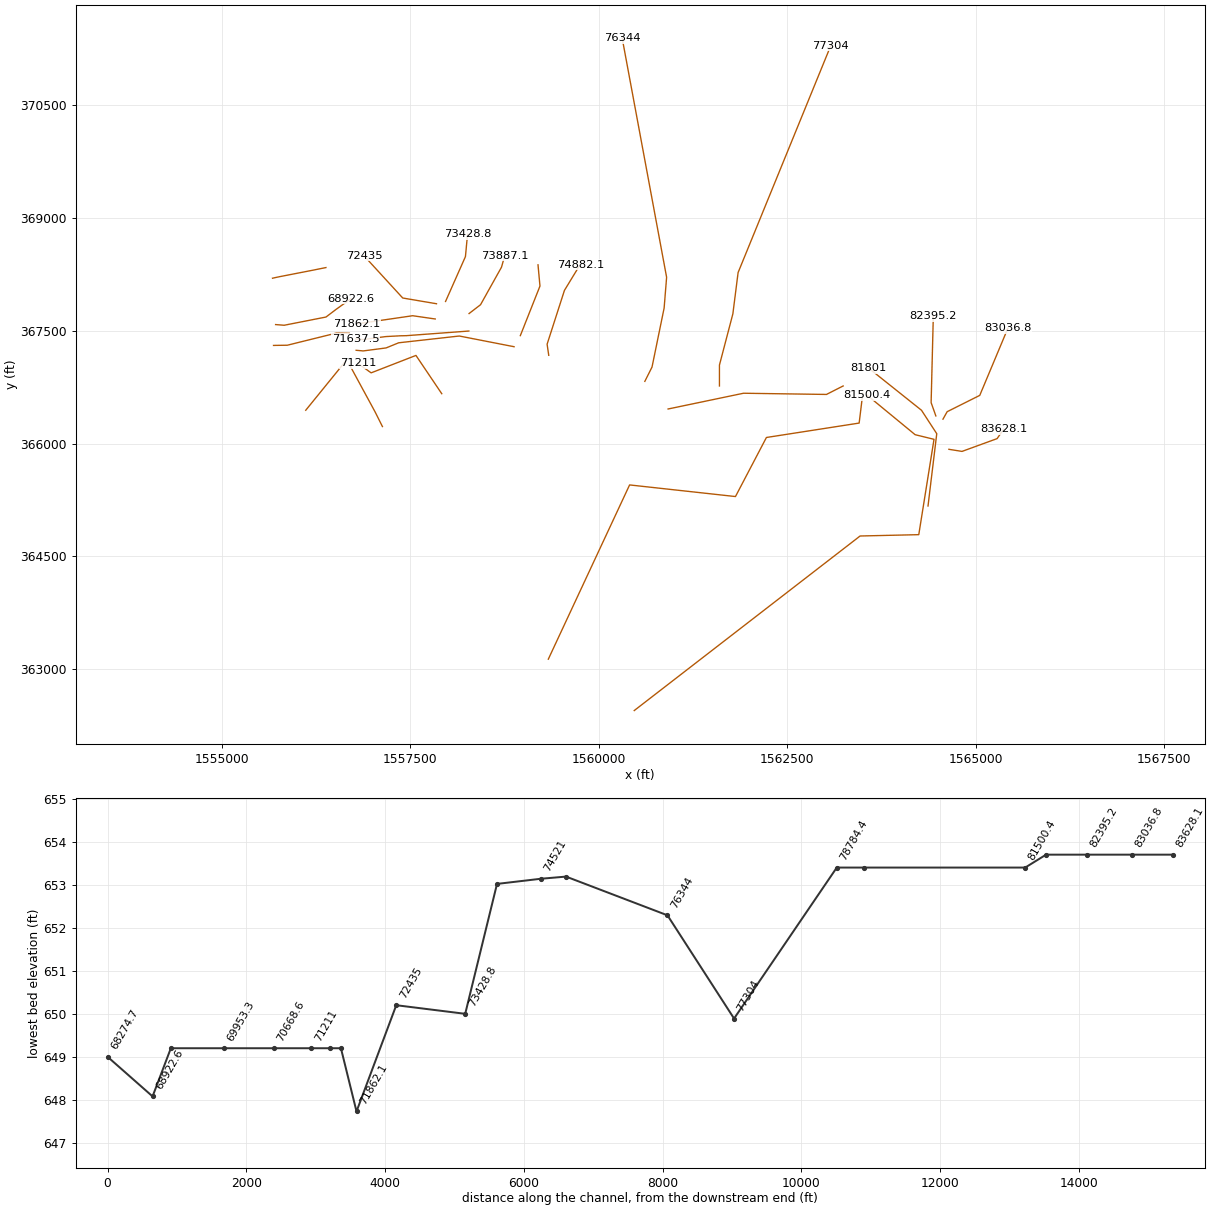
HEC-RAS study MDISLCRK1.prj: MDISLCRK1

--- MDISLCRK1.g01 (geometry) --- (continued)

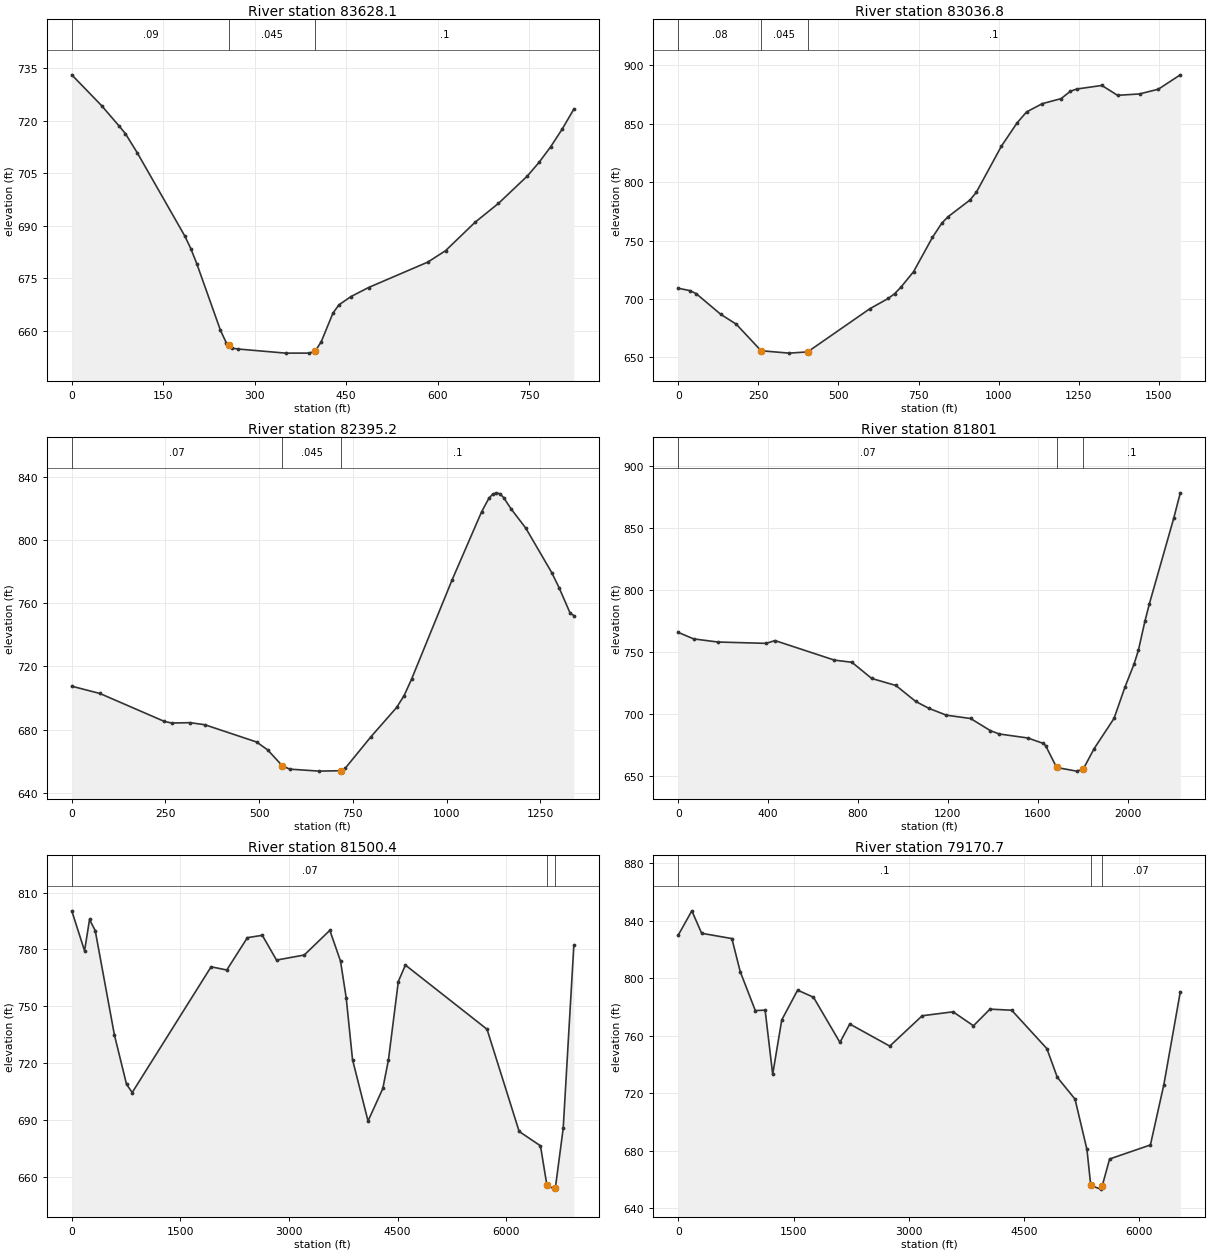
Type RM Length L Ch R = 1 ,83628.1 ,588.7,591.3,593.9
XS GIS Cut Line= 4
     1564645.706      365923.931     1564819.318      365896.153
     1565284.595      366066.292     1565371.401      366191.292
#Sta/Elev= 30
       0  733.06    48.8   724.3    78.1  718.37    87.9  716.31   107.4  710.84
   185.5  687.06   195.2  683.52     205  679.22   243.8  660.24   253.5  656.59
   258.1655.8929   263.2  655.12     273  654.87   350.7   653.7   389.5  653.71
   399.2  654.26     409  656.91   428.4  665.13   438.1  667.46   457.5  669.79
   486.7  672.41   583.8  679.65     613  682.91   661.5  691.03   699.8   696.4
   747.3  704.23   766.3  708.09   785.4  712.55   804.4  717.62   823.4  723.29
#Mann= 3 , 0 , 0
       0     .09       0   258.1    .045       0   399.2      .1       0
Bank Sta=258.1,399.2
XS Rating Curve= 1 ,0
   26600   678.9
Exp/Cntr=0.3,0.1

Type RM Length L Ch R = 1 ,83036.8 ,617,641.6,665.8
XS GIS Cut Line= 4
     1564566.769      366325.431     1564622.325      366424.389
     1565054.617      366641.403     1565428.266      367535.868
#Sta/Elev= 30
       0  709.24    37.8  707.13    56.7  704.46   132.8  686.89   181.2  678.44
   258.6  655.74   345.7   653.7   403.7  654.74   597.2  691.58   655.9  700.61
   675.5  704.67   695.1  710.24   734.3  723.42     793  752.68   822.4  764.97
     842  770.45   910.5  784.81   930.1  791.37  1008.4  830.86  1057.4   850.8
  1086.8  860.12  1135.7   867.2  1194.5  871.52  1223.9  877.89  1243.4  879.74
  1321.8  882.82  1370.7  874.35  1439.3  875.54    1498  879.59  1566.6   891.9
#Mann= 3 , 0 , 0
       0     .08       0   258.6    .045       0   403.7      .1       0
Bank Sta=258.6,403.7
XS Rating Curve= 1 ,0
   26600   678.9
Exp/Cntr=0.3,0.1

Type RM Length L Ch R = 1 ,82395.2 ,573.4,594.2,614.9
XS GIS Cut Line= 3
     1564472.095      366368.375     1564409.595      366545.459
     1564438.682      367696.458
#Sta/Elev= 30
       0   707.4    75.1  702.79   246.8  685.15   266.5  684.11   315.7  684.34
   355.1  683.02   492.8  672.14   522.4  667.16   561.7  657.06   581.4  654.96
   660.1   653.7   719.2  653.97     729   655.4   797.9  675.41   866.8  694.04
   886.5   701.5   906.2  711.78  1014.4  774.59  1093.1  817.64  1112.8  826.36
  1122.7  828.75  1132.5  829.68  1142.3  829.06  1152.2  826.59  1171.9  819.49
  1211.2  807.28  1280.1  779.29  1299.8   769.7  1329.3  753.62  1339.2  752.04
#Mann= 3 , 0 , 0
       0     .07       0   561.7    .045       0   719.2      .1       0
Bank Sta=561.7,719.2
XS Rating Curve= 1 ,0
   26600   678.9
Exp/Cntr=0.3,0.1

Type RM Length L Ch R = 1 ,81801   ,300.9,300.6,300.3
XS GIS Cut Line= 4
     1564368.369      365169.816     1564484.303       366131.65
     1564282.094      366443.257     1563583.648      367002.014
#Sta/Elev= 30
       0  765.82    68.5  760.56   176.1  758.03   391.4  756.94   430.6   759.2
   694.8  743.42   773.1  741.64   861.2  728.58   968.8   722.9  1056.8  710.04
  1115.4  704.45  1193.6   698.9  1301.2  696.23  1389.4  686.42  1428.7  683.72
  1556.5  680.46  1625.3  676.06  1635.1  674.36  1684.3  656.64  1772.7   653.7
  1802.2  655.24  1851.4  671.95  1939.8  696.33    1989  721.96  2028.3  739.94
    2048  751.27  2077.4  775.02  2097.1  788.99  2205.2  857.92  2234.7  878.58
#Mann= 3 , 0 , 0
       0     .07       0  1684.3    .045       0  1802.2      .1       0
Bank Sta=1684.3,1802.2
XS Rating Curve= 1 ,0
   26600   678.9
Exp/Cntr=0.3,0.1

Type RM Length L Ch R = 1 ,81500.4 ,2384.8,2329.7,2274.1
XS GIS Cut Line= 6
     1560472.095      362448.446     1563467.671      364770.766
     1564245.836      364788.512     1564447.858      366056.998
      1564197.79      366118.375     1563562.373      366642.681
#Sta/Elev= 30
       0  800.42   176.8  779.29   245.5  795.85     324  789.97   589.2  734.81
   756.1  708.82   834.7  704.44  1924.6  770.86  2140.7  769.16  2425.4  786.24
  2631.6  787.49    2828   774.4    3211  777.08  3564.5  790.12  3711.8  773.85
  3790.3  754.48  3877.9  721.76    4092  689.38  4296.3  706.58  4374.1  721.76
  4510.3  763.08  4607.9  771.77  5735.5  737.86  6179.3  683.86  6473.5  676.28
  6561.8  655.61  6659.9   653.4  6679.5  654.08  6787.4  685.48  6934.5  782.21
#Mann= 3 , 0 , 0
       0     .07       0  6561.8    .045       0  6679.5      .1       0
Bank Sta=6561.8,6679.5
XS Rating Curve= 1 ,0
   26600   678.9
Exp/Cntr=0.3,0.1

Type RM Length L Ch R = 1 ,79170.7 ,386.7,386.3,386
XS GIS Cut Line= 6
     1559332.772       363132.04     1560410.695      365450.113
     1561814.804      365295.532     1562225.272      366081.305
     1563455.015      366273.043     1563503.626      366668.876
#Sta/Elev= 30
       0  829.96     177  846.87   304.8  831.26   698.1  827.58   806.3  804.64
  1002.9  777.54  1130.7   777.8  1229.1  733.22    1347  771.02  1553.5  791.73
    1760   786.8  2104.2  755.39    2232  768.19  2752.6  752.83  3174.4  773.92
  3576.6  776.67  3841.5  766.96  4056.7  778.53  4339.2  777.77  4797.1  751.07
  4932.5  731.15  5163.2  715.97  5318.5  680.95  5367.7  656.04  5495.5   653.4
  5515.1  655.26  5613.4  674.36  6144.2  684.11  6319.3  726.09  6533.3  790.61
#Mann= 3 , 0 , 0
       0      .1       0  5367.7    .045       0  5515.1     .07       0
Bank Sta=5367.7,5515.1
XS Rating Curve= 1 ,0
   26600   678.9
Exp/Cntr=0.3,0.1

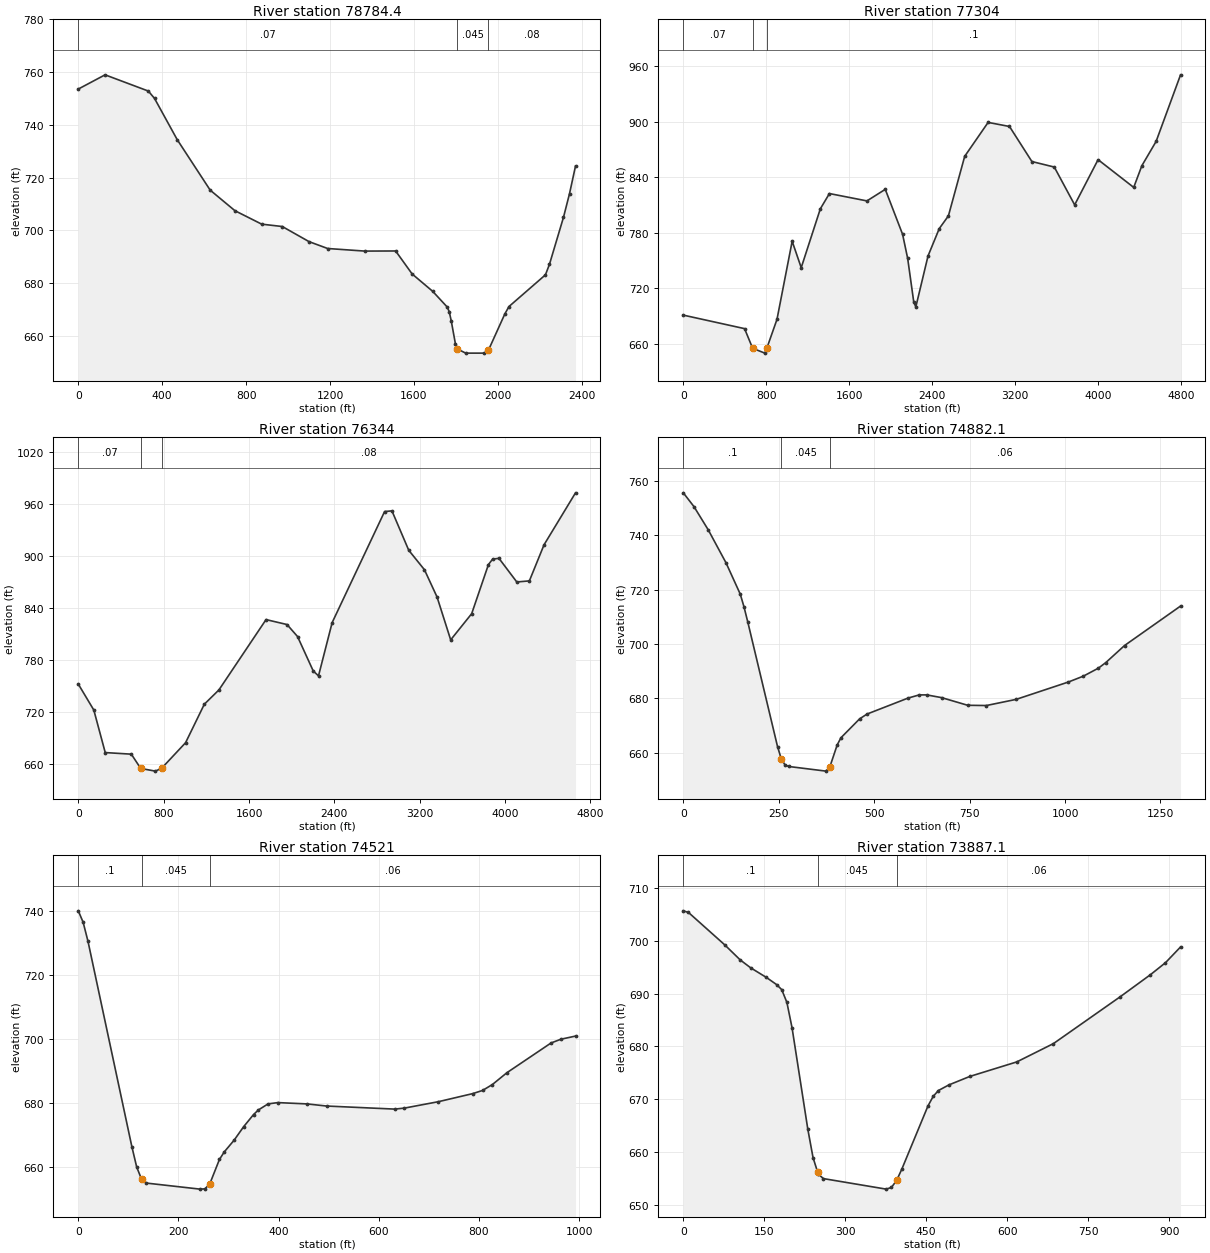
Type RM Length L Ch R = 1 ,78784.4 ,1450.4,1480.4,1510.4
XS GIS Cut Line= 4
     1560921.321      366460.347     1561921.339      366669.911
     1563021.575      366653.966     1563242.929      366766.813
#Sta/Elev= 30
       0   753.6   127.7     759     334  752.84   363.5  750.05   471.6  734.41
   628.8  715.25   746.7  707.45   874.4  702.34   972.6  701.44  1100.3   695.7
  1188.8   693.1  1365.6  692.12    1513  692.16  1591.6  683.44  1689.8  676.84
  1758.6  670.91  1768.4  669.15  1778.2   665.6  1797.9  656.96  1807.7  654.96
    1847   653.4  1935.4   653.4  1955.1  654.46  2033.7  668.29  2053.3  671.08
  2227.2  683.11  2246.3  687.09  2313.2  704.93  2341.9   713.9  2370.6  724.42
#Mann= 3 , 0 , 0
       0     .07       0  1807.7    .045       0  1955.1     .08       0
Bank Sta=1807.7,1955.1
XS Rating Curve= 1 ,0
   26600   678.9
Exp/Cntr=0.3,0.1

Type RM Length L Ch R = 1 ,77304   ,959.3,960,960.6
XS GIS Cut Line= 5
     1561602.304      366766.813     1561602.304      367044.591
     1561780.255      367726.014     1561849.752      368275.374
     1563079.344      371295.547
#Sta/Elev= 30
       0  690.96   590.8  676.36     669   655.1   786.4  649.89     806  655.28
   903.8  686.41  1050.1   770.8  1137.5  742.24  1322.1   805.9  1409.5  822.34
  1771.5  814.39  1948.3  826.89  2115.3  778.31  2164.4   752.2  2223.3  704.96
    2243  699.85  2360.8  754.92  2468.9  784.45  2557.3  798.21  2714.4  862.56
  2940.3  899.22  3146.6  894.82  3362.7  856.93  3578.8  850.97  3775.2  810.11
  4001.1  858.95  4344.9  828.98  4423.4  852.42    4561   878.7  4796.7  950.64
#Mann= 3 , 0 , 0
       0     .07       0     669    .045       0     806      .1       0
Bank Sta=669,806
XS Rating Curve= 1 ,0
   26600   678.9
Exp/Cntr=0.3,0.1

Type RM Length L Ch R = 1 ,76344   ,1463.7,1461.9,1459.9
XS GIS Cut Line= 5
      1560612.72      366827.577     1560708.206      367018.549
     1560868.797      367804.139     1560901.637      368212.814
     1560312.417      371393.203
#Sta/Elev= 30
       0   752.6   145.6  722.65   252.6  673.67   497.1  671.83   585.1  655.38
     722  652.29   780.7  655.51  1005.6  685.05  1181.3   729.4    1318  745.85
  1759.6  826.88  1956.2  821.19  2054.6  807.38    2202  767.66  2251.2  762.05
    2379  823.38  2870.6  951.38  2939.4  952.16  3096.7  906.81  3244.1   884.3
  3362.1  852.92  3489.9  803.53  3686.6  833.68  3843.8  890.33  3883.2   896.6
  3942.2  897.48  4109.3  870.24  4227.3  871.47  4364.9   913.1  4659.8  972.94
#Mann= 3 , 0 , 0
       0     .07       0   585.1    .045       0   780.7     .08       0
Bank Sta=585.1,780.7
XS Rating Curve= 1 ,0
   26600   678.9
Exp/Cntr=0.3,0.1

Type RM Length L Ch R = 1 ,74882.1 ,362.6,361.1,359.7
XS GIS Cut Line= 4
     1559338.415      367174.799     1559316.713      367322.368
     1559546.748      368038.514     1559755.081      368381.396
#Sta/Elev= 30
       0  755.69      28   750.6    65.3  742.06   111.9  729.91   149.2  718.38
   158.9  713.74   168.7  708.24   246.8  662.25   256.6  657.71   266.4  655.49
   276.2   654.9   373.8  653.19   383.6  654.64   403.1  662.83   412.9  665.47
   461.8  672.43   481.3  674.21   588.7  680.09     618  681.26   637.6  681.27
   676.7  680.26     745  677.44   793.9  677.35     872  679.62    1009  686.02
  1048.1  688.18  1087.3  691.11  1106.8  693.17  1155.8  699.44  1302.6  713.99
#Mann= 3 , 0 , 0
       0      .1       0   256.6    .045       0   383.6     .06       0
Bank Sta=256.6,383.6
XS Rating Curve= 1 ,0
   26600   678.9
Exp/Cntr=0.3,0.1

Type RM Length L Ch R = 1 ,74521   ,636.8,633.9,630.9
XS GIS Cut Line= 3
     1558961.728      367436.353     1559222.145      368096.075
     1559196.103      368378.193
#Sta/Elev= 30
       0  740.11     9.7  736.54    19.4  730.57   106.9  666.45   116.6  660.04
   126.3  656.25     136  655.03   242.9  653.14   252.6  653.22   262.3   654.7
   281.8  662.42   291.5  664.79   310.9   668.4   330.3  672.69   349.8  676.43
   359.5  677.88   378.9  679.78   398.4  680.18   456.6  679.77   495.5  679.11
   631.5  678.15     651  678.46     719  680.47   787.4  682.99     807  683.98
   826.5  685.81   855.8  689.54   943.7  698.81   963.3  699.98   992.6  700.97
#Mann= 3 , 0 , 0
       0      .1       0   126.3    .045       0   262.3     .06       0
Bank Sta=126.3,262.3
XS Rating Curve= 0 ,0
Exp/Cntr=0.3,0.1

Type RM Length L Ch R = 1 ,73887.1 ,456.2,458.3,460.4
XS GIS Cut Line= 4
     1558281.991      367730.355     1558433.901      367847.542
     1558711.679      368346.674     1558755.081      368498.584
#Sta/Elev= 30
       0  705.65     9.6  705.34    76.7  699.22   105.5  696.36   124.7  694.88
   153.5  693.08   172.7  691.71   182.3  690.75   191.9  688.33   201.5   683.5
   230.6  664.38   240.3  658.99   248.6656.3117     250  655.86   259.6  655.01
   375.8  653.02   385.5  653.34   395.2  654.67   404.9  656.83   453.3  668.77
     463  670.58   472.6  671.67     492  672.73   530.7  674.33   617.8  677.08
   685.6  680.54   809.6  689.42   865.3  693.57   893.2  695.84   921.1  698.82
#Mann= 3 , 0 , 0
       0      .1       0   248.6    .045       0   395.2     .06       0
Bank Sta=248.6,395.2
XS Rating Curve= 0 ,0
Exp/Cntr=0.3,0.1

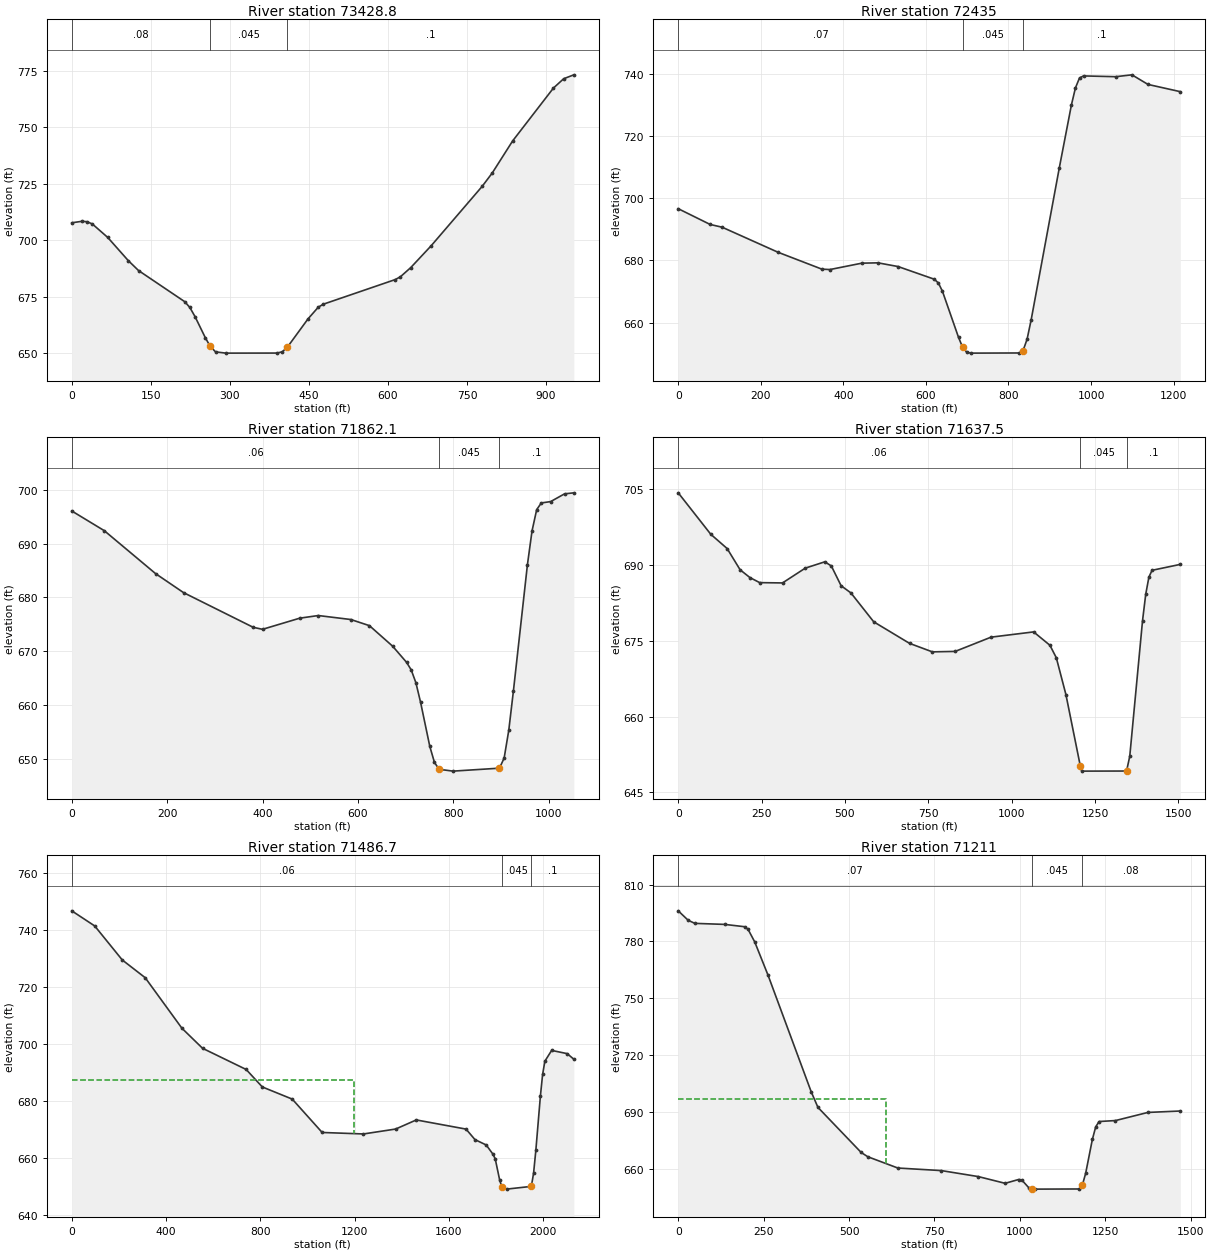
Type RM Length L Ch R = 1 ,73428.8 ,967.8,993.8,1019.9
XS GIS Cut Line= 3
     1557969.932      367890.903     1558233.821      368488.125
     1558261.599      368786.736
#Sta/Elev= 30
       0  707.73    19.5  708.39    29.2  708.19      39  707.21    68.2  701.25
   107.2  690.98   126.7  686.58   214.4  672.78   224.1  670.21   233.9  666.18
   253.4  656.85   262.7653.0149   272.9  650.55   292.4     650   389.8  650.03
   399.6  650.61   409.3  652.69   448.3  665.16   467.8  670.35   477.5  671.68
   613.9  682.58   623.7  683.83   643.2  687.86     682  697.54   778.7  723.83
     798   729.8   836.7     744   914.1  767.41   933.5  771.53   952.8  773.26
#Mann= 3 , 0 , 0
       0     .08       0   262.7    .045       0   409.3      .1       0
Bank Sta=262.7,409.3
XS Rating Curve= 0 ,0
Exp/Cntr=0.3,0.1

Type RM Length L Ch R = 1 ,72435   ,550.6,572.8,595
XS GIS Cut Line= 3
       1557849.7      367860.563     1557401.783      367936.952
     1556887.894      368499.452
#Sta/Elev= 30
       0   696.6    77.3  691.54   106.4  690.65   241.7  682.61     348  677.18
   367.4  677.05   444.7   679.1   483.7  679.21   532.5  678.02   620.4  673.94
   630.2  672.73     640   670.1     679  655.27   688.8  652.11   698.6  650.53
   708.4   650.2   825.6  650.25     834650.8735   835.3  650.97   845.1  654.67
   854.9  660.84   923.2  709.76   952.6     730   962.3  735.43   972.1  738.61
   981.8  739.26    1060  739.01  1099.1  739.61  1138.1  736.52  1216.3   734.2
#Mann= 3 , 0 , 0
       0     .07       0   688.8    .045       0     834      .1       0
Bank Sta=688.8,834
XS Rating Curve= 0 ,0
Exp/Cntr=0.3,0.1

Type RM Length L Ch R = 1 ,71862.1 ,225.1,224.7,224.1
XS GIS Cut Line= 3
     1557833.256      367657.707     1557533.777       367701.11
     1556791.589      367592.603
#Sta/Elev= 30
       0  696.07    68.3   692.4   175.7  684.43   234.3   680.9   380.5  674.45
     400  674.08     478  676.15   516.9  676.64   585.1   675.9   624.1  674.76
   672.8  670.94     702  667.94   711.7  666.54   721.5  664.16   731.2  660.58
   750.7  652.32   760.4  649.36   770.2  648.07   799.4  647.73   896.8  648.28
   906.6  650.17   916.3  655.34     926  662.63   955.3  686.03     965  692.35
   974.8  696.32   984.5  697.56    1004  697.81  1033.2  699.25  1052.7  699.44
#Mann= 3 , 0 , 0
       0     .06       0   770.2    .045       0   896.8      .1       0
Bank Sta=770.2,896.8
XS Rating Curve= 0 ,0
Exp/Cntr=0.3,0.1

Type RM Length L Ch R = 1 ,71637.5 ,150.8,150.8,150.8
XS GIS Cut Line= 6
      1558278.96      367497.384     1557450.741       367435.91
     1557372.616      367434.174     1557176.436      367423.757
     1556872.616      367383.827     1556778.866      367392.507
#Sta/Elev= 30
       0  704.27    97.7  696.06   146.6  693.25   185.6  689.04     215   687.5
   244.3   686.5   312.7  686.44     381  689.37   439.7  690.62   459.2  689.79
   488.5  685.88   517.8  684.47   586.2  678.75   693.7  674.48   762.1   672.8
   830.5  672.89   938.1  675.71  1065.8  676.75  1114.7   674.1  1133.8  671.64
  1162.6  664.36  1205.9  650.19  1210.4   649.2  1344.5  649.22  1354.1  652.14
  1392.4  678.96    1402   684.2  1411.5  687.59    1421  688.94  1505.7  690.11
#Mann= 3 , 0 , 0
       0     .06       0  1205.9    .045       0  1344.5      .1       0
Bank Sta=1205.9,1344.5
XS Rating Curve= 0 ,0
Exp/Cntr=0.3,0.1

Type RM Length L Ch R = 1 ,71486.7 ,270.2,275.6,281.1
XS GIS Cut Line= 6
     1558878.678      367288.838     1558152.444      367431.229
     1557348.405      367341.134     1557181.644      367272.716
     1556877.825      367232.785     1556784.075      367241.466
#Sta/Elev= 30
       0  746.66    97.4  741.36   214.2  729.46   311.6  723.24   467.4  705.55
     555  698.52   740.1   691.1   808.6  684.98   935.7  680.72  1062.6  669.04
    1238  668.52  1374.4  670.24  1462.1  673.43  1673.2  670.22  1711.1  666.54
  1758.8  664.66  1787.6  661.42  1797.1  659.79  1816.3  652.24  1825.9  649.82
    1845   649.2  1950.4  650.16  1959.9  654.83  1969.5  662.85  1988.7  681.76
  1998.2   689.4  2007.8  694.01  2036.5  697.78  2102.4  696.65  2130.7  694.69
#Mann= 3 , 0 , 0
       0     .06       0  1825.9    .045       0  1950.4      .1       0
#XS Ineff= 2 , 0
         1199.63   687.4
Permanent Ineff=
       F       F
Bank Sta=1825.9,1950.4
XS Rating Curve= 0 ,0
Exp/Cntr=0.3,0.1

Type RM Length L Ch R = 1 ,71211   ,575.3,542.5,509.7
XS GIS Cut Line= 4
     1557919.477      366663.838     1557577.378      367173.005
     1556982.859      366941.118     1556805.776      367068.723
#Sta/Elev= 30
       0  796.12    29.2  791.11    48.7   789.5   136.3  788.95   194.7  787.72
   204.5  786.31     224  779.68   262.9  762.14   389.5  700.47     409  692.35
   535.5  668.56     555  666.29   642.9  660.34   770.5  658.98   878.5  655.82
     957  652.27   996.3  654.28  1006.1  653.95  1025.8  650.02  1035.6  649.26
  1045.4   649.2    1173  649.28  1182.8  651.16  1192.7  657.53  1212.3   675.4
  1222.1  682.06  1231.9  684.89    1280   685.4  1374.9  689.69  1469.8  690.44
#Mann= 3 , 0 , 0
       0     .07       0  1035.6    .045       0  1182.8     .08       0
#XS Ineff= 2 , 0
          609.52  696.57
Permanent Ineff=
       F       F
Bank Sta=1035.6,1182.8
XS Rating Curve= 0 ,0
Exp/Cntr=0.3,0.1

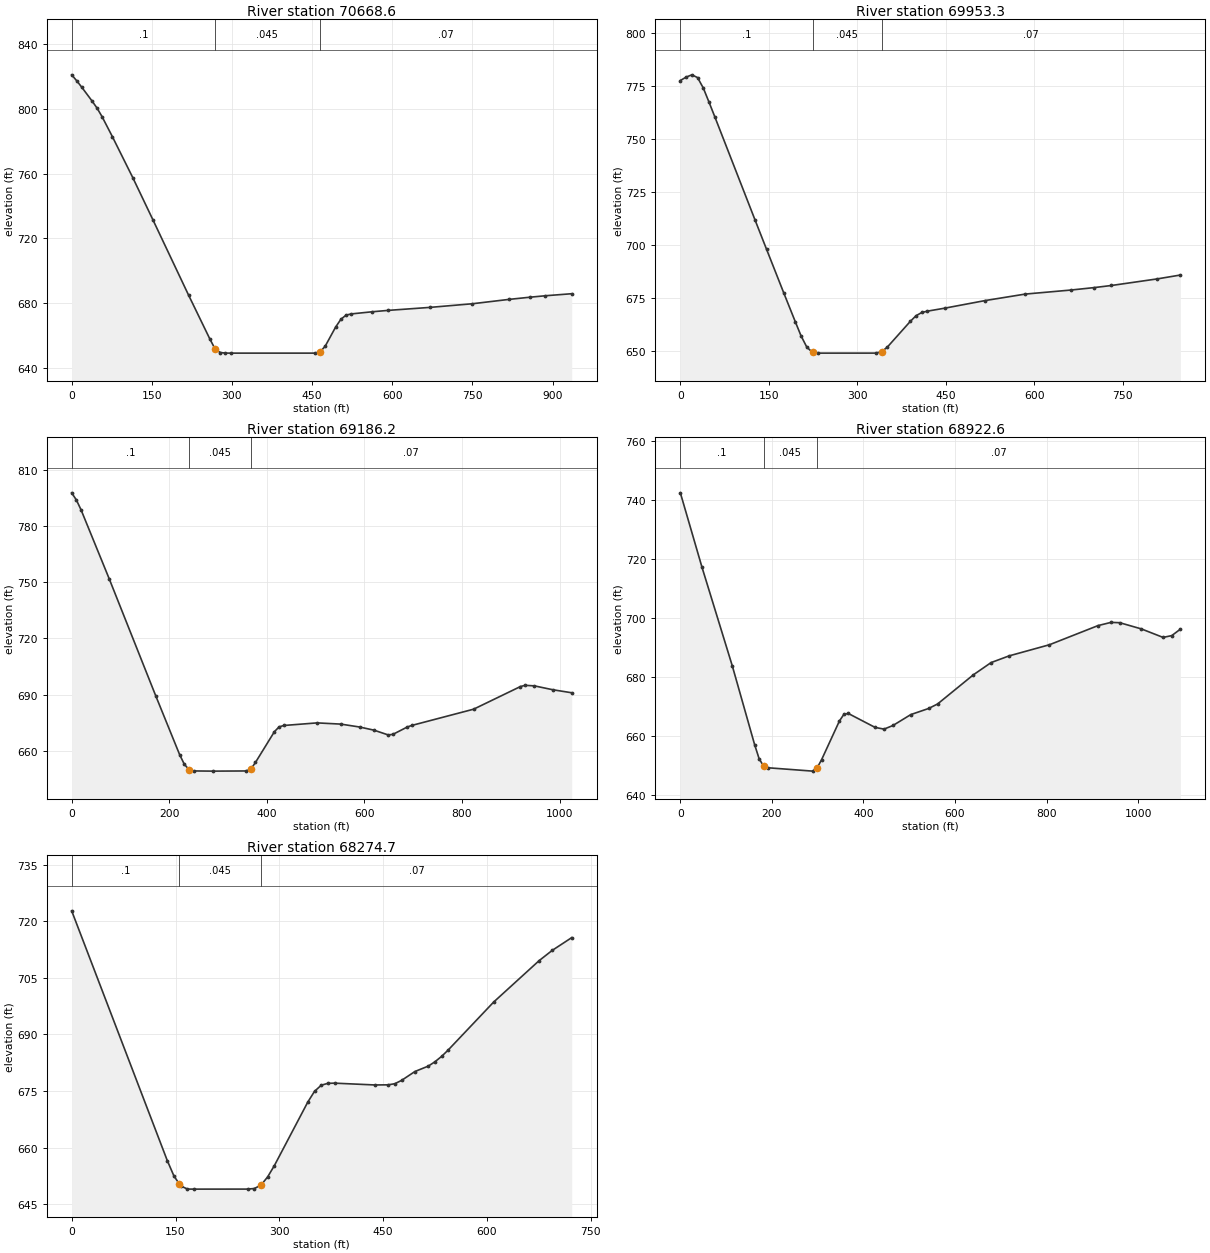
Type RM Length L Ch R = 1 ,70668.6 ,741.9,715.3,688.7
XS GIS Cut Line= 3
     1557132.772      366226.709      1557034.94       366422.63
     1556693.797      367053.098
#Sta/Elev= 30
       0  820.93     9.5  817.25      19  813.23    38.1   804.8    47.6  800.35
    57.1  794.98    76.2  782.77   114.3  757.54   152.3  731.29     219  684.83
   258.3  658.13   268.1  651.94   277.9  649.58   287.7  649.23   297.6   649.2
   454.7   649.2   464.5  649.87   474.3   653.4   493.9  665.24   503.8  670.09
   513.6  672.67   523.4   673.4   562.7  674.73   592.1  675.57   670.7  677.43
   749.3  679.65     818  682.34   857.3   683.7   886.7  684.61   935.8  685.86
#Mann= 3 , 0 , 0
       0      .1       0   268.1    .045       0   464.5     .07       0
Bank Sta=268.1,464.5
XS Rating Curve= 0 ,0
Exp/Cntr=0.3,0.1

Type RM Length L Ch R = 1 ,69953.3 ,781.7,767.1,752.5
XS GIS Cut Line= 2
     1556115.672      366443.723     1556649.526      367102.577
#Sta/Elev= 30
       0  777.74     9.8  779.34    19.5  780.42    29.2  779.12      39  774.15
    48.7  767.48    58.5  760.59   126.7  711.96   146.2  698.15   175.4  677.57
   194.9  664.02   204.7  657.34   214.4  652.05   224.2   649.5   233.9   649.2
   331.4  649.21   341.2  649.88   350.9  652.01   389.9  664.15   399.6  666.82
   409.4  668.36   419.1     669   448.4   670.4   516.6  673.97   584.8  677.04
   662.8  678.96   701.8   680.1     731  681.09     809  684.21     848  686.03
#Mann= 3 , 0 , 0
       0      .1       0   224.2    .045       0   341.2     .07       0
Bank Sta=224.2,341.2
XS Rating Curve= 0 ,0
Exp/Cntr=0.3,0.1

Type RM Length L Ch R = 1 ,69186.2 ,264.7,263.6,262.5
XS GIS Cut Line= 4
     1555688.762      367306.136     1555871.054       367308.74
     1556522.095      367470.198      1556693.97      367467.594
#Sta/Elev= 30
       0  797.64     9.6  793.85    19.2   788.6    76.8  751.88   172.7  689.13
   221.2  658.05   230.9  652.86   240.6     650   250.4   649.3   289.2   649.2
   357.3  649.29     367  650.16   376.7  653.82   415.6  670.26   425.3  672.83
   435.1  673.55   503.1  674.93   551.7  674.28   590.6  672.71   619.8  671.04
   648.9   668.5   658.6  668.83   687.8  672.72   697.5   673.6   823.9  682.24
   919.9  694.32   929.5  694.97   948.6  694.67   986.8  692.58    1025     691
#Mann= 3 , 0 , 0
       0      .1       0   240.6    .045       0     367     .07       0
Bank Sta=240.6,367
XS Rating Curve= 0 ,0
Exp/Cntr=0.3,0.1

Type RM Length L Ch R = 1 ,68922.6 ,648,647.9,647.9
XS GIS Cut Line= 5
     1555716.193      367583.393     1555829.387      367574.365
     1556384.075       367683.74       1556524.7      367790.511
     1556717.408      367928.532
#Sta/Elev= 30
       0  742.48    47.3  717.23   113.6  683.73   162.3  657.05     172  652.33
   181.8  649.79   191.5  649.22     289  648.08   298.8  649.18   308.5  651.93
   347.5  665.08   357.2  667.33     367  667.63   425.5  662.91     445  662.33
   464.5  663.56   503.5  667.26   542.4  669.33     562  670.86   639.9  680.72
   678.9   684.9   718.2  687.17   806.4  690.95   912.4  697.44   940.8  698.53
   959.8  698.43  1007.2  696.32  1054.6  693.44  1073.6  694.05  1092.5  696.24
#Mann= 3 , 0 , 0
       0      .1       0   181.8    .045       0   298.8     .07       0
Bank Sta=181.8,298.8
XS Rating Curve= 0 ,0
Exp/Cntr=0.3,0.1

Type RM Length L Ch R = 1 ,68274.7 ,394.3,395.7,397.2
XS GIS Cut Line= 4
     1555675.132      368200.165     1555762.812      368219.346
      1556199.28       368304.67     1556383.465      368341.831
#Sta/Elev= 30
       0  722.79   138.1  656.58   147.8  652.46   155.5650.3906   157.4  649.88
   167.1  649.02   176.8     649   254.1  649.01   263.8  649.16   273.4  650.04
   283.1  652.24   292.8  655.23   341.1  672.08   350.8  674.92   360.5  676.55
   370.1  677.05   379.8   677.1   437.8  676.62   457.1  676.65   466.8  676.95
   476.5  677.82   495.8  680.18   515.2  681.62   524.8  682.77   534.5  684.21
   543.9  685.88   609.6   698.6   675.4   709.6   694.2   712.3   722.4  715.69
#Mann= 3 , 0 , 0
       0      .1       0   155.5    .045       0   273.4     .07       0
Bank Sta=155.5,273.4
XS Rating Curve= 0 ,0
Exp/Cntr=0.3,0.1