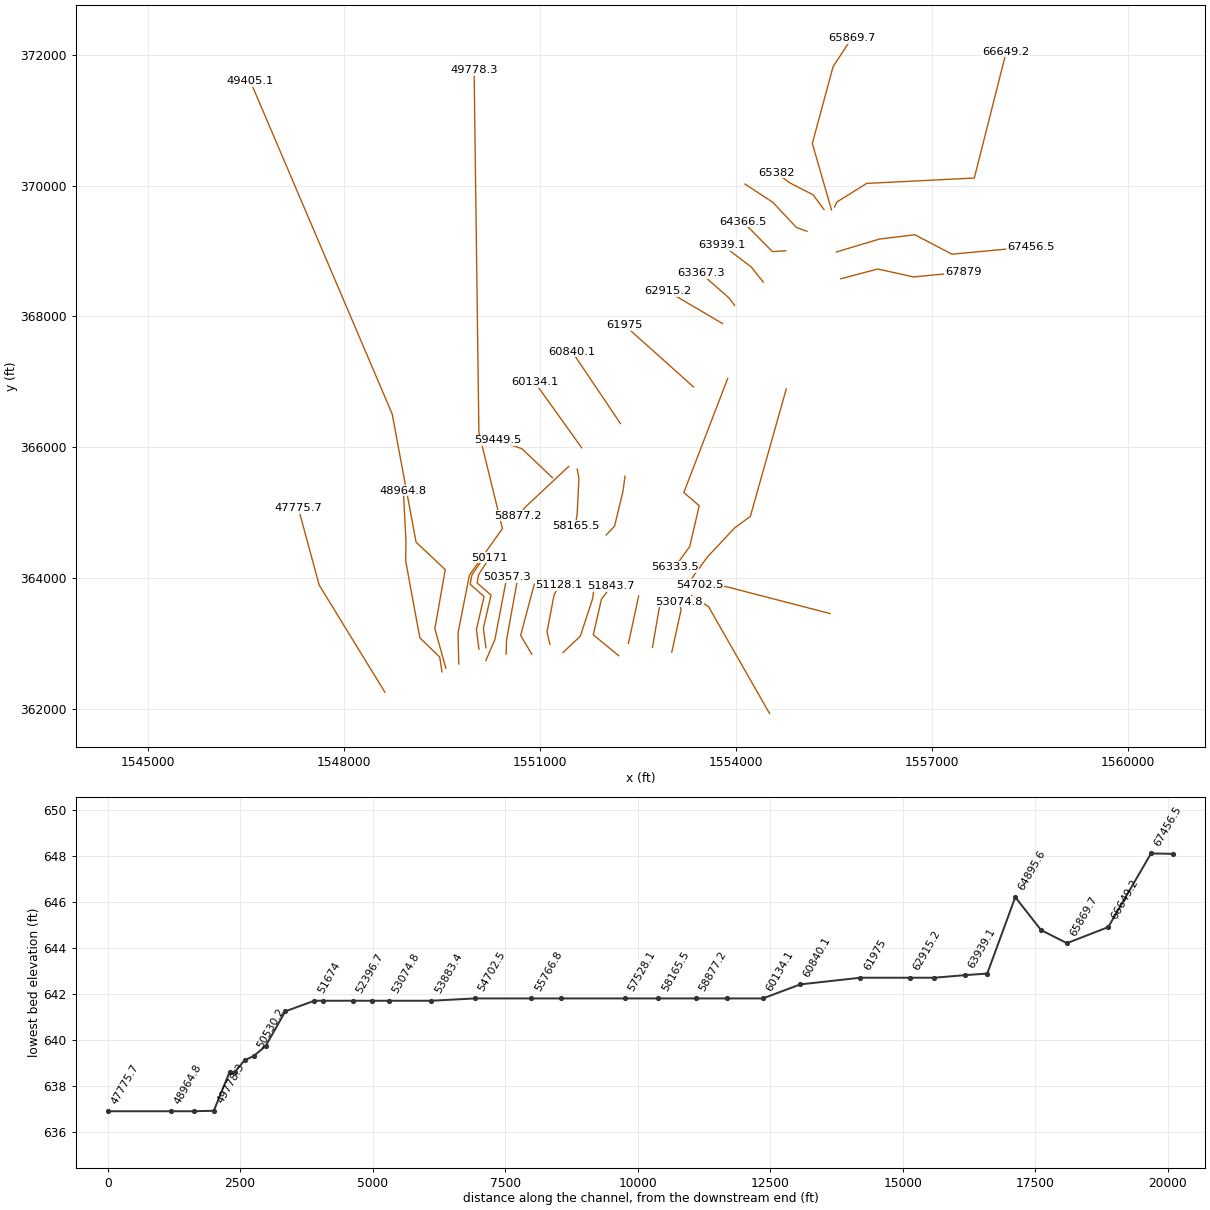
HEC-RAS study MDISLCRK1.prj: MDISLCRK1

--- MDISLCRK1.g01 (geometry) --- (continued)

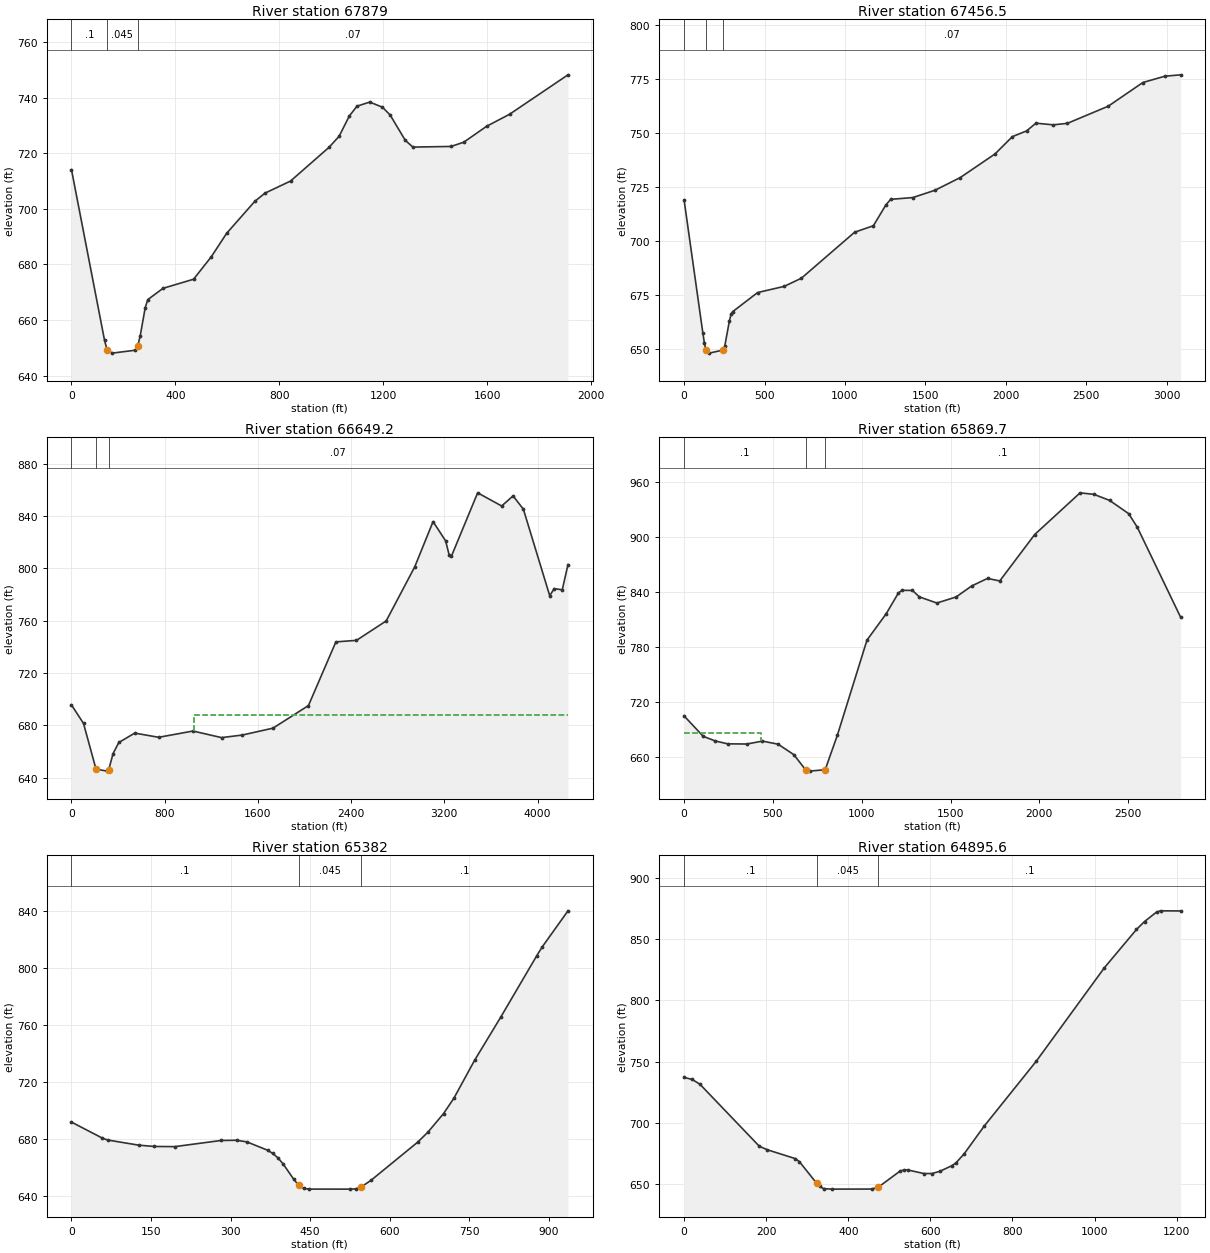
Type RM Length L Ch R = 1 ,67879   ,421.7,422.5,423.3
XS GIS Cut Line= 4
     1555601.474      368577.132     1556169.183      368726.438
     1556716.058       368604.91     1557475.141      368678.808
#Sta/Elev= 30
       0  714.13   127.2  652.66     137  649.22   156.5  648.08   244.6  649.12
   254.4  650.52   264.2  654.24   283.7  664.48   293.5  667.35   352.2  671.42
   469.6  674.69   538.1  682.82   596.8  691.22     705  702.72   744.3  705.69
   842.6  710.04     990  722.13  1029.3  726.14  1068.6  733.44  1098.1  736.99
  1147.2  738.48  1196.1  736.63  1225.4  733.88  1284.1  724.69  1313.4  722.27
  1460.1   722.5    1509  724.03    1597  729.77    1685  734.08  1909.9  748.29
#Mann= 3 , 0 , 0
       0      .1       0     137    .045       0   254.4     .07       0
Bank Sta=137,254.4
XS Rating Curve= 0 ,0
Exp/Cntr=0.3,0.1

Type RM Length L Ch R = 1 ,67456.5 ,800.1,807.2,814.4
XS GIS Cut Line= 5
     1555534.769      368987.039     1556196.227      369184.955
     1556736.955      369250.193     1557303.157        368952.9
     1558509.755      369065.747
#Sta/Elev= 30
       0  718.87   116.7  657.33   126.4  652.64   136.1  649.33   155.6   648.1
   243.1  649.52   252.8  651.37     282  663.14   291.7  666.02   301.5  667.25
     457   676.1   622.4  678.97   729.3  682.74    1060  703.99  1176.7  706.99
  1254.8  716.67  1284.3  719.19    1422  720.01  1559.8   723.4  1717.2  729.28
  1933.2   740.2  2040.7  748.18  2128.7  750.81  2187.3   754.4  2294.8  753.63
  2382.8  754.32  2636.9  762.26  2851.9   773.2  2988.7  776.11  3086.4  776.75
#Mann= 3 , 0 , 0
       0      .1       0   136.1    .045       0   243.1     .07       0
Bank Sta=136.1,243.1
XS Rating Curve= 0 ,0
Exp/Cntr=0.3,0.1

Type RM Length L Ch R = 1 ,66649.2 ,751.4,779.5,807.6
XS GIS Cut Line= 5
     1555508.293      369675.841     1555543.016      369751.796
     1555999.179      370036.084      1557645.49      370118.402
      1558134.32      372049.688
#Sta/Elev= 30
       0  695.49   103.1   681.4   210.6   646.4   308.3   644.9   318.1  645.54
   357.2  658.35     406  666.79   542.8  673.97   748.6  670.76  1042.9  675.55
  1288.2  670.52  1464.8  672.46  1729.7  677.75  2033.9  695.02  2269.4   743.7
    2446  744.87  2701.2  759.71  2946.5  801.12  3103.6  835.65  3211.5  820.89
  3240.9  810.44  3260.6   809.1  3486.3  857.65  3692.4  847.59  3790.5  855.32
  3878.8  845.12  4104.6  779.07  4143.8  784.39  4212.5  783.52  4261.6  802.78
#Mann= 3 , 0 , 0
       0      .1       0   210.6    .045       0   318.1     .07       0
#XS Ineff= 2 , 0
                         1050.39          687.67
Permanent Ineff=
       F       F
Bank Sta=210.6,318.1
XS Rating Curve= 0 ,0
Exp/Cntr=0.3,0.1

Type RM Length L Ch R = 1 ,65869.7 ,469,487.8,505.9
XS GIS Cut Line= 4
     1555460.984      369629.834     1555166.919      370647.059
     1555485.217      371824.288     1555768.869      372255.852
#Sta/Elev= 30
       0  704.49   107.8  682.17   176.5  677.08   245.1  674.02     353   673.8
   441.2     677   529.4   673.6   617.7  662.19   686.3  645.08   705.9   644.2
   794.2  645.77   862.8  683.42  1029.5  787.29  1137.6  816.09  1206.4  838.79
  1226.1  841.66  1285.1  841.58  1324.4  834.53  1422.8   827.8  1530.9   834.4
  1619.4  846.51    1708  854.69  1776.8  851.92  1973.5  902.61  2229.2  948.17
  2307.6  946.47  2395.3  939.88  2502.5  925.43  2551.2  910.55  2794.8  812.36
#Mann= 3 , 0 , 0
       0      .1       0   686.3    .045       0   794.2      .1       0
#XS Ineff= 2 , 0
          434.38  685.35
Permanent Ineff=
       F       F
Bank Sta=686.3,794.2
XS Rating Curve= 0 ,0
Exp/Cntr=0.3,0.1

Type RM Length L Ch R = 1 ,65382   ,494.2,486.3,478.5
XS GIS Cut Line= 4
     1555346.277      369636.874     1555177.006      369862.568
     1554821.103       370044.86      1554617.11      370196.769
#Sta/Elev= 30
       0  691.88    58.4  680.59    68.1   679.3   126.5  675.69   155.6  674.76
   194.6  674.63   282.1  678.97   311.4  679.11   330.9  677.96   369.9   672.1
   379.6  669.84   389.4  666.72   399.2  662.44   418.7  651.93   428.4  647.45
   438.2  645.28   447.9  644.79   525.9  644.77   535.7  644.93   545.4  646.04
     565  651.01   652.7  677.73   672.2  684.82   701.6  697.86   721.1  708.65
   760.2  735.33   809.2  765.48   877.6  808.95   887.4  814.86   936.3  840.38
#Mann= 3 , 0 , 0
       0      .1       0   428.4    .045       0   545.4      .1       0
Bank Sta=428.4,545.4
XS Rating Curve= 0 ,0
Exp/Cntr=0.3,0.1

Type RM Length L Ch R = 1 ,64895.6 ,528.4,529.1,529.8
XS GIS Cut Line= 4
     1555085.984      369303.445      1554922.79      369362.473
     1554561.679      369747.889     1554136.599       370026.03
#Sta/Elev= 30
       0  737.22    19.3   735.7    38.6  731.71   183.3  681.15   202.9  678.28
   271.4  671.03   281.1  668.55   323.2650.8878     330  648.48   339.8   646.6
   359.4   646.2   457.2  646.27   473.2647.8002   525.6  660.76   535.4  661.86
   545.2  661.83   584.3   658.9   603.9  658.91   623.4  660.75   652.8  665.37
   662.6   667.7   682.1  674.86     731   697.5     858  750.47  1024.1  826.72
  1102.2  857.88  1121.8  864.37  1151.1  872.06  1160.8  873.09  1209.7  872.99
#Mann= 3 , 0 , 0
       0      .1       0   323.2    .045       0   473.2      .1       0
Bank Sta=323.2,473.2
XS Rating Curve= 0 ,0
Exp/Cntr=0.3,0.1

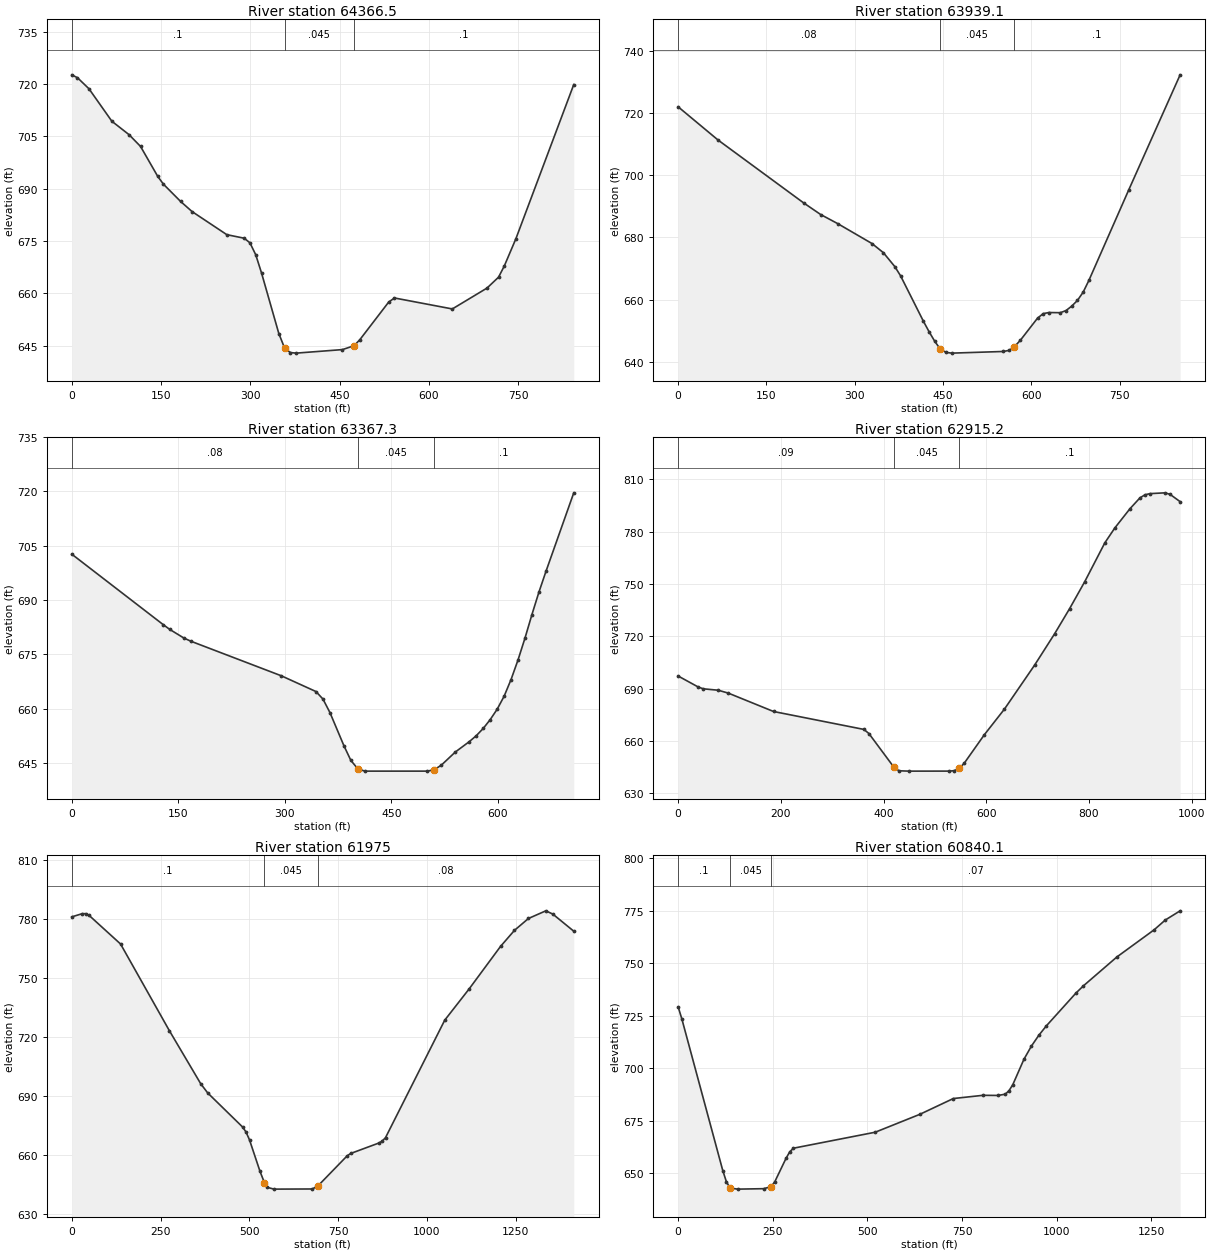
Type RM Length L Ch R = 1 ,64366.5 ,424.2,427.4,430.7
XS GIS Cut Line= 3
     1554759.161      369005.268     1554557.338      368992.247
      1554105.95      369447.976
#Sta/Elev= 30
       0  722.62     9.6  721.79    28.9  718.63    67.4  709.32    96.3  705.47
   115.6   702.1   144.5  693.52   154.1  691.28     183  686.33   202.2  683.44
   260.6  676.82   289.7  675.81   299.4   674.5   309.2  671.07   318.9  665.87
     348   648.5   357.7  644.33   367.5  643.04   377.2  642.88   454.9  643.89
   474.4     645   484.1  646.71   532.7  657.52   542.4  658.68   639.6  655.54
   697.9  661.52   717.3  664.64     727  667.86   746.5  675.68   843.7  719.83
#Mann= 3 , 0 , 0
       0      .1       0   357.7    .045       0   474.4      .1       0
Bank Sta=357.7,474.4
XS Rating Curve= 0 ,0
Exp/Cntr=0.3,0.1

Type RM Length L Ch R = 1 ,63939.1 ,573.5,571.8,570.2
XS GIS Cut Line= 3
     1554416.279      368525.667     1554236.158      368753.532
     1553789.109      369094.243
#Sta/Elev= 30
       0  721.99    67.8  711.31     213  691.12     242  687.37   271.1  684.43
   329.2  678.04   348.6  675.09     368  670.62   377.7  667.68   416.4  653.11
   426.1  649.71   435.8  646.61   445.5  644.03   455.2  643.04   464.9  642.81
   552.1  643.34   561.8  643.68   570.3 644.714   581.2  646.95   610.3  654.04
     620  655.51   629.6  655.86     649  655.81   658.7  656.49   668.4  657.92
   678.1  659.75   687.8   662.4   697.5  666.16   765.3  695.31   852.5  732.27
#Mann= 3 , 0 , 0
       0     .08       0   445.5    .045       0   570.3      .1       0
Bank Sta=445.5,570.3
XS Rating Curve= 0 ,0
Exp/Cntr=0.3,0.1

Type RM Length L Ch R = 1 ,63367.3 ,447.8,452,456.3
XS GIS Cut Line= 3
     1553975.741      368171.934     1553893.276      368282.611
     1553465.759      368658.046
#Sta/Elev= 30
       0  702.67   128.8  683.19     138  681.87   157.6  679.52   167.4  678.63
     295  669.06     344  664.69   353.8  662.61   363.6  658.89   383.3  649.72
   393.1  645.65   402.9  643.34   412.7   642.7     501   642.7   510.8  643.11
   520.6  644.37   540.2  647.98   559.8  650.84   569.6  652.47   579.5   654.5
   589.3  656.93   599.1   659.8   608.9  663.39   618.7  668.02   628.5  673.43
   638.3  679.46   648.1  685.97   657.9  692.15   667.8  697.88     707  719.62
#Mann= 3 , 0 , 0
       0     .08       0   402.9    .045       0   510.8      .1       0
Bank Sta=402.9,510.8
XS Rating Curve= 0 ,0
Exp/Cntr=0.3,0.1

Type RM Length L Ch R = 1 ,62915.2 ,944.7,940.2,935.7
XS GIS Cut Line= 2
     1553792.457      367892.082     1552949.967      368388.009
#Sta/Elev= 30
       0  697.24    39.1  690.94    48.9   689.9    78.2  689.08    97.8  687.42
   185.8  676.89   361.7  666.62   371.5  664.27   420.4  644.86   430.2  642.89
   449.7   642.7   527.9  642.71   537.7  642.96   547.5  644.26   557.2  647.26
   596.4   663.6   635.4  678.24   694.1  703.43   733.2  721.46   762.5  735.93
   791.9  751.36     831  773.61   850.5  782.16   879.8  793.12   899.4   799.4
   909.2  801.15     919  801.81   948.3  802.27   958.1  801.38   977.6  797.21
#Mann= 3 , 0 , 0
       0     .09       0   420.4    .045       0   547.5      .1       0
Bank Sta=420.4,547.5
XS Rating Curve= 0 ,0
Exp/Cntr=0.3,0.1

Type RM Length L Ch R = 1 ,61975   ,1140.5,1134.9,1129.1
XS GIS Cut Line= 2
     1553349.164       366921.65     1552296.321      367864.572
#Sta/Elev= 30
       0  781.12    29.4  782.74    39.3  782.74    49.1  781.82   137.4  767.32
   274.8  723.26   363.2  696.25   382.8  691.59   480.9  674.29   490.8   671.7
   500.6  667.65     530  651.72   542.6645.9257   549.6  643.64   569.3   642.7
   677.2  642.78   692.6644.2372   775.4  659.63   785.2  660.82   863.7  666.07
   873.5  667.01   883.4  668.87  1050.2  728.62  1118.9   744.5  1207.2  766.09
  1246.5  774.27  1285.8   780.3  1334.8  784.19  1354.5  782.53  1413.4  773.84
#Mann= 3 , 0 , 0
       0      .1       0   542.6    .045       0   692.6     .08       0
Bank Sta=542.6,692.6
XS Rating Curve= 0 ,0
Exp/Cntr=0.3,0.1

Type RM Length L Ch R = 1 ,60840.1 ,705.3,706,706.7
XS GIS Cut Line= 2
     1552231.058      366361.388     1551490.766      367461.794
#Sta/Elev= 30
       0  729.18     9.8  723.43   117.9  651.27   127.7  645.81   137.5  642.93
   157.2  642.41     226  642.62   245.6  643.59   255.4  645.95   284.9  657.01
   294.7  660.14   304.6  661.89   520.7   669.5   638.6  678.02     727  685.53
   805.6  687.07   844.9     687   864.5  687.61   874.3  689.33   884.2  692.15
   913.6  704.23   933.3  710.49   952.9  715.64   972.6  720.08  1051.2  735.78
  1070.8  739.19  1159.2  752.93  1257.5  765.84    1287   770.5  1326.2  774.88
#Mann= 3 , 0 , 0
       0      .1       0   137.5    .045       0   245.6     .07       0
Bank Sta=137.5,245.6
XS Rating Curve= 0 ,0
Exp/Cntr=0.3,0.1

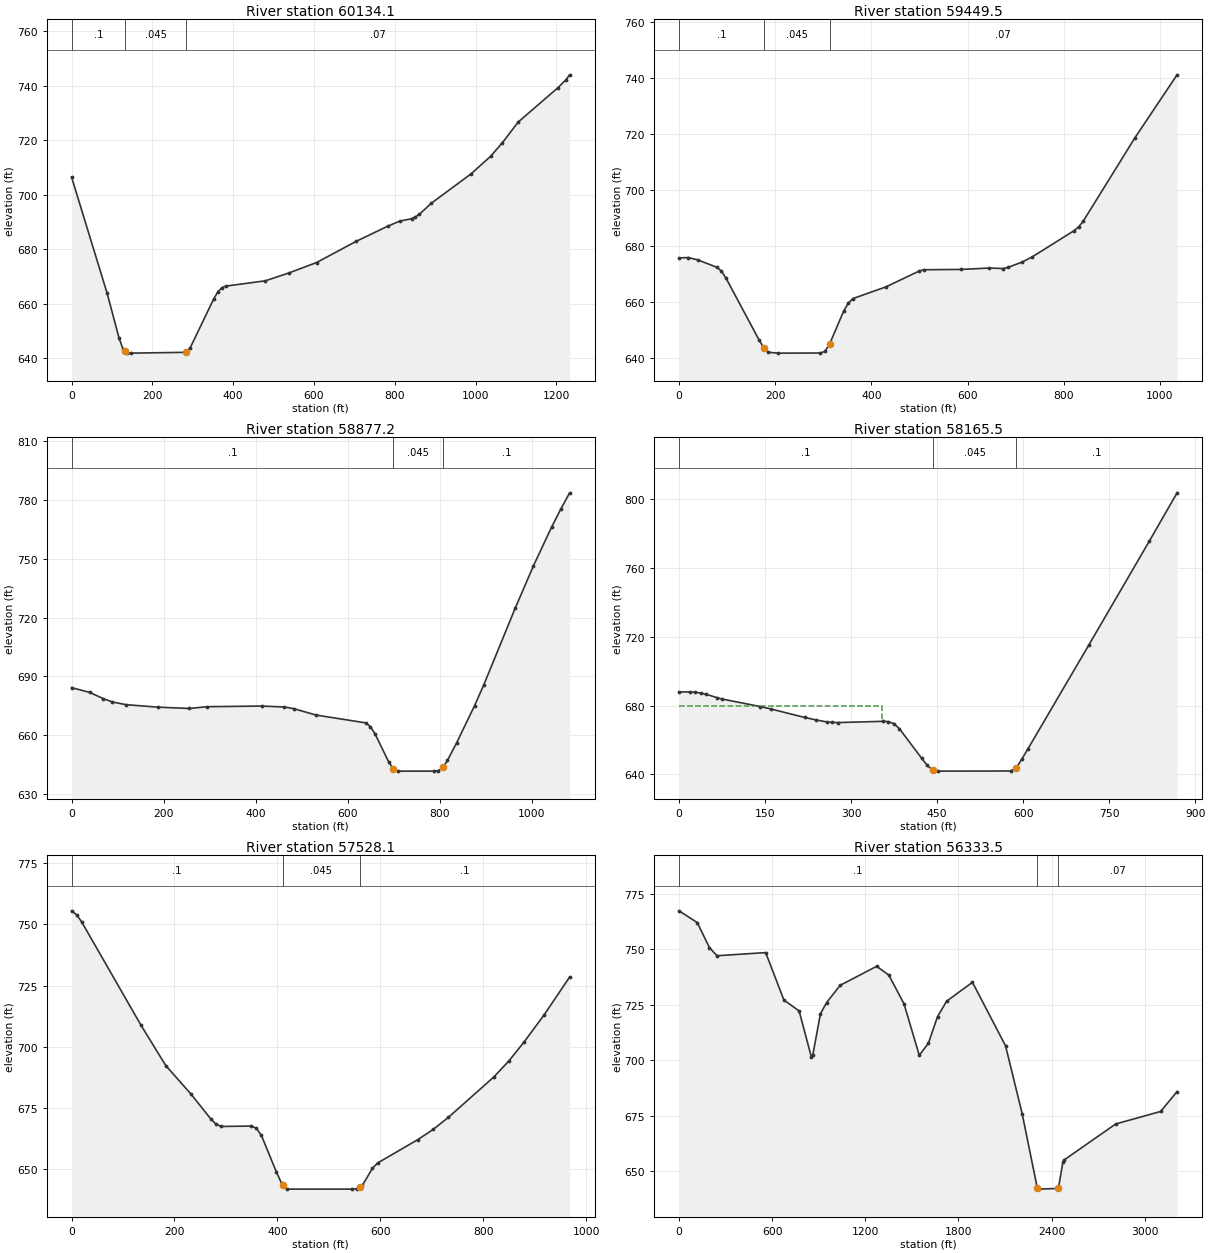
Type RM Length L Ch R = 1 ,60134.1 ,680.3,684.6,688.9
XS GIS Cut Line= 2
     1551638.176      365990.728     1550920.453      366993.044
#Sta/Elev= 30
       0  706.42    88.1  663.73   117.4  647.39   127.2  643.33   132.6642.5421
     137   641.9   146.8   641.8   282.6642.0948   293.5  643.72   352.2  661.81
     362  664.27   371.8   665.8   381.6   666.4   479.4  668.34   538.1  671.24
   606.6  675.07   704.4  682.84   782.7  688.41   812.1  690.25   841.4  691.15
   851.2  691.82     861  692.79   890.4  696.83   988.2  707.54  1037.1  714.04
  1066.5  719.07  1105.6  726.65  1203.4  739.18    1223  742.04  1232.8  743.97
#Mann= 3 , 0 , 0
       0      .1       0   132.6    .045       0   282.6     .07       0
Bank Sta=132.6,282.6
XS Rating Curve= 0 ,0
Exp/Cntr=0.3,0.1

Type RM Length L Ch R = 1 ,59449.5 ,538,572.3,606.5
XS GIS Cut Line= 3
     1551191.822      365531.785     1550723.766       365976.23
     1550354.957      366103.888
#Sta/Elev= 30
       0  675.74    19.6  675.86    39.1  675.03    78.2  672.44      88   671.1
    97.8   668.5   166.2  646.58     176  643.76   185.8  642.11   205.4   641.8
   293.4  641.84   303.2  642.39     313  644.98   342.3  656.75   352.1  659.63
   361.8  661.25   430.3  665.42   498.8  671.01   508.5  671.52   586.8  671.64
   645.4  672.13   674.7  671.95   684.5  672.38   713.8  674.29   733.3  675.98
   821.1  685.41   830.8  686.76   840.6  688.85   947.9  718.53  1035.7     741
#Mann= 3 , 0 , 0
       0      .1       0     176    .045       0     313     .07       0
Bank Sta=176,313
XS Rating Curve= 0 ,0
Exp/Cntr=0.3,0.1

Type RM Length L Ch R = 1 ,58877.2 ,694,711.7,729
XS GIS Cut Line= 3
     1551439.391      365705.138     1550785.746      365093.158
     1550665.954      364949.929
#Sta/Elev= 30
       0  684.32    39.4  681.89    68.9   678.7    88.6  677.04   118.1  675.64
     187  674.38   255.8   673.7   295.2  674.61   413.3  674.94   462.5  674.45
   482.2  673.63   531.4  670.35   639.6  666.36   649.4  664.35   659.3  660.84
   688.8  646.54   698.6  643.02   708.5   641.8   787.2   641.8     797  642.02
   806.9  643.67   816.7  647.28   836.4  656.13   875.7   675.2   895.4  685.64
   964.2  724.96  1003.5  746.35  1042.8  766.02  1062.5  775.05  1082.1  783.51
#Mann= 3 , 0 , 0
       0      .1       0   698.6    .045       0   806.9      .1       0
Bank Sta=698.6,806.9
XS Rating Curve= 0 ,0
Exp/Cntr=0.3,0.1

Type RM Length L Ch R = 1 ,58165.5 ,641.6,637.3,633.1
XS GIS Cut Line= 4
       1551569.6      365663.905     1551595.641      365525.016
       1551569.6      364991.162     1551543.558       364800.19
#Sta/Elev= 30
       0  687.87    18.8  687.92    28.3  687.72    37.7  687.26    47.1   686.6
    65.9  684.62    75.4  683.76   141.3  679.43   160.8  677.94     219  673.07
   238.5  671.64   257.9  670.45   267.6  670.14   277.4  670.08   355.1  670.79
   364.8  670.62   374.5   669.5   384.3   666.5   423.1  649.33   432.8  645.16
   442.6  642.29   443.5642.2445   452.3   641.8   578.6  641.88   588.3   643.7
     598  648.92   607.8  654.42   714.4  715.13   820.4  775.91   868.5  803.86
#Mann= 3 , 0 , 0
       0      .1       0   443.5    .045       0   588.3      .1       0
#XS Ineff= 2 , 0
          354.11  679.45
Permanent Ineff=
       F       F
Bank Sta=443.5,588.3
XS Rating Curve= 0 ,0
Exp/Cntr=0.3,0.1

Type RM Length L Ch R = 1 ,57528.1 ,1194.5,1194.7,1194.8
XS GIS Cut Line= 4
     1552301.371      365556.266     1552270.121      365327.099
     1552141.648      364792.377     1552013.176       364656.96
#Sta/Elev= 30
       0  755.59     9.6  754.02    19.3  751.18   134.9  708.82   183.1  692.32
   231.3  680.85   270.6  670.51   280.4  668.43   290.2  667.42   349.1  667.59
     359   666.7   368.8  663.81   398.2  648.74     408   644.2   410.1643.6909
   417.9   641.8   545.5   641.8   555.4  641.97   560.1642.6366   565.2  643.36
   584.8  650.33   594.6  652.46   673.2  662.09   702.7  666.21   732.1  671.11
   820.5  687.64     850  694.24   879.5     702   918.8  713.19   967.9  728.53
#Mann= 3 , 0 , 0
       0      .1       0   410.1    .045       0   560.1      .1       0
Bank Sta=410.1,560.1
XS Rating Curve= 0 ,0
Exp/Cntr=0.3,0.1

Type RM Length L Ch R = 1 ,56333.5 ,578.4,566.7,554.8
XS GIS Cut Line= 5
      1553872.71      367052.072     1553200.598      365306.175
     1553436.787      365104.877     1553290.954      364479.877
     1553065.259      364167.377
#Sta/Elev= 30
       0  767.33   117.5  762.04   195.9  750.74   244.9  747.07   558.3  748.49
   675.8  727.08   773.8  722.17   852.1  701.53   861.9  702.35   910.9  720.86
   950.1  725.87  1038.2  733.74  1273.3  742.31  1351.7  738.33  1449.6  725.34
  1547.6  702.17  1606.3  707.57  1665.1  719.57  1723.9  726.57  1890.2  735.09
  2103.6  706.42  2210.3  675.89  2307.5  642.47  2317.3   641.8  2443.7  642.12
  2472.8  653.91  2482.6  655.04  2813.2   671.2  3102.4  676.83  3208.4   685.8
#Mann= 3 , 0 , 0
       0      .1       0  2307.5    .045       0  2443.7     .07       0
Bank Sta=2307.5,2443.7
XS Rating Curve= 0 ,0
Exp/Cntr=0.3,0.1

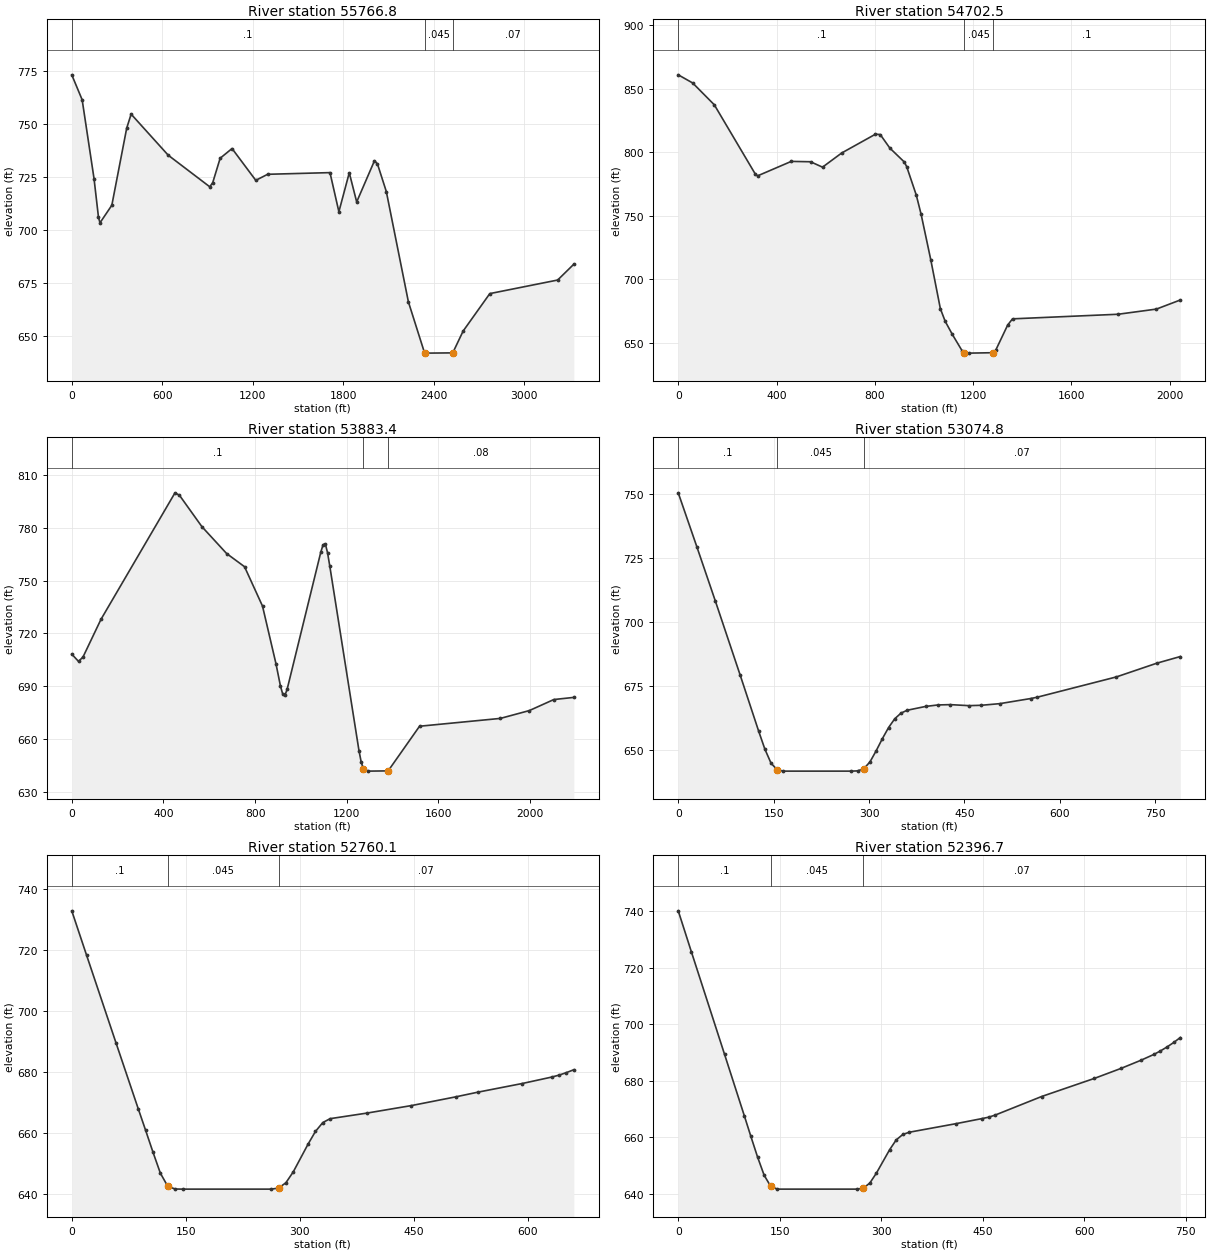
Type RM Length L Ch R = 1 ,55766.8 ,1088.4,1064.3,1040
XS GIS Cut Line= 5
     1554768.544       366892.35      1554218.47      364941.097
     1553974.982      364761.127     1553558.315      364316.683
     1553329.148       364000.71
#Sta/Elev= 30
       0  773.42    68.9  761.61   147.6  724.37   177.1  706.08     187  703.41
   265.7  711.74   364.1  748.14   393.6  754.83   639.7   735.4   915.2  720.46
   934.9  722.46   984.1  733.98  1062.9  738.56  1220.3  723.52    1299  726.38
  1712.4  727.17  1771.4  708.68  1840.3   727.1  1889.5   713.3  2007.6  732.82
  2027.3  731.27  2085.9  718.24  2232.4  666.04  2339.9  641.83  2349.7   641.8
  2526.6  641.92  2595.4  652.24  2772.3  669.95  3222.3  676.37  3329.6  683.87
#Mann= 3 , 0 , 0
       0      .1       0  2339.9    .045       0  2526.6     .07       0
Bank Sta=2339.9,2526.6
XS Rating Curve= 0 ,0
Exp/Cntr=0.3,0.1

Type RM Length L Ch R = 1 ,54702.5 ,837.3,819.1,800.9
XS GIS Cut Line= 3
      1555437.47      363454.609     1553845.803      363867.109
     1553447.204      363886.127
#Sta/Elev= 30
       0  861.08    58.7  854.67   146.8  837.46   313.2  783.03     323  781.48
     460  792.87   538.3  792.59   587.2  788.33   665.5  799.53   802.6   814.3
   822.1  814.03   861.3  803.34     920   792.4   929.8  788.72   968.9  766.25
   988.5  751.13  1027.7  715.39  1066.8  676.82  1086.4  666.87  1115.7  656.48
  1154.9  643.76  1164.7  642.18  1184.2   641.8  1282.1  642.14  1291.9  644.04
  1340.8  663.95  1360.4  668.81  1790.2  672.43    1946   676.5  2043.3  683.67
#Mann= 3 , 0 , 0
       0      .1       0  1164.7    .045       0  1282.1      .1       0
Bank Sta=1164.7,1282.1
XS Rating Curve= 0 ,0
Exp/Cntr=0.3,0.1

Type RM Length L Ch R = 1 ,53883.4 ,825.3,808.6,791.9
XS GIS Cut Line= 3
     1554511.599      361927.072     1553579.148      363559.738
     1553318.732      363729.877
#Sta/Elev= 30
       0  708.23    29.4  704.11      49  706.59   127.3  727.98   450.5  799.97
     470  798.58     568  780.72   675.7  765.46     754  757.95   832.4  735.57
   891.1  702.84   910.7  690.13   920.5   685.6   930.3  684.72   940.1  688.35
    1087  766.32  1096.8  770.44  1106.6  770.94  1116.4  765.83  1126.2  758.18
  1253.4   653.4  1263.2  646.81    1273   642.9  1292.6   641.7  1380.8  641.84
  1517.8  667.23  1870.4  671.68  1996.8  676.13  2103.8  682.41  2191.2  683.63
#Mann= 3 , 0 , 0
       0      .1       0    1273    .045       0  1380.8     .08       0
Bank Sta=1273,1380.8
XS Rating Curve= 0 ,0
Exp/Cntr=0.3,0.1

Type RM Length L Ch R = 1 ,53074.8 ,313.7,314.7,315.7
XS GIS Cut Line= 3
     1553016.648      362865.294     1553159.009      363511.127
     1553131.232      363636.127
#Sta/Elev= 30
       0  750.31    29.2   729.3    58.4  708.05    97.3  679.24   126.4  657.34
   136.2  650.29   145.9  644.81   155.6  642.22   165.3   641.7   272.3   641.7
     282   641.8   291.8  642.64   301.5  645.31   311.2  649.64   320.9  654.34
   330.7   658.7   340.4  662.13   350.1  664.31   359.8  665.45     389  666.95
   408.5  667.53   427.9  667.65   457.1  667.25   476.6   667.4   505.7  668.04
   554.4  670.04   564.1  670.53   688.8  678.46   752.8  683.85   789.4  686.42
#Mann= 3 , 0 , 0
       0      .1       0   155.6    .045       0   291.8     .07       0
Bank Sta=155.6,291.8
XS Rating Curve= 0 ,0
Exp/Cntr=0.3,0.1

Type RM Length L Ch R = 1 ,52760.1 ,364.3,363.4,362.5
XS GIS Cut Line= 2
     1552720.408      362935.485     1552833.256      363586.526
#Sta/Elev= 27
       0  732.73    19.4  718.28    58.3  689.48    87.4  668.05    97.2  660.93
   106.9  653.78   116.6  646.92   126.3  642.64     136  641.74   145.8   641.7
   262.4   641.7   272.1  642.04   281.8  643.78   291.5  647.34   310.9  656.38
   320.7  660.56   330.4  663.48   340.1  664.75   388.7  666.58     447  669.03
   505.3  671.88   534.4  673.41   592.7  676.24   631.6  678.35   641.3  678.99
     651  679.81   660.8  680.76
#Mann= 3 , 0 , 0
       0      .1       0   126.3    .045       0   272.1     .07       0
Bank Sta=126.3,272.1
XS Rating Curve= 0 ,0
Exp/Cntr=0.3,0.1

Type RM Length L Ch R = 1 ,52396.7 ,553.1,552.9,552.5
XS GIS Cut Line= 2
     1552353.454      362997.238     1552509.704      363722.933
#Sta/Elev= 30
       0  740.09    19.5  725.55    68.4  689.41    97.7  667.64   107.4  660.33
   117.2  653.11     127  646.62   136.7  642.68   146.5   641.7   263.7   641.7
   273.5  642.02   283.3  643.86     293  647.37   312.6  655.66   322.3  659.11
   332.1  661.04   341.9  661.83   410.2  664.82   449.3  666.65   459.1  667.14
   468.8   667.9   537.2  674.44   615.4  680.86   654.4  684.36   683.7  687.22
   703.3  689.33     713  690.57   722.8  691.98   732.6  693.55   742.3   695.3
#Mann= 3 , 0 , 0
       0      .1       0   136.7    .045       0   273.5     .07       0
Bank Sta=136.7,273.5
XS Rating Curve= 0 ,0
Exp/Cntr=0.3,0.1

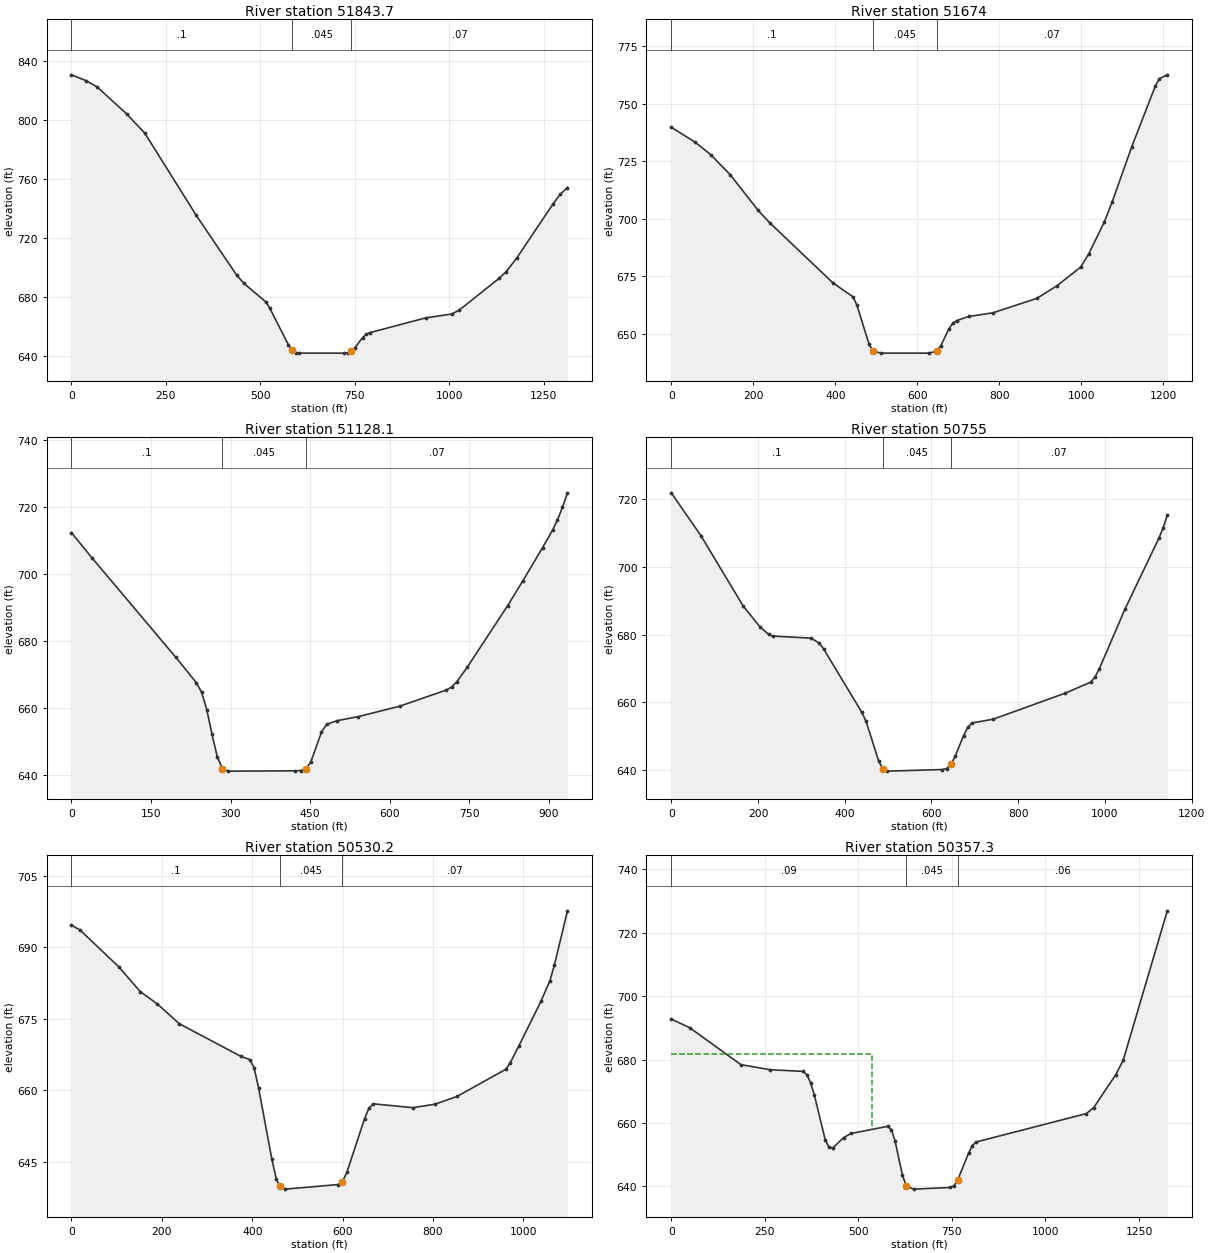
Type RM Length L Ch R = 1 ,51843.7 ,171.6,169.7,167.4
XS GIS Cut Line= 4
     1552206.044      362809.016     1551815.259      363129.183
     1551940.259      363674.322     1552089.565      363872.238
#Sta/Elev= 30
       0  830.84    38.9  826.86      68  822.61   145.7  804.37   194.3   791.1
   330.3   735.3   437.2  694.66   456.6  689.03     515  676.35   524.8  672.22
   573.9  647.44   583.7  643.74   593.5  641.98   603.3   641.7   721.1   641.7
   730.9  641.87   740.7  642.92   750.5  645.52   770.1  652.18   779.9   654.5
   789.7  655.63   936.9  665.63  1005.6  668.26  1025.2  670.77  1131.2  692.46
  1150.3  697.08  1178.9   706.6  1274.2  743.09  1293.3  749.67  1312.4  754.24
#Mann= 3 , 0 , 0
       0      .1       0   583.7    .045       0   740.7     .07       0
Bank Sta=583.7,740.7
XS Rating Curve= 0 ,0
Exp/Cntr=0.3,0.1

Type RM Length L Ch R = 1 ,51674   ,543.5,545.9,548.9
XS GIS Cut Line= 4
     1551351.877      362857.627     1551617.343      363108.349
     1551808.315      363691.683     1551832.621      363920.849
#Sta/Elev= 30
       0  739.81    57.7   733.4    96.1  727.94   144.1  719.12   211.4  703.82
   240.2  698.29   394.4   672.2   443.1  666.17   452.8  662.52   482.1  645.66
   491.8  642.64   511.3   641.7   628.2   641.7   647.7   642.6   657.4  644.96
   676.9  652.26   686.7  654.73   696.4  655.86   725.6  657.64   784.1   659.2
   891.3  665.48     940   670.9   998.2  679.06  1017.4  684.62  1055.8  698.62
    1075  707.33    1123  731.44  1180.6  757.87  1190.2  760.92  1209.4  762.59
#Mann= 3 , 0 , 0
       0      .1       0   491.8    .045       0   647.7     .07       0
Bank Sta=491.8,647.7
XS Rating Curve= 0 ,0
Exp/Cntr=0.3,0.1

Type RM Length L Ch R = 1 ,51128.1 ,374.5,373,371.5
XS GIS Cut Line= 4
     1551152.065      362983.349     1551106.926      363174.322
     1551214.565      363733.349     1551287.482      363886.127
#Sta/Elev= 30
       0  712.45    39.2  704.84   196.2  675.32   235.5  667.64   245.3  664.76
   255.1  659.56   264.9  652.25   274.8  645.51   284.6  641.96   294.4  641.24
     422  641.33   431.8  641.41   441.6  641.74   451.4  644.11   471.1  652.86
   480.9  655.25   500.5   656.3   539.8   657.5   618.3  660.62   706.6  665.46
   716.4  666.36   726.3  667.94   745.9  672.27     822  690.65   850.2  697.94
   887.8  707.98   906.6  713.19     916  716.27   925.4  720.07   934.8  724.36
#Mann= 3 , 0 , 0
       0      .1       0   284.6    .045       0   441.6     .07       0
Bank Sta=284.6,441.6
XS Rating Curve= 0 ,0
Exp/Cntr=0.3,0.1

Type RM Length L Ch R = 1 ,50755   ,222.9,224.8,226.8
XS GIS Cut Line= 3
     1550874.287      362834.044     1550704.148      363118.766
     1550912.482      363903.488
#Sta/Elev= 30
       0  721.85    68.3  709.22   165.8  688.46   204.9  682.25   224.4   680.1
   234.1  679.58   321.9  678.98   341.5  677.51   351.2  675.81   439.3  657.09
   449.1  654.46   478.4  642.64   488.2  640.37     498  639.73   625.1   640.2
   634.9  640.49   644.7  641.72   654.5  644.09     674  650.22   683.8  652.63
   693.6  653.94   742.5  655.06   908.8  662.76   967.5  666.01   977.3  667.58
   987.1  669.98  1045.8  687.47    1124   708.4  1133.8   711.4  1143.6  715.26
#Mann= 3 , 0 , 0
       0      .1       0   488.2    .045       0   644.7     .07       0
Bank Sta=488.2,644.7
XS Rating Curve= 0 ,0
Exp/Cntr=0.3,0.1

Type RM Length L Ch R = 1 ,50530.2 ,173.1,172.9,172.7
XS GIS Cut Line= 3
     1550481.926      362834.044     1550488.871      363052.794
     1550645.121      363917.377
#Sta/Elev= 30
       0  694.68      19  693.65   104.7  685.93   152.2  680.73   190.3  678.12
   238.4  674.01     375  667.14   394.6  666.47   404.3  664.69   414.1  660.49
   443.4  645.55   453.2  641.43   460.8639.9962   472.7   639.3   589.8  640.26
   599.6  640.88   609.3  642.82   648.4  654.06   658.2  656.29   667.9  657.19
   755.8  656.39   804.6  657.12   853.4  658.76   960.8  664.43   970.5  665.76
   990.1  669.39  1038.9  678.74  1058.4     683  1068.2  686.23  1097.4  697.68
#Mann= 3 , 0 , 0
       0      .1       0   460.8    .045       0   599.6     .07       0
Bank Sta=460.8,599.6
XS Rating Curve= 0 ,0
Exp/Cntr=0.3,0.1

Type RM Length L Ch R = 1 ,50357.3 ,188.8,186.3,183.9
XS GIS Cut Line= 3
     1550171.683      362734.883     1550310.919       363058.87
     1550493.211      364014.599
#Sta/Elev= 30
       0  692.78      49  690.07   186.1   678.4   264.5  676.79   352.6  676.27
   362.5  675.23   372.3  672.72   382.1  668.97   411.6  654.64   421.4  652.37
   431.3  652.06   460.8  655.39   480.4  656.67   578.7  658.93   588.5  657.85
   598.3  654.18     618  643.44   627.8  640.23   647.5  639.11   745.8  639.63
   755.6  640.17   765.4  641.97   794.9  650.54   804.7  652.87   814.6  653.98
  1109.4  662.95    1129  664.84    1188  675.24  1207.7  679.74  1325.6  726.94
#Mann= 3 , 0 , 0
       0     .09       0   627.8    .045       0   765.4     .06       0
#XS Ineff= 2 , 0
           535.9  681.66
Permanent Ineff=
       F       F
Bank Sta=627.8,765.4
XS Rating Curve= 0 ,0
Exp/Cntr=0.3,0.1

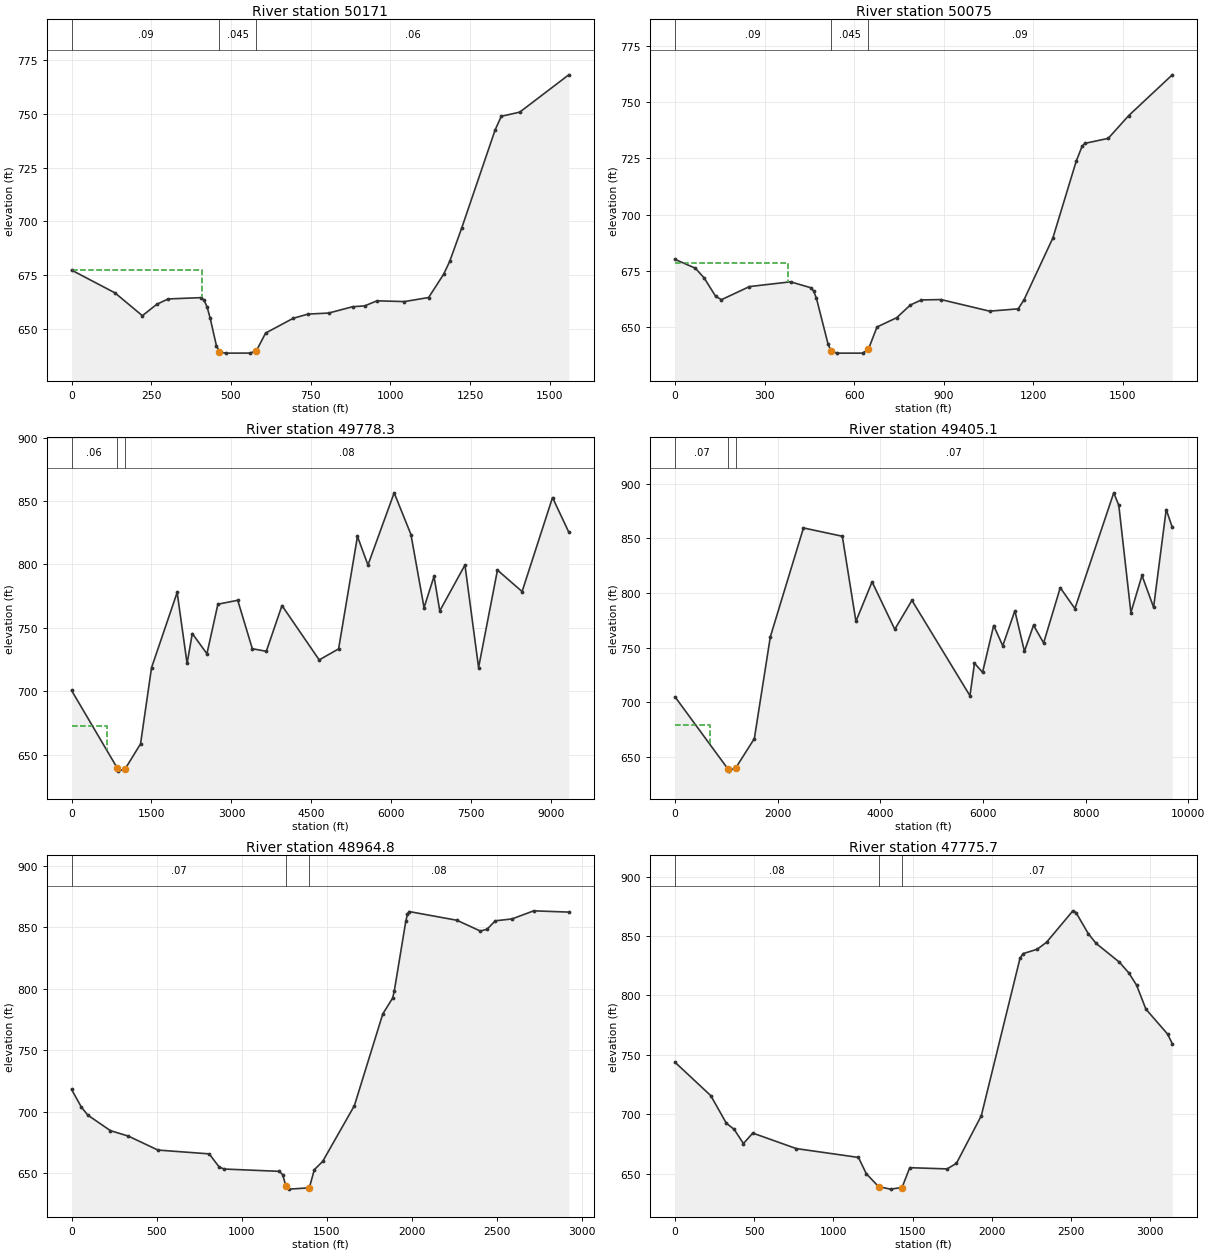
Type RM Length L Ch R = 1 ,50171   ,96.1,96.1,96.1
XS GIS Cut Line= 6
     1550172.898      362931.266     1550133.836      363230.745
     1550251.023      363735.953     1550038.414      363922.592
     1550062.066      364052.306     1550231.389        364309.4
#Sta/Elev= 30
       0  677.29   136.2  666.69   222.3  656.04   267.3  661.34   303.2  663.85
   406.3  664.46   415.9  663.28   425.6  659.98   435.2  654.74   454.5  642.07
   464.2  639.16   483.5   638.6   560.7  638.62     580   639.7   608.9  647.95
   695.8  654.86   742.3   656.8   806.8  657.27   881.7  660.22   919.9  660.62
   958.3  662.97  1044.3  662.62  1120.4  664.52  1167.4  675.36  1186.3   681.3
    1224  696.84  1329.2   742.7  1348.4  748.96  1406.1  750.89    1560  768.28
#Mann= 3 , 0 , 0
       0     .09       0   464.2    .045       0     580     .06       0
#XS Ineff= 2 , 0
          408.79  677.46
Permanent Ineff=
       F       F
Bank Sta=464.2,580
XS Rating Curve= 0 ,0
Exp/Cntr=0.3,0.1

Type RM Length L Ch R = 1 ,50075   ,294.1,296.7,298.9
XS GIS Cut Line= 6
     1550066.127      362910.433     1550027.065      363209.912
     1550144.252       363715.12     1549931.643      363901.758
     1549957.719      364044.762     1550182.778      364375.372
#Sta/Elev= 30
       0   680.2    68.1  676.28    97.3     672   136.2  663.78   155.6  662.32
   249.3  668.13     387  670.24   454.5  667.62   464.2  666.17   473.8  662.86
   512.4  642.72   522.1  639.61   541.4   638.6   628.2   638.6   647.5  640.23
   676.5   650.2   742.3   654.3   788.4  659.96   825.2   662.2   891.1  662.36
  1053.8  657.22  1149.4  658.25  1168.8  662.21  1265.7  689.71  1343.8  723.73
  1363.3  730.31    1373  731.68    1451  733.88  1519.3  743.94  1665.6  762.08
#Mann= 3 , 0 , 0
       0     .09       0   522.1    .045       0   647.5     .09       0
#XS Ineff= 2 , 0
          377.86  678.57
Permanent Ineff=
       F       F
Bank Sta=522.1,647.5
XS Rating Curve= 0 ,0
Exp/Cntr=0.3,0.1

Type RM Length L Ch R = 1 ,49778.3 ,373,373.2,373.7
XS GIS Cut Line= 6
     1549757.621        362682.8     1549745.815      363155.224
     1549920.294      364043.245     1550425.688      364754.843
     1550065.185      366222.198     1549991.959       371769.74
#Sta/Elev= 30
       0  700.62   854.5639.5969     872  636.92  1004.5638.5561  1294.9  658.44
  1501.2  718.52  1981.7  777.89    2168  721.87  2266.1  745.46  2540.4  729.51
  2746.2  768.62  3118.4  771.69    3392  733.49  3654.6  731.45  3948.3  767.54
  4646.7  724.65  5010.7  733.35  5364.8   822.1  5561.6  799.53  6053.4  856.47
  6368.2  823.58  6614.1  765.86    6801  790.57  6909.2  763.33  7381.4  799.51
  7637.2  718.63  7991.3  795.51  8453.6  778.58  9024.2  852.74  9329.1   825.5
#Mann= 3 , 0 , 0
       0     .06       0   854.5    .045       0  1004.5     .08       0
#XS Ineff= 2 , 0
          665.48  672.91
Permanent Ineff=
       F       F
Bank Sta=854.5,1004.5
XS Rating Curve= 0 ,0
Exp/Cntr=0.3,0.1

Type RM Length L Ch R = 1 ,49405.1 ,432,440.3,448.2
XS GIS Cut Line= 6
     1549559.704      362617.695     1549391.648      363222.933
     1549550.502      364126.578     1549103.929      364546.874
     1548738.262      366508.635      1546567.48       371600.47
#Sta/Elev= 30
       0  704.95  1028.3  639.06  1047.8   636.9  1185.5640.0134  1545.6  666.71
  1857.1  759.94    2503  859.66  3259.9  852.04  3525.3  774.12  3839.9  810.27
  4282.2  766.81  4616.5  793.32  5747.2  705.95  5835.7  735.73    5993  727.42
  6209.3  770.29  6386.2  751.71  6622.2  783.74    6809  746.63    6986  770.53
  7182.6  754.31    7507   804.9  7792.2  785.79  8549.2  891.82  8647.5  880.44
  8883.5  782.13  9099.8   816.1  9325.9  786.96  9571.7  876.54  9689.7  860.26
#Mann= 3 , 0 , 0
       0     .07       0  1028.3    .045       0  1185.5     .07       0
#XS Ineff= 2 , 0
          681.85  679.05
Permanent Ineff=
       F       F
Bank Sta=1028.3,1185.5
XS Rating Curve= 0 ,0
Exp/Cntr=0.3,0.1

Type RM Length L Ch R = 1 ,48964.8 ,1180.9,1189.1,1197.5
XS GIS Cut Line= 6
     1549500.242      362563.008      1549465.52      362788.702
       1549161.7      363083.841     1548944.687      364260.057
     1548949.027      364568.216     1548909.964      365332.105
#Sta/Elev= 30
       0   718.1    57.1  703.84    95.2  697.18   228.4  684.51   334.2  680.04
   507.5   668.7   808.8   665.6   867.6  654.84     897  653.25  1220.5  651.38
  1240.2  648.73  1259.8  639.22  1279.4   636.9    1397  637.96  1426.4  652.76
  1475.4  659.45  1661.7  704.85  1828.4  779.48  1886.5  792.43  1896.1  798.15
  1963.6  854.82  1973.2  860.47  1982.8  862.84    2264  855.74  2401.3  846.99
  2440.6   848.4  2489.6  855.29  2587.6  856.82  2715.1  863.42  2921.1  862.39
#Mann= 3 , 0 , 0
       0     .07       0  1259.8    .045       0    1397     .08       0
Bank Sta=1259.8,1397
XS Rating Curve= 0 ,0
Exp/Cntr=0.3,0.1

Type RM Length L Ch R = 1 ,47775.7 ,977.2,981.4,985.7
XS GIS Cut Line= 3
     1548626.544      362251.087     1547621.264      363890.619
     1547303.627      365063.587
#Sta/Elev= 30
       0  743.74   225.7  715.62   323.8  692.41   372.9  687.29   431.7  675.29
   490.6   684.1   765.4  671.05  1157.8  663.59  1206.9  649.93  1285.4  638.93
  1360.1   636.9  1432.6  638.25  1481.6  654.96  1717.1  653.93    1776  658.59
    1933  698.69    2178  831.64  2197.6  835.28  2285.8   838.9  2344.6  844.78
  2511.2  871.28  2530.8  869.84  2609.2  851.86  2658.2  843.79  2805.2  827.99
    2864  819.01    2913  808.75  2971.8  788.51    3109  767.48  3138.4  759.44
#Mann= 3 , 0 , 0
       0     .08       0  1285.4    .045       0  1432.6     .07       0
Bank Sta=1285.4,1432.6
XS Rating Curve= 0 ,0
Exp/Cntr=0.3,0.1