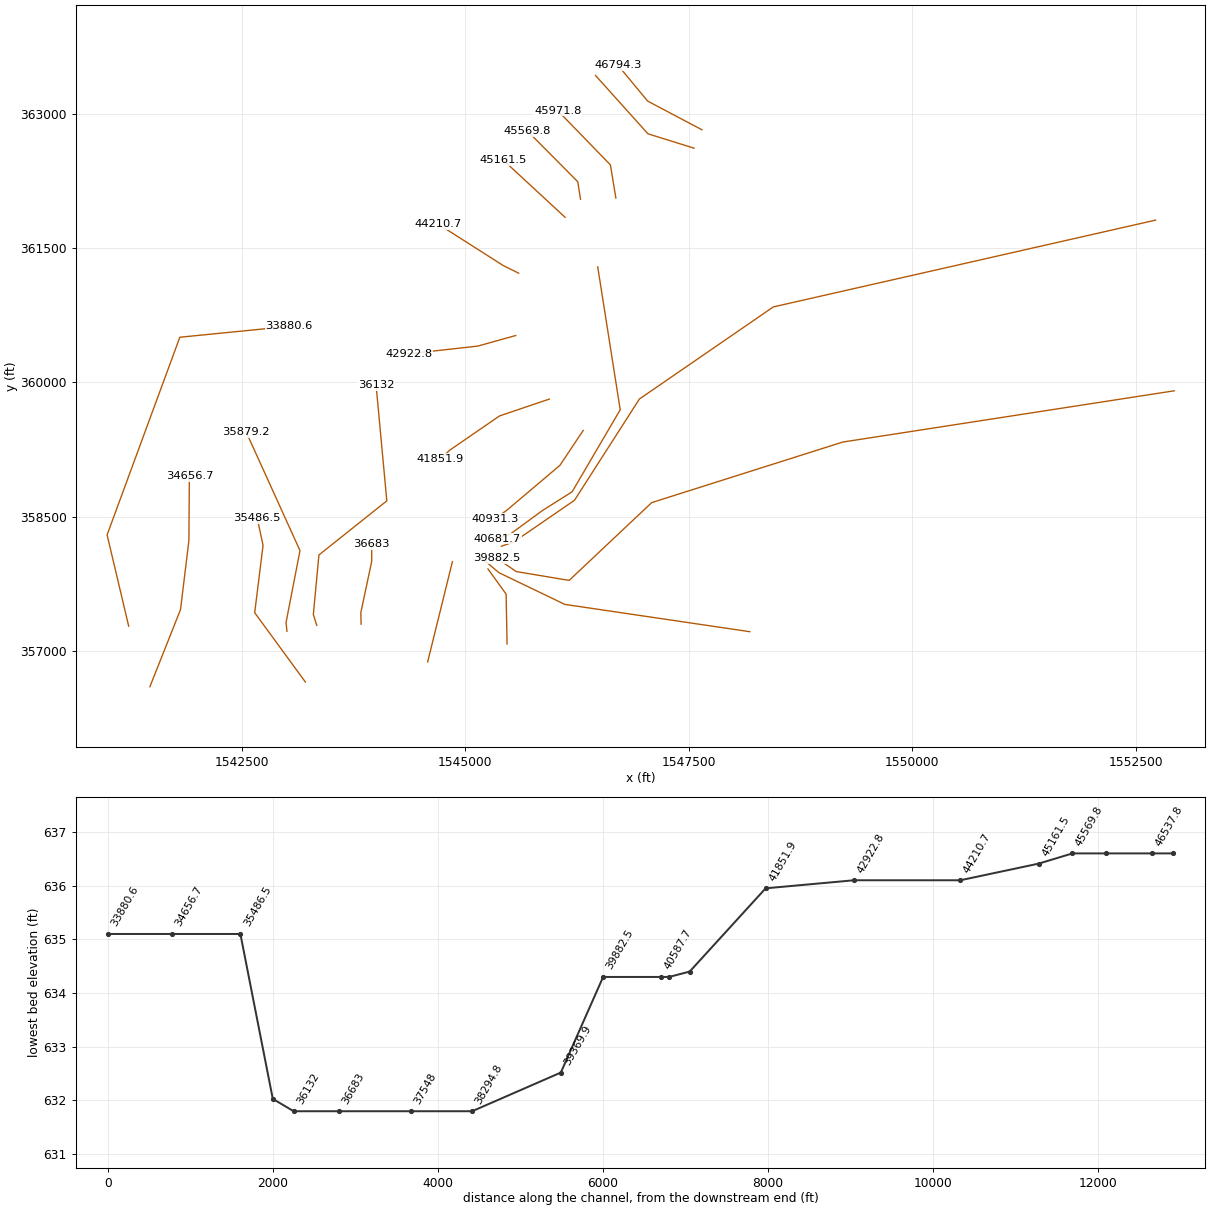
HEC-RAS study MDISLCRK1.prj: MDISLCRK1

--- MDISLCRK1.g01 (geometry) --- (continued)

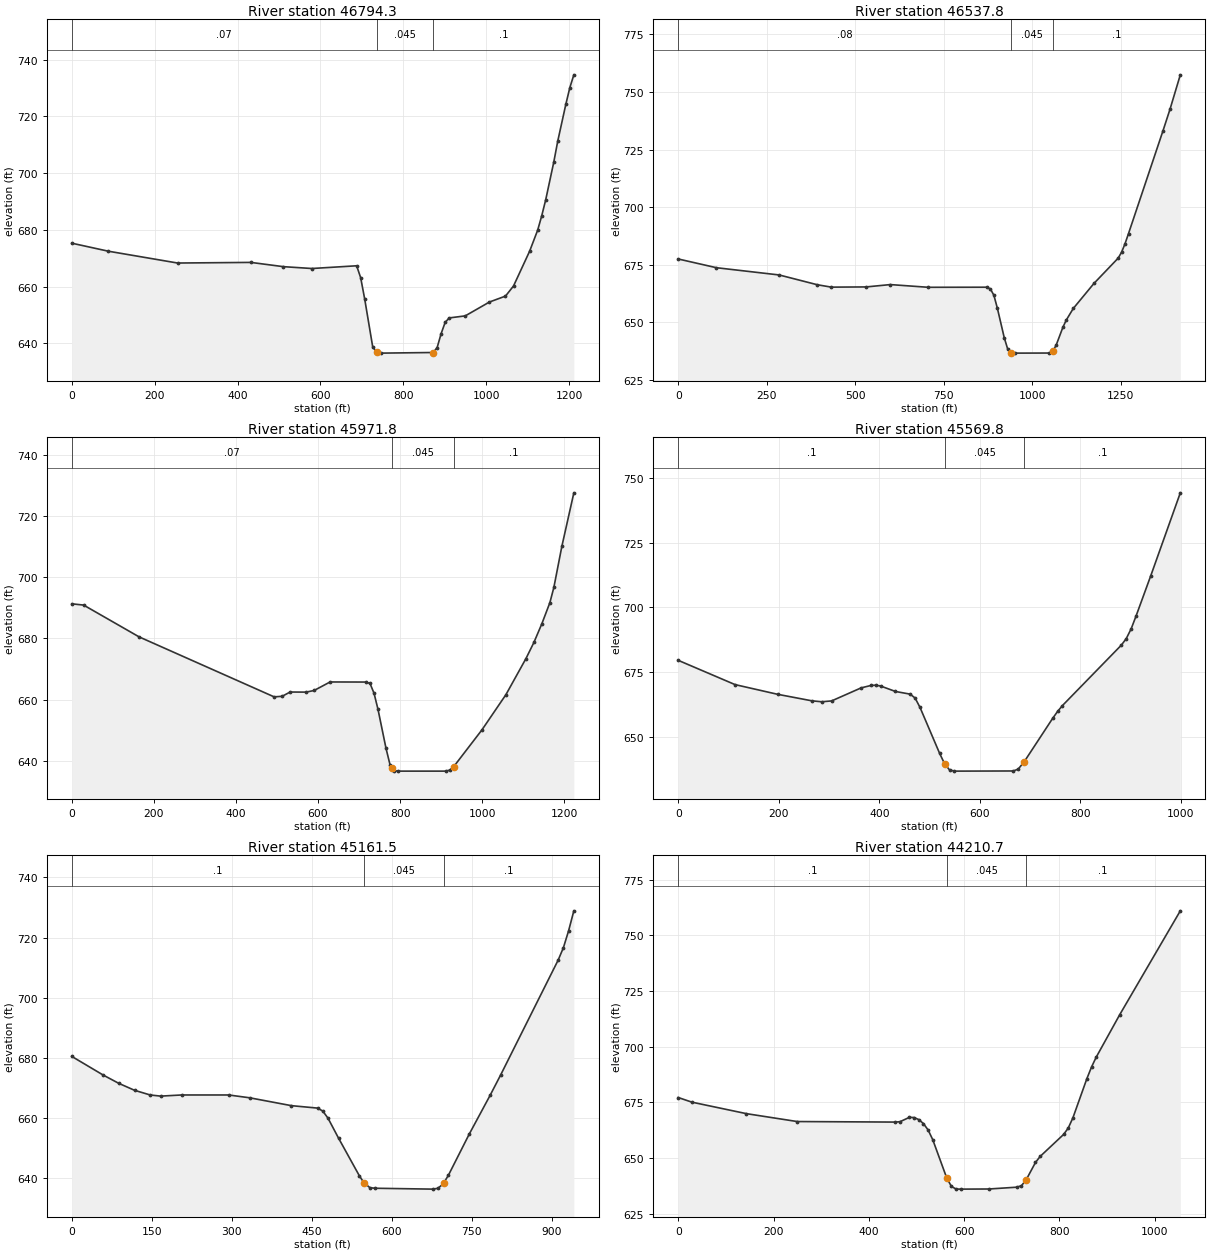
Type RM Length L Ch R = 1 ,46794.3 ,256.6,256.5,256.3
XS GIS Cut Line= 3
     1547646.624      362826.978     1547038.985      363148.158
     1546704.783      363551.804
#Sta/Elev= 30
       0  675.33    88.4   672.5   255.3  668.34     432  668.56   510.6  667.06
   579.3  666.41   687.3  667.37     697  663.17   706.7  655.67   726.1  638.75
   735.8  636.94   745.5   636.6   871.7  636.82   881.4   638.5   891.1  643.46
   900.8  647.42   910.5     649   949.3  649.72  1007.6   654.6  1046.4  656.69
  1065.8  660.26  1104.6   672.5    1124  679.91  1133.7  684.91  1143.4  690.61
  1162.8  703.83  1172.5  711.31  1191.9  724.21  1201.6  730.12  1211.3  734.64
#Mann= 3 , 0 , 0
       0     .07       0   735.8    .045       0   871.7      .1       0
Bank Sta=735.8,871.7
XS Rating Curve= 0 ,0
Exp/Cntr=0.3,0.1

Type RM Length L Ch R = 1 ,46537.8 ,565.1,566,566.9
XS GIS Cut Line= 3
     1547558.836      362620.878      1547042.69       362781.96
     1546455.884      363434.738
#Sta/Elev= 30
       0  677.47   108.1  673.68   285.1  670.54   393.2  666.28   432.6  665.25
   530.9  665.34   599.2  666.36   706.5  665.18   872.3  665.22     882  664.44
   891.8  661.72   901.6  656.11   921.1  643.28   930.8  638.38   940.6  636.62
   950.3   636.6  1047.8  636.64  1057.6  637.35  1067.4  639.92  1086.9  647.88
  1096.6  651.03  1116.1  655.99  1174.6  666.88  1242.9  677.84  1252.7  680.45
  1262.4  684.14  1272.2  688.53  1369.7   733.2  1389.2   742.4  1418.5  757.43
#Mann= 3 , 0 , 0
       0     .08       0   940.6    .045       0  1057.6      .1       0
Bank Sta=940.6,1057.6
XS Rating Curve= 0 ,0
Exp/Cntr=0.3,0.1

Type RM Length L Ch R = 1 ,45971.8 ,401.8,402,402.2
XS GIS Cut Line= 3
     1546683.836      362063.587     1546622.551      362434.738
     1546032.273      363042.377
#Sta/Elev= 30
       0   691.3    28.9  690.88     164  680.49     493  660.88   512.5  661.06
     532  662.46   570.9  662.43   590.4  662.96   629.4  665.75     717  665.72
   726.7  665.25   736.5  662.05   746.2  656.75   765.7  644.02   775.4   638.7
   780.8637.6144   785.1  636.75   794.9   636.6   911.7   636.6   921.5  636.95
   930.8638.1005   999.4  650.09  1057.8   661.6  1106.5  673.37    1126  678.67
  1145.4  684.79  1164.9  691.67  1174.6  696.65  1194.1  710.09  1223.3  727.58
#Mann= 3 , 0 , 0
       0     .07       0   780.8    .045       0   930.8      .1       0
Bank Sta=780.8,930.8
XS Rating Curve= 0 ,0
Exp/Cntr=0.3,0.1

Type RM Length L Ch R = 1 ,45569.8 ,407.4,408.3,409.3
XS GIS Cut Line= 3
     1546288.117      362050.068     1546257.735      362245.381
     1545693.499      362813.957
#Sta/Elev= 30
       0  679.52     113  670.12   197.7  666.36     266  663.83   285.6  663.47
   305.1   663.8   363.7  668.84   383.3  669.79     393  669.89   402.8  669.55
   432.1  667.46   461.4  666.42   471.2   664.9     481  661.25     520  643.45
   529.8  639.47   539.6  637.08   549.3   636.6   666.6  636.66   676.3  637.39
   688.4640.3023   744.7  657.02   754.5   659.7   764.2  661.99   881.5  685.43
   891.2  687.95     901  691.76   910.8  696.75   940.1  712.38   998.7  744.41
#Mann= 3 , 0 , 0
       0      .1       0   529.8    .045       0   688.4      .1       0
Bank Sta=529.8,688.4
XS Rating Curve= 0 ,0
Exp/Cntr=0.3,0.1

Type RM Length L Ch R = 1 ,45161.5 ,946.7,950.8,954.8
XS GIS Cut Line= 2
     1546115.607      361847.933     1545424.634      362486.822
#Sta/Elev= 30
       0  680.52    58.8  674.33    88.2  671.56   117.6  669.26     147   667.7
   166.6  667.32   205.9   667.7   294.1   667.7   333.3  666.77   411.7  664.15
   460.7  663.34   470.5  662.36   480.3  659.98     500  653.37   539.2   640.8
   547.5 638.581   558.8  636.89   568.6   636.7   676.4  636.41   686.2  636.68
     696  638.11   697.5638.5463   705.8  640.96     745  654.69   784.2   667.6
   803.8  674.32   911.7  712.53   921.5  716.63   931.3  722.28   941.1   728.9
#Mann= 3 , 0 , 0
       0      .1       0   547.5    .045       0   697.5      .1       0
Bank Sta=547.5,697.5
XS Rating Curve= 0 ,0
Exp/Cntr=0.3,0.1

Type RM Length L Ch R = 1 ,44210.7 ,1272.6,1287.9,1303.2
XS GIS Cut Line= 3
     1545596.403      361222.302     1545425.221      361307.033
      1544697.31      361770.438
#Sta/Elev= 30
       0   677.2    28.6  675.12   143.2  669.96   249.8  666.42   455.8  666.18
   465.6  666.36   485.2   668.3     495  668.22   504.8  667.31   514.6  665.53
   524.4  662.68   534.2  658.31   563.6   641.1   573.4  637.32   583.2  636.13
     593   636.1   652.2  636.16   710.7  636.97   720.5  637.65   730.3  640.26
   749.9  648.07   759.7  650.77   808.8  660.61   818.6  663.48   828.4  668.06
   857.8  685.68   867.6  690.92   877.4  695.32   926.4  714.24  1053.9  760.96
#Mann= 3 , 0 , 0
       0      .1       0   563.6    .045       0   730.3      .1       0
Bank Sta=563.6,730.3
XS Rating Curve= 0 ,0
Exp/Cntr=0.3,0.1

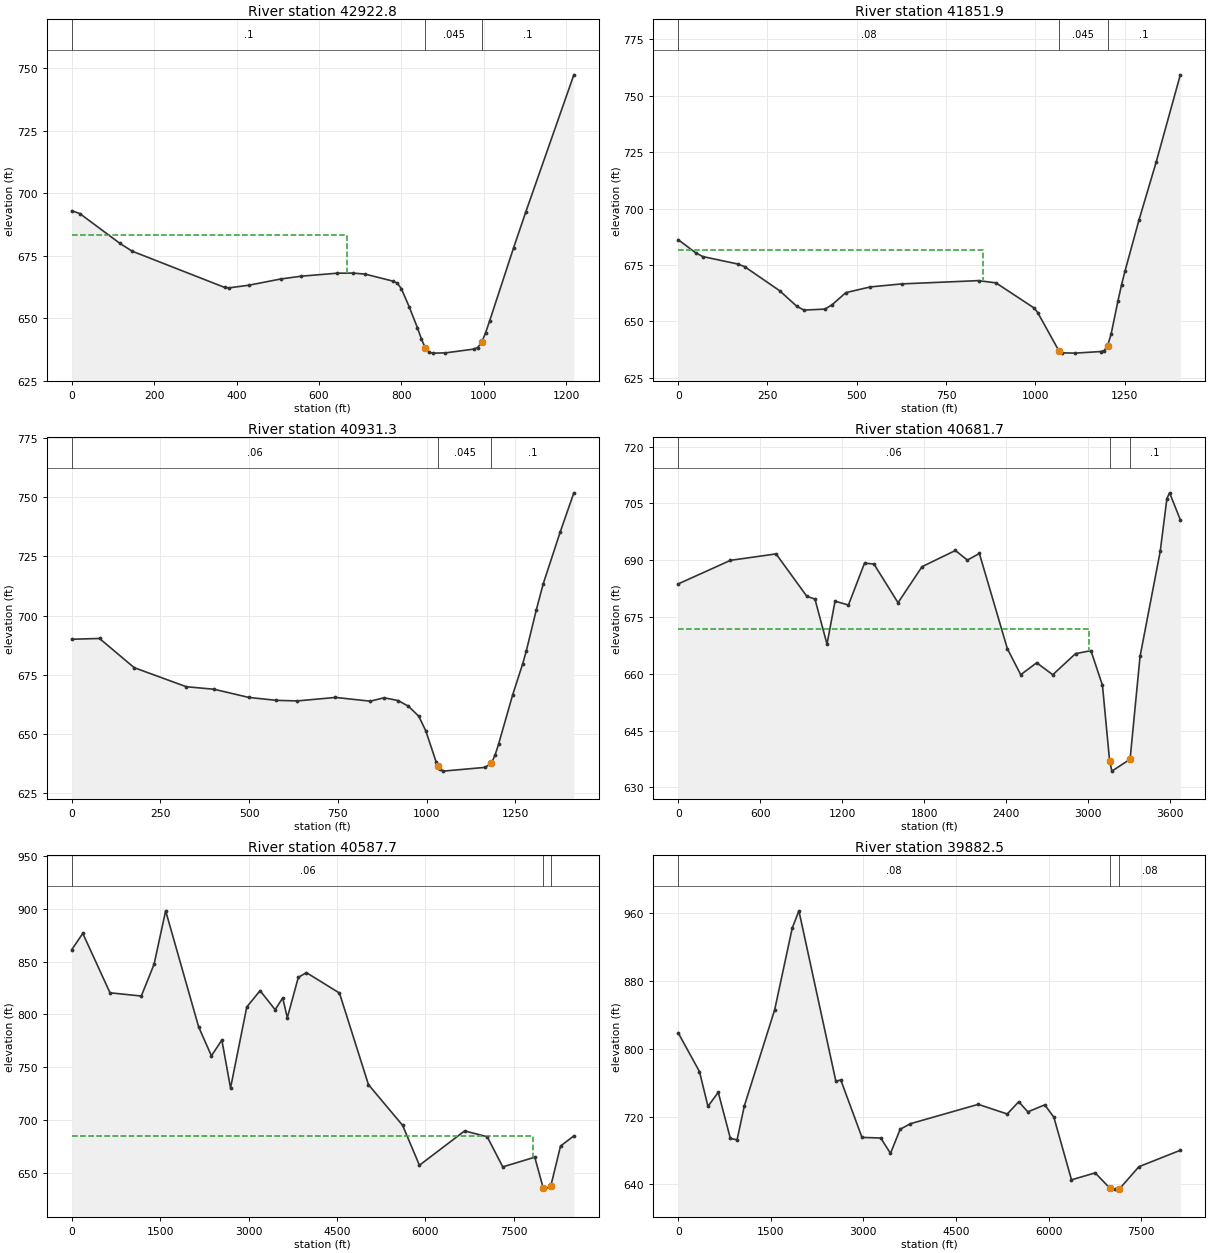
Type RM Length L Ch R = 1 ,42922.8 ,1059.8,1070.9,1081.9
XS GIS Cut Line= 3
     1545563.523      360525.016     1545139.912       360406.96
     1544365.607      360320.155
#Sta/Elev= 30
       0  693.01    19.5  691.89   117.3  679.93   146.6  676.86   371.4  662.35
   381.1  662.18     430  663.25   507.9  665.76   556.6  666.85   644.3  668.06
   683.2   668.1   712.5  667.68   780.6  664.85   790.4  664.04   800.1  661.88
   819.6  654.45   839.1  646.27   848.8  641.77   858.6  638.05   868.3  636.37
     878   636.1   907.2   636.2   975.4   637.7   985.2  638.32   994.9  640.38
  1004.6   644.2  1014.4  648.95  1072.8   678.3    1102  692.43  1218.9  747.36
#Mann= 3 , 0 , 0
       0      .1       0   858.6    .045       0   994.9      .1       0
#XS Ineff= 2 , 0
          669.23  683.43
Permanent Ineff=
       F       F
Bank Sta=858.6,994.9
XS Rating Curve= 0 ,0
Exp/Cntr=0.3,0.1

Type RM Length L Ch R = 1 ,41851.9 ,918.2,920.6,922.7
XS GIS Cut Line= 4
     1545939.044      359813.587     1545382.968       359625.71
     1544827.412      359243.766     1544719.773      359146.544
#Sta/Elev= 30
       0  686.22    48.9  680.42    68.5  678.77   166.3  675.47   185.9  674.29
   283.7  663.65   332.6  656.64   352.2  655.03   410.9  655.47   430.4  657.34
   469.6  662.78     538   665.3     626  666.64     841  668.09   889.8   667.1
   997.3   655.9  1007.1  653.85  1065.7   637.1  1075.5  636.07  1111.5  635.95
    1183  636.65  1192.8  637.06  1202.5  639.25  1212.3  644.33  1231.8  659.25
  1241.6  666.23  1251.4  672.39  1290.2  694.81  1338.5  720.58  1406.2  759.32
#Mann= 3 , 0 , 0
       0     .08       0  1065.7    .045       0  1202.5      .1       0
#XS Ineff= 2 , 0
          852.75  681.88
Permanent Ineff=
       F       F
Bank Sta=1065.7,1202.5
XS Rating Curve= 0 ,0
Exp/Cntr=0.3,0.1

Type RM Length L Ch R = 1 ,40931.3 ,251.2,249.6,248.1
XS GIS Cut Line= 4
     1546318.499      359463.263     1546058.082      359072.638
     1545467.804      358573.506     1545327.882      358472.151
#Sta/Elev= 30
       0  690.06    78.2  690.38     176  678.06   322.8  670.02     401  668.95
   498.8  665.51   577.1  664.26   635.8  664.03   743.4   665.5   841.3  663.92
   880.4  665.35   919.6   664.2   948.9  661.81   978.3  657.54   997.9  651.42
  1027.2  638.23  1032.7636.5688    1037  635.27  1046.8   634.4  1164.2  635.97
  1182.7 637.645  1193.6  641.35  1203.4  645.93  1242.5  666.42  1271.3  679.81
  1280.9  684.89  1309.7  702.57  1328.9  713.41  1376.9  735.33  1415.3  751.84
#Mann= 3 , 0 , 0
       0     .06       0  1032.7    .045       0  1182.7      .1       0
Bank Sta=1032.7,1182.7
XS Rating Curve= 0 ,0
Exp/Cntr=0.3,0.1

Type RM Length L Ch R = 1 ,40681.7 ,94.1,94.1,94.1
XS GIS Cut Line= 6
     1546480.711      361293.069     1546732.473      359694.337
     1546194.568      358776.624     1545862.134      358566.683
     1545497.551      358299.322     1545358.662       358250.71
#Sta/Elev= 30
       0  683.75   382.5  689.98     716  691.68   941.6  680.46  1000.5  679.75
  1088.8  667.84  1147.6  679.19  1245.7  678.18  1363.4  689.23  1432.1  689.01
  1608.6  678.79  1784.3   688.3  2028.3  692.58  2116.2  690.04    2204  691.79
  2408.9  666.62  2506.5  659.77  2623.6  662.92  2741.1  659.76    2908  665.34
  3020.5  666.12  3104.8  656.97    3157637.0502  3173.6   634.3    3307637.4371
    3380  664.61  3527.5  692.34  3576.5  706.31  3596.1  707.81  3674.6  700.69
#Mann= 3 , 0 , 0
       0     .06       0    3157    .045       0    3307      .1       0
#XS Ineff= 2 , 0
         3007.33  671.77
Permanent Ineff=
       F       F
Bank Sta=3157,3307
XS Rating Curve= 0 ,0
Exp/Cntr=0.3,0.1

Type RM Length L Ch R = 1 ,40587.7 ,702.4,705.2,707.9
XS GIS Cut Line= 6
     1552722.717      361816.181     1548445.649      360845.145
     1546947.181      359814.448     1546220.668      358681.391
      1545542.69      358215.988     1545403.801      358167.377
#Sta/Elev= 30
       0  861.44   186.8  876.91     649  820.54  1180.1  817.47  1396.4  847.56
  1593.1  898.29  2153.6   788.1    2370  760.74    2547  775.71  2694.5  730.23
  2969.8  807.07    3196  822.56  3451.7  804.49  3579.5  815.67  3658.2   796.9
    3845  835.24  3982.7  839.66  4543.2  820.28  5034.8  733.44  5614.8  694.78
  5899.9  656.94  6666.4  689.51  7049.6  684.02  7314.8  655.41  7857.3  664.58
    8000  635.57  8019.6   634.3  8127.7  636.88  8294.8  675.19  8520.6  684.78
#Mann= 3 , 0 , 0
       0     .06       0    8000    .045       0  8127.7     .09       0
#XS Ineff= 2 , 0
         7820.51  684.53
Permanent Ineff=
       F       F
Bank Sta=8000,8127.7
XS Rating Curve= 0 ,0
Exp/Cntr=0.3,0.1

Type RM Length L Ch R = 1 ,39882.5 ,532.9,512.6,492.1
XS GIS Cut Line= 6
     1552931.051      359906.459     1549222.241      359332.907
     1547084.877        358655.6     1546161.147      357785.081
     1545569.133      357884.039     1545348.647      358035.081
#Sta/Elev= 30
       0  818.77   343.8  773.19   481.4  732.12   648.4  748.63   844.9  694.16
     953  692.52  1070.8  732.54  1562.1  846.06    1847  942.73    1955     963
  2554.3  761.59  2632.9   763.3  2976.8  695.41  3281.3  694.64  3438.5  676.55
  3595.7  705.04  3762.7   711.6  4859.4  734.42    5330  723.05  5516.4  737.52
  5663.5  725.57  5938.2  733.83  6085.6  719.18  6370.9  645.31  6754.7   653.5
  6990.8  635.55    7069   634.3  7148.2  634.64  7463.1  660.78  8133.8   680.2
#Mann= 3 , 0 , 0
       0     .08       0  6990.8    .045       0  7148.2     .08       0
Bank Sta=6990.8,7148.2
XS Rating Curve= 0 ,0
Exp/Cntr=0.3,0.1

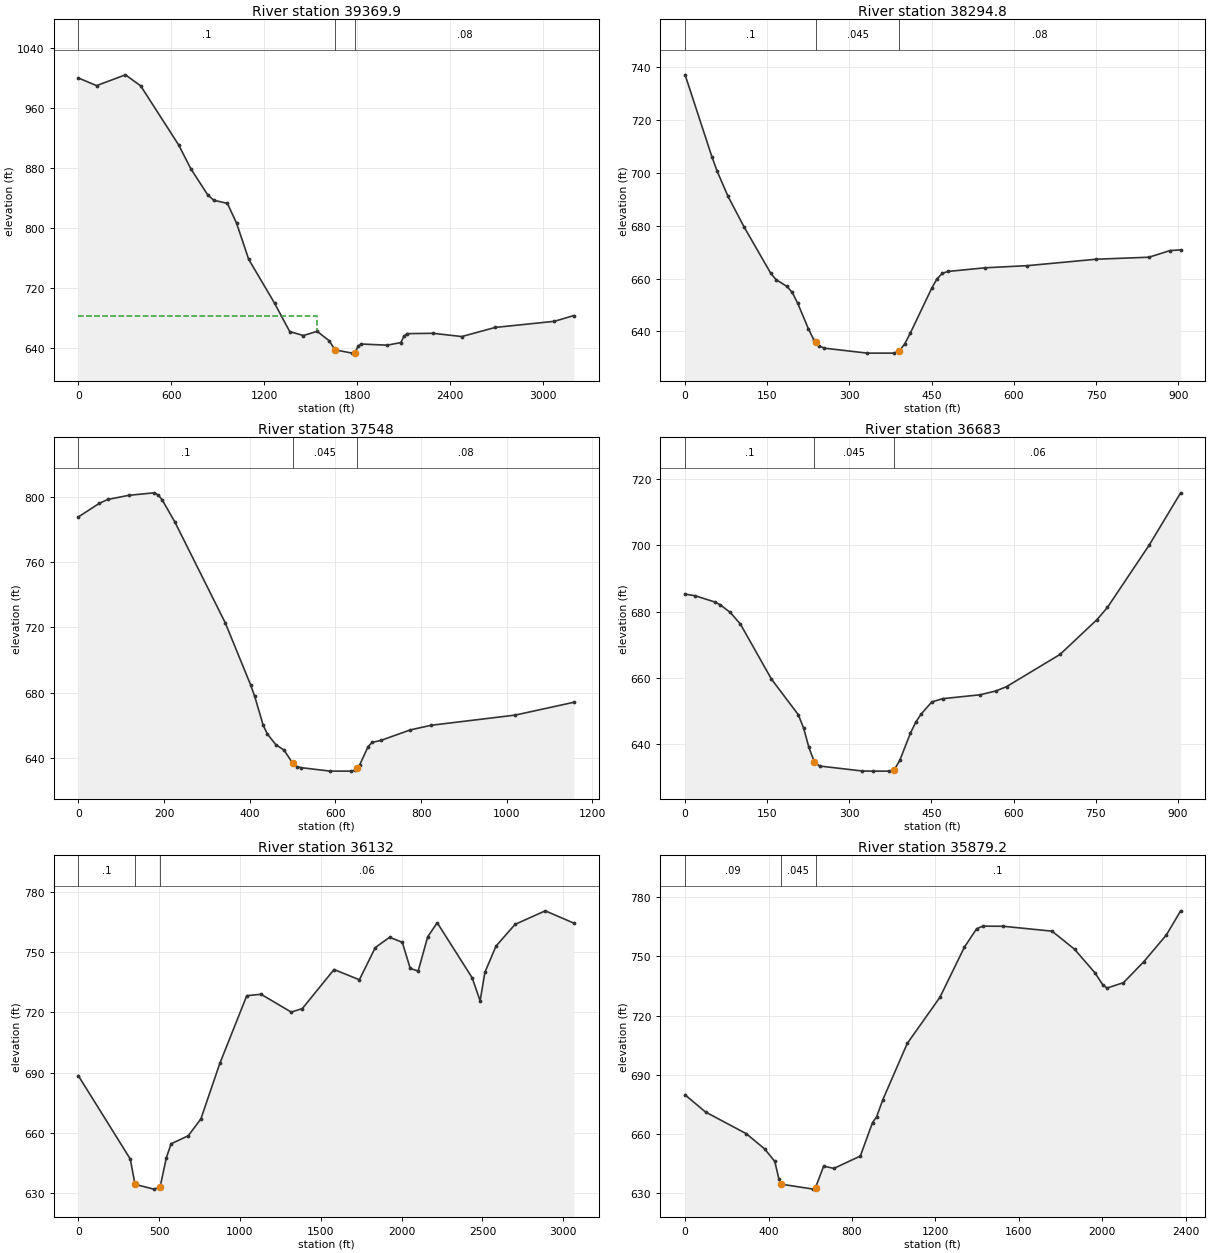
Type RM Length L Ch R = 1 ,39369.9 ,1107,1075.1,1043.1
XS GIS Cut Line= 4
       1548182.1      357211.156     1546112.655      357516.712
     1545376.544      357870.878     1545154.322      358058.378
#Sta/Elev= 30
       0 1000.45   117.8  990.18   304.4  1004.6   402.7  989.86   648.2  910.75
   726.8   878.9   834.8  844.37   874.1  836.96   962.5   832.7  1021.4   806.5
    1100  757.98  1266.9  699.37  1365.1   661.3  1453.5  656.07  1541.9  661.67
  1620.5  648.95  1656.9636.9793  1767.8  632.52  1787.4  633.26  1807.1  641.91
  1826.7  644.69  1993.7  643.15  2082.1  646.61  2101.7  654.77  2121.4  658.57
  2288.7  659.05  2475.7  654.68  2692.2  666.88  3073.5  675.04  3199.5  682.78
#Mann= 3 , 0 , 0
       0      .1       0  1656.9    .045       0  1787.4     .08       0
#XS Ineff= 2 , 0
         1538.46  682.67
Permanent Ineff=
       F       F
Bank Sta=1656.9,1787.4
XS Rating Curve= 0 ,0
Exp/Cntr=0.3,0.1

Type RM Length L Ch R = 1 ,38294.8 ,752.6,746.8,740.9
XS GIS Cut Line= 3
     1545466.337      357074.582     1545455.921      357631.874
     1545252.796      357913.124
#Sta/Elev= 30
       0   737.1    48.9   706.1    58.7  700.54    78.2  691.17   107.6  679.56
   156.5  661.94   166.2  659.57   185.8  657.06   195.6  654.74   205.4  650.71
   224.9  641.07   234.7   636.9     239635.8602   244.5  634.53   254.2  633.68
   332.5   631.8   381.4   631.8   391.2  632.67   400.9  635.35   410.7  639.25
   449.8  656.26   459.6  659.91   469.4  661.97   479.2  662.69   547.6  664.09
   624.8   664.9   750.1  667.33   846.5  668.09     885  670.61   904.3  670.86
#Mann= 3 , 0 , 0
       0      .1       0     239    .045       0   391.2     .08       0
Bank Sta=239,391.2
XS Rating Curve= 0 ,0
Exp/Cntr=0.3,0.1

Type RM Length L Ch R = 1 ,37548   ,864.3,865.1,865.8
XS GIS Cut Line= 2
     1544577.933      356872.614      1544855.19      357995.502
#Sta/Elev= 30
       0  787.88      49  796.24    68.6  798.62   117.6  801.16   176.4   802.7
   186.2  801.47     196  798.24   225.4  784.77   343.1   722.8   401.9  684.94
   411.7  677.72   431.3  660.11   441.1  654.66   460.7  648.14   480.3  644.68
   500.3636.6339   509.7  634.61   519.5  633.94   588.1   631.8   637.1  631.81
   646.9  632.38   650.3633.5006   656.7  635.61   676.3  646.86   686.1   649.5
   705.7  650.61   774.3  657.07   823.4  659.96  1019.4   666.2  1156.6  674.08
#Mann= 3 , 0 , 0
       0      .1       0   500.3    .045       0   650.3     .08       0
Bank Sta=500.3,650.3
XS Rating Curve= 0 ,0
Exp/Cntr=0.3,0.1

Type RM Length L Ch R = 1 ,36683   ,548.3,550.9,553.5
XS GIS Cut Line= 4
     1543833.662      357295.502      1543830.19      357423.974
     1543951.718      357996.891     1543951.718      358187.863
#Sta/Elev= 30
       0  685.25    18.4  684.76    55.1  682.83    64.3  682.01    82.6  679.71
     101  676.21   157.8  659.57   206.6  648.88   216.4  644.86   226.1  638.98
   235.9  634.66   245.6  633.34   323.7  631.84   343.3   631.8   372.6   631.8
   382.3  632.29   392.1  635.03   411.6  643.27   421.4   646.6   431.1  649.02
   450.6  652.68   470.2  653.67   538.5  654.85   567.8  656.01   587.3  657.33
   684.9  667.04   752.4  677.56   771.5  681.24   847.9   700.1   905.2  715.84
#Mann= 3 , 0 , 0
       0      .1       0   235.9    .045       0   382.3     .06       0
Bank Sta=235.9,382.3
XS Rating Curve= 0 ,0
Exp/Cntr=0.3,0.1

Type RM Length L Ch R = 1 ,36132   ,255.1,252.9,250.7
XS GIS Cut Line= 5
     1543337.134      357281.613      1543298.94      357403.141
      1543361.44      358069.808     1544121.052      358674.996
     1544001.309      359966.713
#Sta/Elev= 30
       0  688.45   321.5  646.82   350.6  634.18     467   631.8   505.8   632.8
   544.7  647.52   573.8  654.42   680.5  658.46   758.2  666.87   875.5  694.59
  1042.2  728.37  1130.5  729.07  1316.9  720.18  1385.6  721.92  1581.8  741.42
  1738.8  736.32    1837  752.37  1925.4  757.53  2004.1  755.02  2053.2  741.99
  2102.3  740.66  2161.3  757.77  2220.3  764.77  2436.5  737.26  2485.6  725.78
  2515.1     740  2583.9  753.12  2701.8  763.97  2888.6  770.72  3065.4  764.58
#Mann= 3 , 0 , 0
       0      .1       0   350.6    .045       0   505.8     .06       0
Bank Sta=350.6,505.8
XS Rating Curve= 0 ,0
Exp/Cntr=0.3,0.1

Type RM Length L Ch R = 1 ,35879.2 ,391.1,392.7,394.2
XS GIS Cut Line= 4
     1543003.801      357215.641     1542993.384      357312.863
     1543149.634      358118.419     1542547.316       359445.88
#Sta/Elev= 30
       0  679.79    97.8  671.12   293.2  660.14   381.1  652.44   429.9  646.09
   449.4  637.36   459.2  634.56   615.5  632.03   625.3  632.78   664.4   643.7
   713.2  642.53   840.2  648.78   898.8  665.79   918.4  668.66   947.7  677.26
  1065.1  705.84  1221.6   729.2    1339   754.6  1397.7  763.97  1427.1  765.29
  1524.9  765.24  1759.7  762.76  1867.3  753.61  1965.2  741.65  2004.3   735.3
  2023.9  733.95  2102.1  736.67    2200  747.36  2307.6  760.81  2376.1  773.06
#Mann= 3 , 0 , 0
       0     .09       0   459.2    .045       0   625.3      .1       0
Bank Sta=459.2,625.3
XS Rating Curve= 0 ,0
Exp/Cntr=0.3,0.1

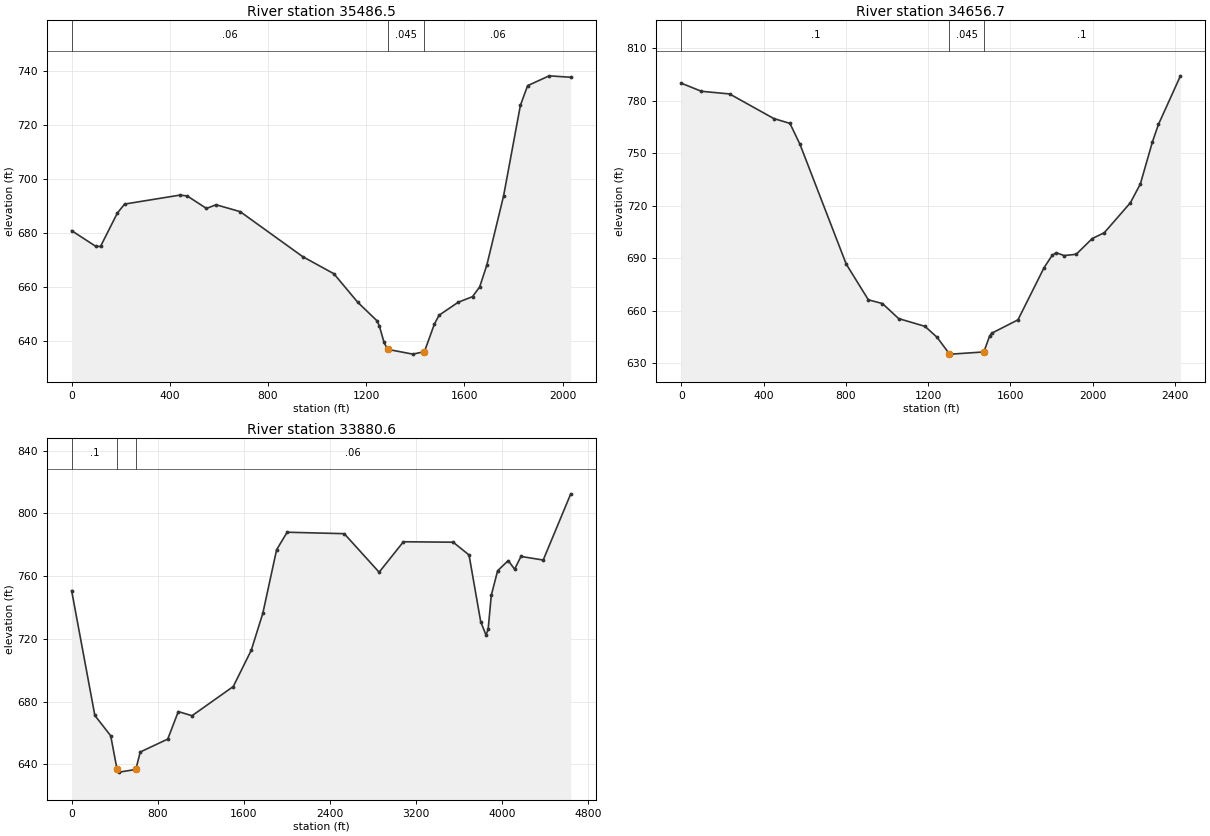
Type RM Length L Ch R = 1 ,35486.5 ,829.8,829.8,829.9
XS GIS Cut Line= 4
     1543209.992      356648.158      1542642.69      357423.974
      1542736.44      358177.447     1542670.468      358483.002
#Sta/Elev= 30
       0  680.87    98.1  675.07   117.7  675.01   186.3  687.39   215.8  690.72
   441.3  694.05   470.8  693.74   549.2   689.1   588.4  690.47   686.5  687.92
   941.5  671.22  1068.2   664.9  1165.5  654.31  1243.4   647.5  1253.1  645.63
  1272.6  639.43  1286.9 636.882  1389.4   635.1  1436.9635.9975    1477   646.1
  1496.5  649.52  1574.4  654.32  1632.8   656.4    1662  660.01  1691.2  668.12
  1759.5   693.8  1827.8  727.28  1857.2  734.61  1945.1  738.26    2033  737.73
#Mann= 3 , 0 , 0
       0     .06       0  1286.9    .045       0  1436.9     .06       0
Bank Sta=1286.9,1436.9
XS Rating Curve= 0 ,0
Exp/Cntr=0.3,0.1

Type RM Length L Ch R = 1 ,34656.7 ,768.1,776.1,784.1
XS GIS Cut Line= 4
      1541470.22      356595.526     1541812.829      357458.697
     1541906.579       358229.53     1541911.954       358950.73
#Sta/Elev= 30
       0  790.12    97.8   785.5   234.6  783.99   449.7   769.9   527.9  767.14
   576.8  755.16   801.6  686.63   909.1  666.19   977.8  664.04  1056.5  655.44
  1184.2  651.01  1243.2  644.74  1302.2  635.41    1312   635.1  1470.6636.3474
  1498.8   645.5  1508.6  647.05  1636.4  654.72  1763.7  684.64  1802.6   691.6
  1822.2  693.14  1861.1   691.5  1919.6  692.24  1997.6  701.24  2056.1  704.57
  2182.8  721.68  2231.5   732.5    2290  756.51  2319.2   766.5  2426.4  794.35
#Mann= 3 , 0 , 0
       0      .1       0  1302.2    .045       0  1470.6      .1       0
Bank Sta=1302.2,1470.6
XS Rating Curve= 0 ,0
Exp/Cntr=0.3,0.1

Type RM Length L Ch R = 1 ,33880.6 ,787.7,787.2,786.6
XS GIS Cut Line= 4
     1541232.968      357272.933     1540991.458      358294.396
     1541805.261      360505.667     1543029.219      360627.195
#Sta/Elev= 30
       0  750.74   215.8   671.2     363  658.27   421.8  636.88   441.4   635.1
   596.1 636.801   637.6  647.94   892.7  656.15   990.8  673.68  1118.4  671.04
  1501.2  689.64  1668.2  712.72  1776.1  736.37  1903.8  776.78    2002  787.95
  2532.1  787.02  2856.1  762.47  3081.9  781.88  3543.6  781.58  3691.2  773.46
  3799.5  730.96  3848.7  722.46  3868.4     726  3897.9  747.79  3956.9  763.45
  4055.3  769.86  4114.4  764.39  4173.4  772.52    4380  770.22  4635.9  812.41
#Mann= 3 , 0 , 0
       0      .1       0   421.8    .045       0   596.1     .06       0
Bank Sta=421.8,596.1
XS Rating Curve= 0 ,0
Exp/Cntr=0.3,0.1