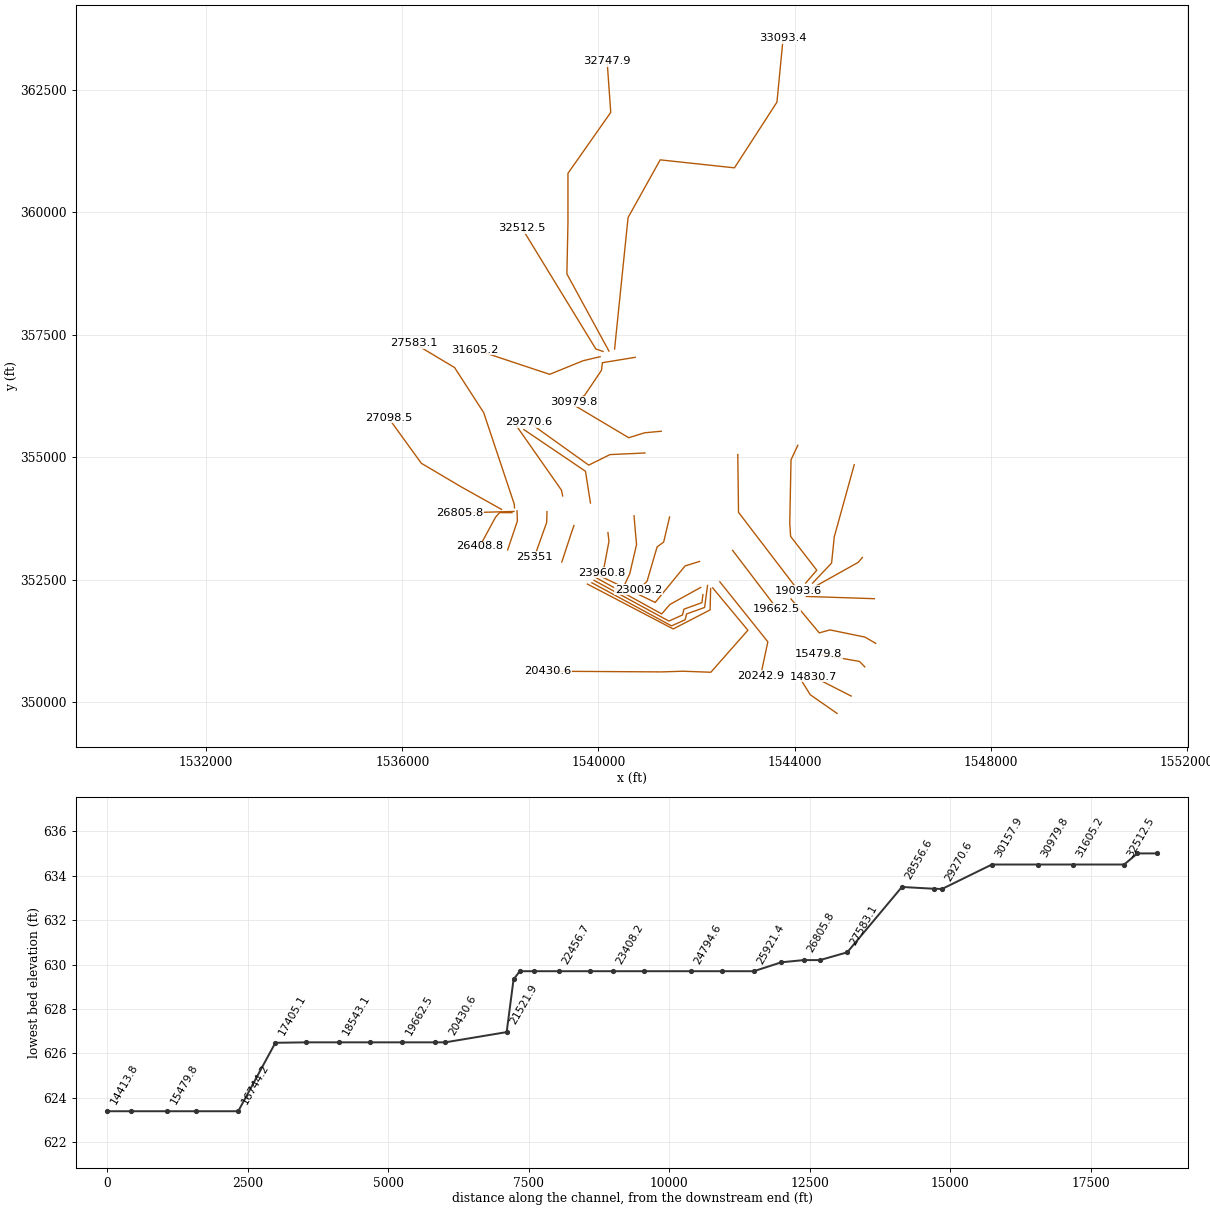
HEC-RAS study MDISLCRK1.prj: MDISLCRK1

--- MDISLCRK1.g01 (geometry) --- (continued)

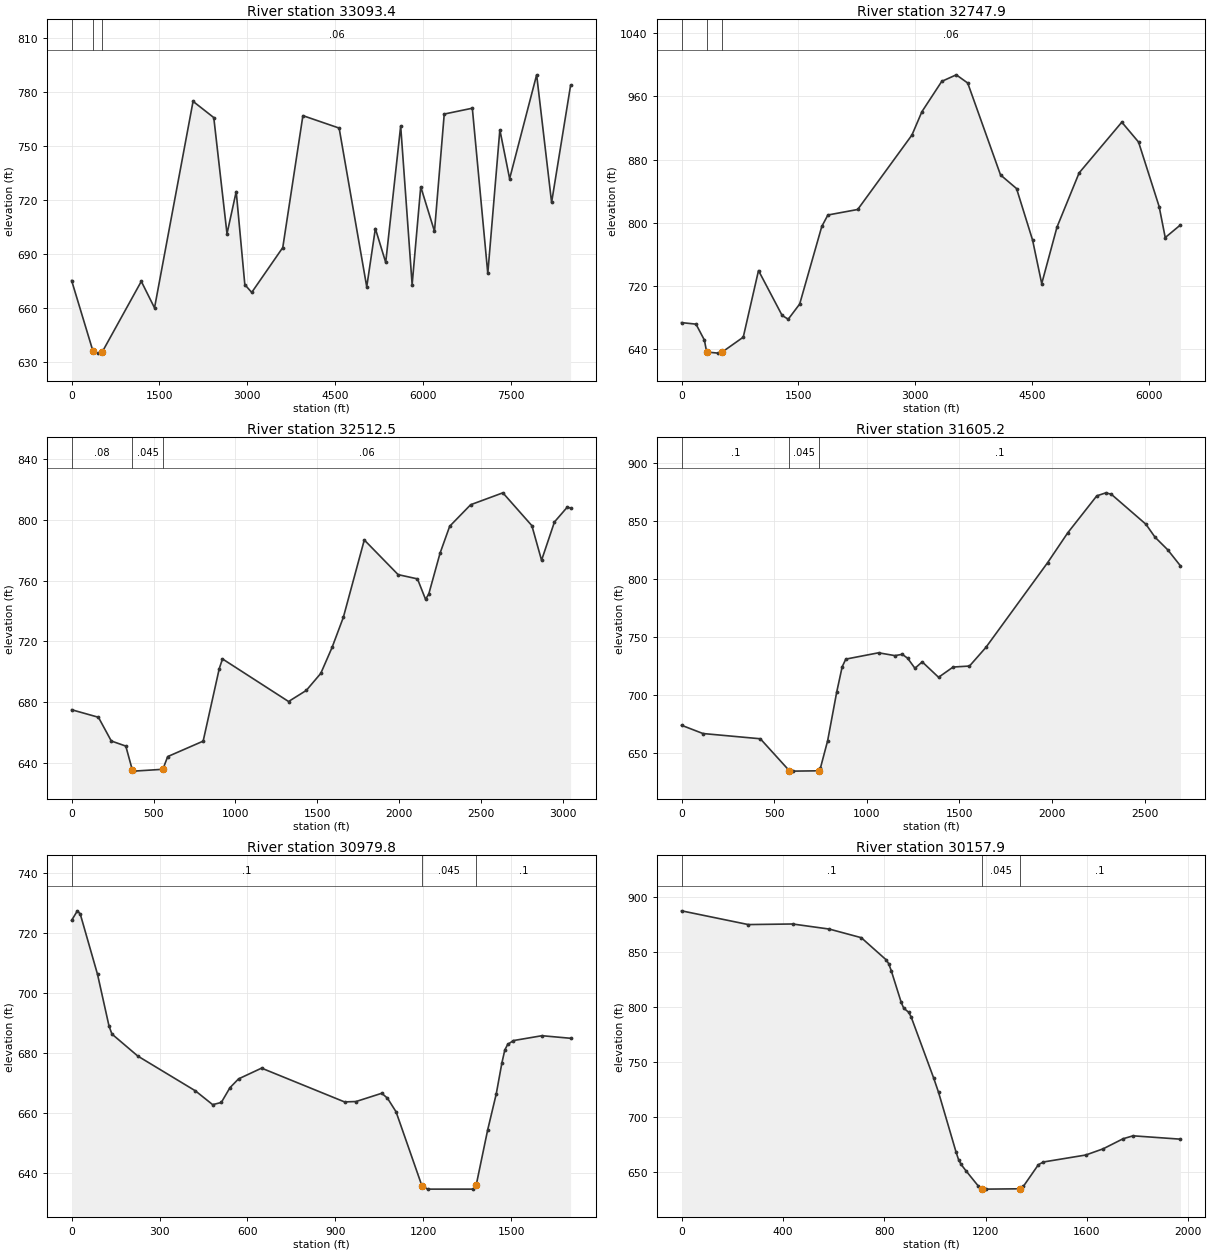
Type RM Length L Ch R = 1 ,33093.4 ,338.8,345.4,352.1
XS GIS Cut Line= 6
      1540330.19      357208.697     1540605.228      359890.719
     1541260.368       361066.45     1542774.938      360903.633
     1543641.638      362244.384      1543767.09      363544.945
#Sta/Elev= 30
       0  675.35   364.8   636.1   445.6     635   522.2  635.58  1190.6  674.89
  1416.7  660.14  2075.3   774.9  2429.2  765.88  2655.2  701.32  2812.5  724.77
  2959.8  673.06  3077.7  668.73  3608.2  693.66  3952.1  766.96  4571.2  760.05
  5042.9  671.83  5190.3  704.23  5367.2   685.4  5622.8  761.23  5818.6  673.04
  5965.6  727.45  6200.6  702.68  6367.1  767.84  6847.1  771.09  7111.5  679.25
  7317.5  759.11  7484.5  731.91  7946.2  789.64  8201.7  718.71  8525.8  783.71
#Mann= 3 , 0 , 0
       0      .1       0   364.8    .045       0   522.2     .06       0
Bank Sta=364.8,522.2
XS Rating Curve= 0 ,0
Exp/Cntr=0.3,0.1

Type RM Length L Ch R = 1 ,32747.9 ,234.2,235.4,236.6
XS GIS Cut Line= 6
     1540214.417      357167.234     1539357.212      358740.585
     1539378.913      359771.401     1539378.913      360791.366
     1540251.904      362034.429     1540177.774      363078.917
#Sta/Elev= 30
       0  673.62     186  671.69   293.7  651.55   323.1  636.39     470     635
   518.9  636.12     793  655.19   988.9   739.5  1292.4  682.68  1370.7  677.92
  1517.6  697.11  1801.5  795.27  1880.1  809.81    2263  816.79  2960.1  911.09
  3087.6  940.53  3342.6  978.93  3528.9  987.21    3676  976.86  4097.5  860.51
  4303.3  843.28  4509.1  778.12  4626.7  722.96  4822.7  794.46  5106.9  863.07
  5655.3   927.3  5870.6  902.12  6134.8  820.53  6213.1  781.24  6408.8  797.26
#Mann= 3 , 0 , 0
       0      .1       0   323.1    .045       0   518.9     .06       0
Bank Sta=323.1,518.9
XS Rating Curve= 0 ,0
Exp/Cntr=0.3,0.1

Type RM Length L Ch R = 1 ,32512.5 ,875.6,907.4,939.1
XS GIS Cut Line= 3
     1540094.079      357160.085     1539948.246      357208.697
     1538439.044      359676.434
#Sta/Elev= 30
       0  674.96   163.6  669.99   242.3  654.36   330.8     651   370.2  635.45
     380   634.5   557.1  635.71   586.6  644.08   803.1  654.26   901.5  702.05
   921.2  708.43  1324.6  680.37  1432.8  687.67  1521.3   698.9  1590.2  715.99
  1659.1  735.84    1787  786.81  1993.6  763.97  2111.7  761.17  2160.9  747.73
  2180.5  751.14  2249.4  778.05  2308.4  795.85  2436.4  810.03  2633.1  817.87
  2810.2  796.24  2869.3  773.43    2948  798.66  3026.7  808.48  3046.4   807.8
#Mann= 3 , 0 , 0
       0     .08       0   370.2    .045       0   557.1     .06       0
Bank Sta=370.2,557.1
XS Rating Curve= 0 ,0
Exp/Cntr=0.3,0.1

Type RM Length L Ch R = 1 ,31605.2 ,612,625.3,638.7
XS GIS Cut Line= 4
     1540035.236      357051.886     1539688.014      356969.942
     1539006.069      356692.164     1537487.655      357197.267
#Sta/Elev= 30
       0     674   115.7  666.88   425.5  662.36   582.6  634.75   602.2   634.5
   739.7  634.78   749.5  636.95   788.8   660.7   837.8  702.64   867.3   724.4
   886.9  730.95  1063.6   736.4    1152  733.96  1191.3  735.09  1220.7   731.7
    1260  723.06  1299.3  728.58  1387.6   715.3  1466.2  724.14  1554.5  724.99
  1642.9  741.01  1976.7  814.14  2084.7  839.68  2241.7  871.55  2290.8  874.14
  2320.3  872.87  2506.8  847.09  2555.9  835.95  2624.6  825.08  2693.3  811.24
#Mann= 3 , 0 , 0
       0      .1       0   582.6    .045       0   739.7      .1       0
Bank Sta=582.6,739.7
XS Rating Curve= 0 ,0
Exp/Cntr=0.3,0.1

Type RM Length L Ch R = 1 ,30979.8 ,856.2,821.9,787.6
XS GIS Cut Line= 5
     1540750.495      357039.272     1540081.521      356929.547
     1540062.829      356774.669     1539719.079      356264.252
     1539500.329       356135.78
#Sta/Elev= 30
       0  724.32    19.6  727.52    29.5  726.45    88.4   706.3   127.7     689
   137.6  686.34     226  678.97   422.5  667.35   481.4  662.74   510.9  663.46
   540.4   668.4   569.8  671.35   648.4  674.94   931.6  663.65   970.7  663.78
  1058.6  666.54  1078.1  664.89  1107.4  660.35  1195.3   635.7  1214.9   634.5
  1371.2   634.5  1380.9  635.84    1420  654.26  1449.3   666.3  1468.8  676.78
  1478.6  681.02  1488.3  682.86  1507.8  684.15  1605.4  685.78    1703  684.92
#Mann= 3 , 0 , 0
       0      .1       0  1195.3    .045       0  1380.9      .1       0
Bank Sta=1195.3,1380.9
XS Rating Curve= 0 ,0
Exp/Cntr=0.3,0.1

Type RM Length L Ch R = 1 ,30157.9 ,889.2,887.3,885.4
XS GIS Cut Line= 4
     1541281.875      355531.526     1540941.598      355500.276
     1540618.681      355399.582     1539511.042      356059.304
#Sta/Elev= 30
       0  887.81   263.6   875.3   438.4  875.83   583.3   871.2   709.5  863.36
   807.9  843.16   817.7  839.66   827.6  833.44     867  804.56   876.8  799.26
   896.5  795.48   906.3  791.22   994.9  735.79  1014.6  722.46  1083.5  668.25
  1093.3  661.42  1103.1  657.08  1122.8  651.15    1172  637.11  1184.8634.9495
  1201.6   634.5  1334.8634.8021  1349.2  637.03  1408.2  656.66  1427.9  659.19
  1595.2  665.54  1664.1  671.19  1742.8  680.36  1782.2  683.03  1969.2  679.97
#Mann= 3 , 0 , 0
       0      .1       0  1184.8    .045       0  1334.8      .1       0
Bank Sta=1184.8,1334.8
XS Rating Curve= 0 ,0
Exp/Cntr=0.3,0.1

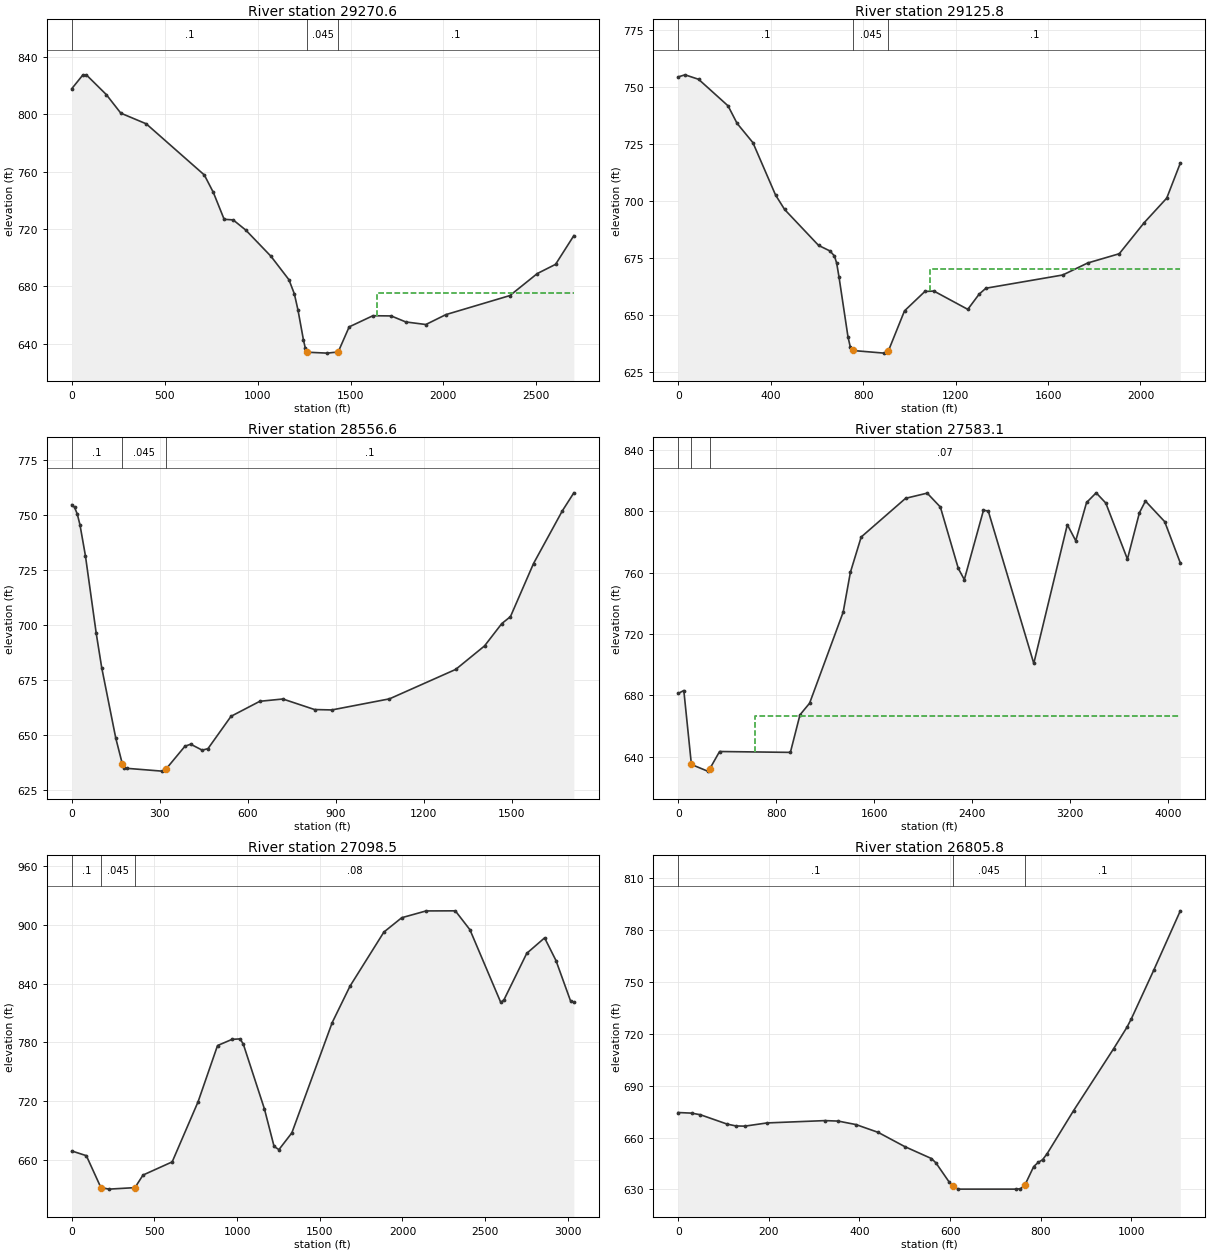
Type RM Length L Ch R = 1 ,29270.6 ,144.2,144.8,145.4
XS GIS Cut Line= 4
     1540949.226      355088.241     1540236.557       355055.34
     1539802.412      354840.641     1538579.669      355716.364
#Sta/Elev= 30
       0  817.77    58.6  827.18    78.2  827.44   185.7  813.69   263.9  800.72
   400.7  793.28   713.4   757.6   761.9  745.43     820   726.7   868.4   726.3
   936.2  719.21  1071.8  700.94  1168.7  684.57  1197.8  674.72  1217.4   663.4
  1246.9  642.47  1256.7  636.89  1266.6  634.04  1374.7   633.4  1433.7  634.23
  1492.7   651.7  1620.4  659.47  1718.8  659.34  1797.4  655.14  1905.5  653.35
  2013.6  660.27  2357.7  673.54  2505.2  688.89  2603.4   695.3  2701.8  715.33
#Mann= 3 , 0 , 0
       0      .1       0  1266.6    .045       0  1433.7      .1       0
#XS Ineff= 2 , 0
                         1642.86          675.28
Permanent Ineff=
       F       F
Bank Sta=1266.6,1433.7
XS Rating Curve= 0 ,0
Exp/Cntr=0.3,0.1

Type RM Length L Ch R = 1 ,29125.8 ,577.5,569.1,561.1
XS GIS Cut Line= 3
     1539838.115      354067.407      1539736.44      354715.641
     1538480.711      355565.323
#Sta/Elev= 30
       0   754.5    29.4   755.4    88.1  753.44   215.5  741.81   254.6  734.12
   323.2  725.66   421.1  702.71   460.3  696.37   607.2  680.63   656.2  678.21
   675.7  676.02   685.5  672.85   695.3  666.99   734.4  640.58   744.2  636.18
     754  634.57   890.9  633.41   909.2634.3694     979  651.94    1067  660.43
  1106.1  660.62  1252.8   652.6  1301.8  659.25  1331.1  661.86  1663.7  667.66
  1771.3  672.91  1908.2  676.98  2015.8  690.57  2113.6  701.36  2172.3  716.71
#Mann= 3 , 0 , 0
       0      .1       0     754    .045       0   909.2      .1       0
#XS Ineff= 2 , 0
                         1089.74          670.28
Permanent Ineff=
       F       F
Bank Sta=754,909.2
XS Rating Curve= 0 ,0
Exp/Cntr=0.3,0.1

Type RM Length L Ch R = 1 ,28556.6 ,979.5,973.5,966.6
XS GIS Cut Line= 3
     1539271.162      354212.169     1539246.857      354330.224
     1538334.877      355633.031
#Sta/Elev= 30
       0  754.82     9.3  753.67    18.5  750.68    27.8  745.77    46.4  731.69
    83.4  696.18     102  680.64     150  648.47   172.1636.8831   179.4  635.14
   189.2  634.75     307  633.49   322.1 634.591   385.6  644.82   405.2  645.75
   444.5  643.04   464.1  643.73   542.6  658.45   640.8   665.3   719.3  666.34
   827.3  661.54   886.2  661.36  1082.6  666.41  1308.3  679.82  1406.5  690.52
  1465.4  700.71  1494.8  703.85  1573.4  728.04  1671.6  752.04  1710.8  760.24
#Mann= 3 , 0 , 0
       0      .1       0   172.1    .045       0   322.1      .1       0
Bank Sta=172.1,322.1
XS Rating Curve= 0 ,0
Exp/Cntr=0.3,0.1

Type RM Length L Ch R = 1 ,27583.1 ,464.5,484.6,505.3
XS GIS Cut Line= 5
     1538288.523      353969.113     1538285.051       354042.03
     1537660.722      355910.478     1537066.487      356830.783
     1536240.892      357324.352
#Sta/Elev= 30
       0  681.19    45.6  683.11   107.5634.8898   239.6  630.55   257.5632.0485
   337.6  643.34   915.9  642.77   994.3  667.27  1072.7  674.81  1347.1  734.22
  1405.9  760.13  1494.1  783.17  1856.8   808.4  2033.2  811.78  2140.8  802.71
  2287.5  762.65  2336.4  755.41  2492.9  800.62    2532  800.12  2903.7  700.78
  3177.7  791.21  3246.4  780.76  3334.8  805.68  3413.3  811.98  3491.8  805.32
  3668.5  768.75  3766.6  799.03  3815.7  806.61  3972.8   793.2  4100.4  766.28
#Mann= 3 , 0 , 0
       0      .1       0   107.5    .045       0   257.5     .07       0
#XS Ineff= 2 , 0
                          625.16          666.45
Permanent Ineff=
       F       F
Bank Sta=107.5,257.5
XS Rating Curve= 0 ,0
Exp/Cntr=0.3,0.1

Type RM Length L Ch R = 1 ,27098.5 ,284,292.7,301.4
XS GIS Cut Line= 4
     1538025.416       353936.85     1537187.742        354405.6
     1536389.131      354877.823      1535715.52      355808.378
#Sta/Elev= 30
       0  669.16    88.2  664.34   176.3  631.74   225.3   630.2     382  631.73
     431  644.57   607.3  658.01     764  719.42   881.6  776.77   969.7  783.11
  1018.5  783.57    1038  777.93    1165  712.17  1223.6  673.76  1252.9  670.53
    1331  687.63  1575.2  800.28  1682.6  837.37  1887.7  892.63  1995.7  907.28
    2143   914.2  2319.7   914.3  2408.1  894.98  2594.6  820.76  2614.3   823.6
  2751.7  870.92  2859.7  886.69  2928.5  863.53  3016.8   822.2  3036.5  820.83
#Mann= 3 , 0 , 0
       0      .1       0   176.3    .045       0     382     .08       0
Bank Sta=176.3,382
XS Rating Curve= 0 ,0
Exp/Cntr=0.3,0.1

Type RM Length L Ch R = 1 ,26805.8 ,373,397,420.6
XS GIS Cut Line= 2
     1538278.107      353896.197     1537170.468      353864.947
#Sta/Elev= 30
       0  674.41    29.4  674.07      49  673.13   107.9  667.74   127.5  666.66
   147.1  666.56   196.1  668.41   323.6  669.75     353  669.48   392.2  667.47
   441.3  662.96   500.1  654.73   558.9  647.85   568.8  645.33   598.2   634.2
   605.8 631.889   617.8   630.2   745.3   630.2   755.1  630.39   764.9  632.46
   784.5  643.21   794.3  645.59   804.1  647.18   813.9  650.55   872.7  675.58
     961  711.28   990.4  723.67  1000.2  728.61  1049.2  756.42  1108.1  790.84
#Mann= 3 , 0 , 0
       0      .1       0   605.8    .045       0   764.9      .1       0
Bank Sta=605.8,764.9
XS Rating Curve= 0 ,0
Exp/Cntr=0.3,0.1

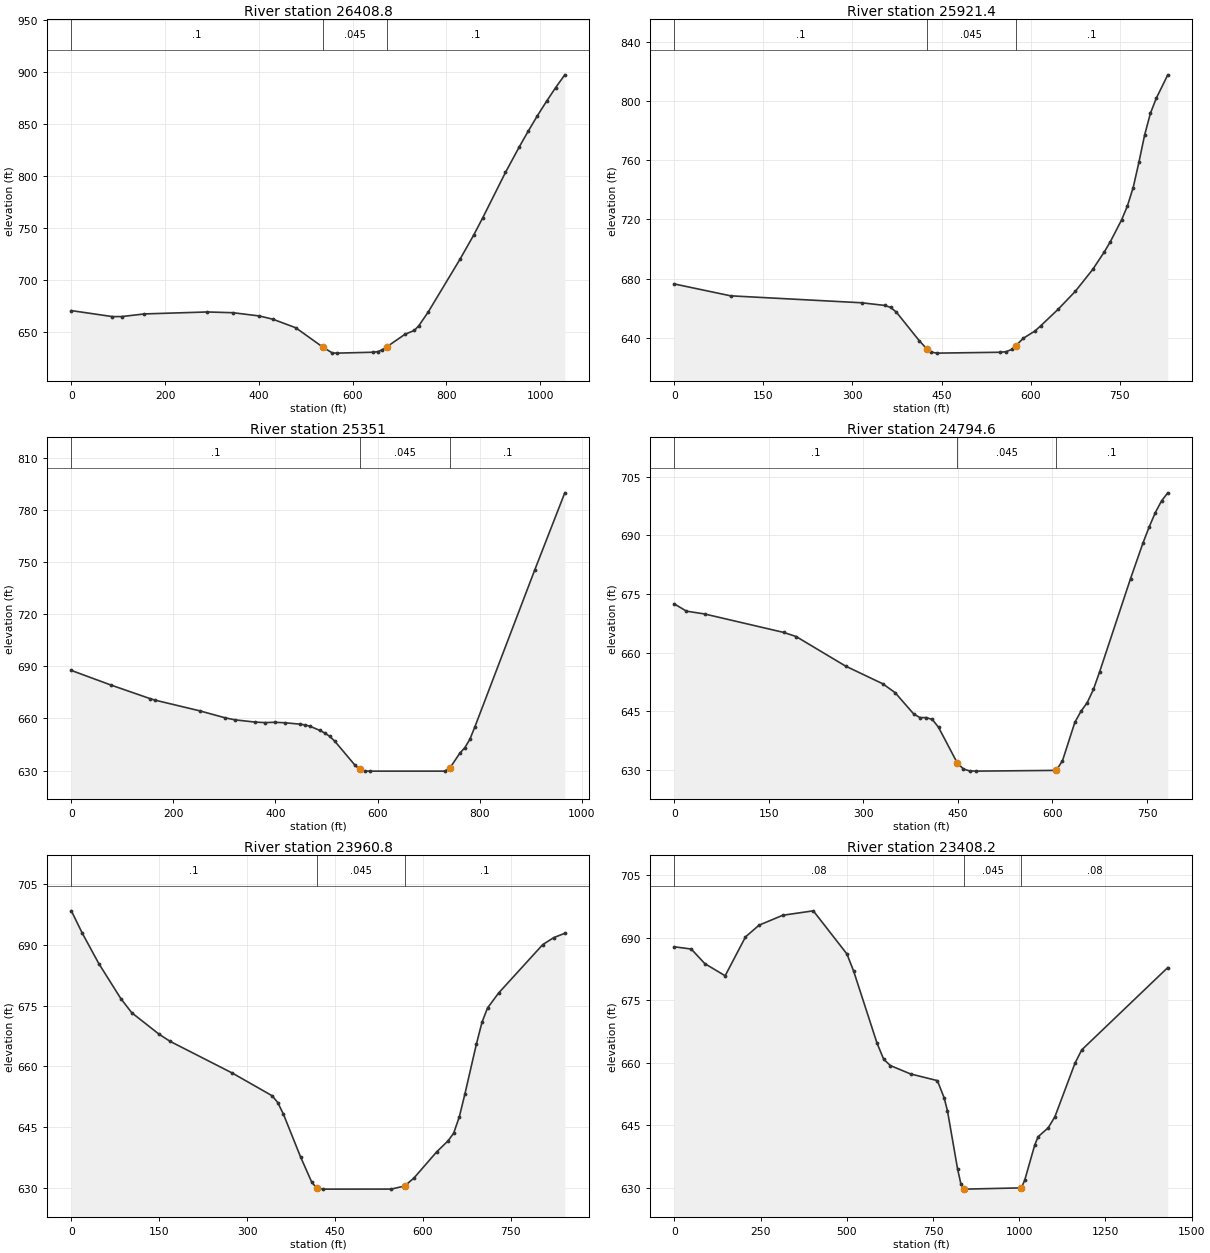
Type RM Length L Ch R = 1 ,26408.8 ,483.4,487.3,491.2
XS GIS Cut Line= 4
      1538236.44      353871.891     1537982.968      353871.891
     1537899.634      353774.669      1537580.19      353184.391
#Sta/Elev= 30
       0   670.9    87.7  665.15   107.2  665.17     156  667.72   290.1  669.59
   344.9  668.87     401  665.76   430.2   662.6   478.8  654.43   537.2  635.65
   556.6   630.3   566.3   630.1   644.2  630.97   653.9  631.55   663.6  633.38
   673.3  636.25   712.2   648.3   731.7  651.83   741.4  656.49   760.9  669.26
     829   720.1   858.2  743.24   877.6  759.92   926.2  803.53   955.4  827.84
   974.9  843.25   994.3  857.91  1013.8  871.74  1033.2  884.89  1052.7  897.12
#Mann= 3 , 0 , 0
       0      .1       0   537.2    .045       0   673.3      .1       0
Bank Sta=537.2,673.3
XS Rating Curve= 0 ,0
Exp/Cntr=0.3,0.1

Type RM Length L Ch R = 1 ,25921.4 ,570.9,570.4,570
XS GIS Cut Line= 3
     1538340.607      353910.085     1538347.551      353701.752
     1538149.634      353111.474
#Sta/Elev= 30
       0   676.4    94.8  668.39   315.4   663.7   354.4   661.9   364.1  660.58
   373.8  657.47   412.7  637.98   425.3632.5727   432.2  630.46   441.9   629.7
   548.9  630.29   558.6  630.66   568.4  632.22   575.3634.7808   587.8  639.75
   607.3  644.62     617  648.12   646.2  659.23   675.4  671.48   704.6  686.19
     724  697.96   733.8  704.55   753.2  719.62   762.9  728.91   772.7  741.39
   782.4  758.51   792.1  777.08   801.8  791.64   811.6  801.72     831   817.6
#Mann= 3 , 0 , 0
       0      .1       0   425.3    .045       0   575.3      .1       0
Bank Sta=425.3,575.3
XS Rating Curve= 0 ,0
Exp/Cntr=0.3,0.1

Type RM Length L Ch R = 1 ,25351   ,555.9,556.4,557
XS GIS Cut Line= 3
     1538951.718      353892.724     1538944.773      353670.502
     1538694.773      352969.113
#Sta/Elev= 30
       0  687.67    77.3   679.3   154.7   671.4   164.3  670.55   251.7   664.4
   300.7  660.44   320.3  659.24   359.5  657.95   379.1  657.64   398.7  657.82
   418.3  657.55   447.7  656.75   457.5  656.32   467.3  655.58   486.9  653.14
   496.7  651.63   506.5  649.67   516.3   646.9   555.4  633.25   565.2  630.64
     575  629.77   584.8   629.7   731.8   629.7   741.6   631.4   761.2  640.04
     771  643.19   780.8  647.98   790.6  655.11   908.2  745.66   966.9  789.92
#Mann= 3 , 0 , 0
       0      .1       0   565.2    .045       0   741.6      .1       0
Bank Sta=565.2,741.6
XS Rating Curve= 0 ,0
Exp/Cntr=0.3,0.1

Type RM Length L Ch R = 1 ,24794.6 ,830.7,833.8,836.7
XS GIS Cut Line= 3
     1539500.329      353608.002     1539441.301      353434.391
     1539253.801      352864.947
#Sta/Elev= 30
       0  672.48    19.3  670.63    48.3   669.9   173.7  665.18   193.2  664.14
   271.8  656.57   330.8  652.04   350.4  649.77   379.9  644.31   389.8  643.39
   399.6   643.4   409.4  642.92   419.2  640.91   448.7  631.87   458.6  630.25
   468.4  629.76   478.2   629.7     606  629.89   615.8  632.33   635.5  642.19
   645.3  645.04   655.1  647.22     665  650.62   674.8  655.11   723.9  678.98
   743.6  688.08   753.4  692.17   763.2  695.86   773.1  698.85   782.9   700.9
#Mann= 3 , 0 , 0
       0      .1       0   448.7    .045       0     606      .1       0
Bank Sta=448.7,606
XS Rating Curve= 0 ,0
Exp/Cntr=0.3,0.1

Type RM Length L Ch R = 1 ,23960.8 ,553.4,552.6,551.6
XS GIS Cut Line= 4
     1540194.773      353465.641     1540215.607      353288.558
     1540118.384      352774.669     1540059.357      352646.197
#Sta/Elev= 30
       0  698.45    18.8   692.9    46.9  685.42    84.5  676.77   103.2  673.27
   150.2  667.93   168.9  666.19   275.2  658.35     343  652.76   352.6  651.07
   362.3  648.18   391.4  637.68   410.8  631.34   419.2 629.975   430.1   629.7
   546.3  629.71   569.2630.4703   585.1  632.44   623.8  638.89   643.2  641.61
   652.9  643.51   662.6  647.58   672.2  653.26   691.6  665.45   701.3  670.92
   710.7  674.44   729.6  678.13     805   690.1   823.8  691.83   842.7   692.9
#Mann= 3 , 0 , 0
       0      .1       0   419.2    .045       0   569.2      .1       0
Bank Sta=419.2,569.2
XS Rating Curve= 0 ,0
Exp/Cntr=0.3,0.1

Type RM Length L Ch R = 1 ,23408.2 ,400.4,399.1,397.9
XS GIS Cut Line= 5
     1540726.805      353807.944     1540762.611      353386.835
     1540778.107      353222.585     1540639.218      352625.363
     1540541.996       352417.03
#Sta/Elev= 30
       0   687.8    49.1  687.26    88.5  683.76   147.4  680.85   206.4  690.17
   245.7  692.98   314.5  695.36     403  696.42   500.3   686.1   519.7  682.03
   587.6  664.73   607.1  660.83   626.5  659.32   684.9  657.32   762.8  655.71
   782.3   651.6     792  648.48   821.2  634.58   830.9  630.95   839.9629.8021
   840.7   629.7  1006.1     630  1015.8   631.8    1045  640.27  1054.8  642.26
    1084  644.39  1103.4  647.03  1161.8  659.91  1181.3  663.09  1430.7  682.82
#Mann= 3 , 0 , 0
       0     .08       0   839.9    .045       0  1006.1     .08       0
Bank Sta=839.9,1006.1
XS Rating Curve= 0 ,0
Exp/Cntr=0.3,0.1

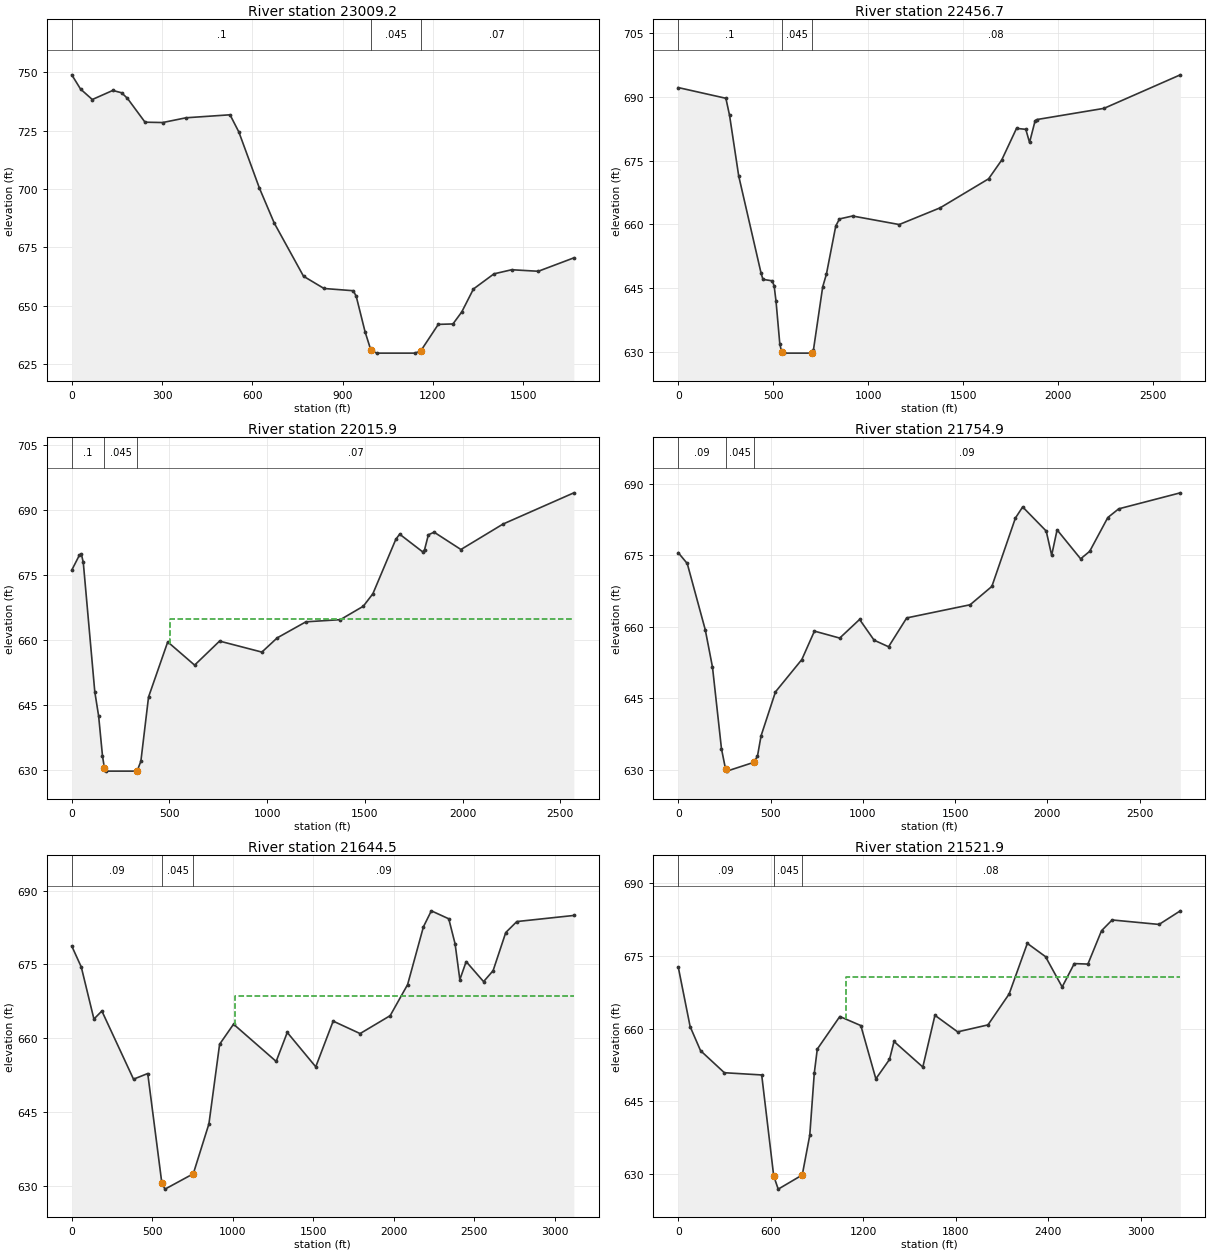
Type RM Length L Ch R = 1 ,23009.2 ,561.5,552.5,543.4
XS GIS Cut Line= 5
     1541452.122       353783.56     1541331.255      353271.794
     1541197.511      353173.016     1540992.419       352472.27
     1540818.755      352298.183
#Sta/Elev= 30
       0  748.92    29.2  742.82    68.2  738.34   136.3  742.23   165.5  741.23
     185  738.84   243.4  728.63   301.9  728.48   379.8  730.52   525.8   731.8
   555.2  724.42   623.6  700.35   672.6  685.46     770  662.64   838.1  657.39
   935.5  656.43   945.2  654.01   974.4   638.9   993.9  630.92  1013.4   629.7
  1139.9   629.7  1159.4  630.62  1217.8  642.02  1266.5   642.2  1295.7  647.33
  1334.6  657.18  1402.8  663.66  1461.6  665.42  1550.1  664.77  1668.2  670.51
#Mann= 3 , 0 , 0
       0      .1       0   993.9    .045       0  1159.4     .07       0
Bank Sta=993.9,1159.4
XS Rating Curve= 0 ,0
Exp/Cntr=0.3,0.1

Type RM Length L Ch R = 1 ,22456.7 ,449.3,440.7,432.1
XS GIS Cut Line= 4
     1542062.742      352876.087     1541767.987      352784.999
     1541158.612      352040.207     1539921.911      352632.685
#Sta/Elev= 30
       0  692.19   250.7  689.67     270  685.67   318.3  671.37   436.2  648.46
     446  647.05   495.1  646.71   504.9  645.46   514.7  641.87   534.4  631.91
   544.2  629.94     554   629.7   701.3   629.7   711.1  630.32   760.2  645.29
   779.8  648.29     829  659.63   848.6  661.28   917.3  661.97  1162.8  659.96
  1378.6   663.9  1633.2  670.72  1701.8   675.1  1780.2  682.59  1829.1  682.36
  1848.7  679.27  1878.1  684.39  1887.9  684.67  2240.5   687.3  2642.1  695.19
#Mann= 3 , 0 , 0
       0      .1       0   544.2    .045       0   701.3     .08       0
Bank Sta=544.2,701.3
XS Rating Curve= 0 ,0
Exp/Cntr=0.3,0.1

Type RM Length L Ch R = 1 ,22015.9 ,264.6,261,257.4
XS GIS Cut Line= 4
     1542085.832      352346.283     1541458.662      351999.061
     1541291.363      351805.559     1539894.133       352577.13
#Sta/Elev= 30
       0  676.12    39.3   679.6    49.1  679.83    58.9   677.9   117.8  648.02
   137.5   642.4   157.1  633.25   166.9  630.42   176.8   629.7   333.9   629.7
   353.5  631.96   392.8  646.82     491  659.55   628.5  654.18   756.2  659.73
   972.7  657.19    1051  660.47  1197.9  664.18  1374.2  664.68  1491.6  667.78
  1540.6  670.67  1658.1  683.25  1677.7  684.42  1795.2  680.34    1805  680.84
  1824.6  684.28    1854  684.88    1991  680.88  2206.5  686.76  2568.8  693.97
#Mann= 3 , 0 , 0
       0      .1       0   166.9    .045       0   333.9     .07       0
#XS Ineff= 2 , 0
                          502.75          664.86
Permanent Ineff=
       F       F
Bank Sta=166.9,333.9
XS Rating Curve= 0 ,0
Exp/Cntr=0.3,0.1

Type RM Length L Ch R = 1 ,21754.9 ,110.4,110.4,110.4
XS GIS Cut Line= 6
     1542131.405      352200.884     1542111.874      352035.953
     1541745.121      351903.575     1541714.739      351784.217
     1541437.901      351660.048     1539911.494      352490.324
#Sta/Elev= 30
       0  675.54    48.8  673.27   146.5  659.35   185.6  651.52   234.3  634.38
   256.5630.0984   263.6   629.7   409.8  631.55   429.3  632.85   448.8  637.11
   526.8  646.33   669.7  653.12   737.9  659.08   874.9  657.62   982.6  661.53
  1061.1  657.18  1139.6   655.8  1237.8  661.85  1581.4  664.61  1699.2  668.46
  1826.8  682.81  1866.1  685.14  1993.7  680.08  2023.2  674.99  2052.6  680.33
  2180.2  674.25  2229.3  675.83  2327.5  682.92  2386.4  684.74  2720.2   688.1
#Mann= 3 , 0 , 0
       0     .09       0   256.5    .045       0   409.8     .09       0
Bank Sta=256.5,409.8
XS Rating Curve= 0 ,0
Exp/Cntr=0.3,0.1

Type RM Length L Ch R = 1 ,21644.5 ,119.6,122.6,125.6
XS GIS Cut Line= 6
     1542225.937      352386.503     1542166.127      351938.297
     1541799.374      351805.919     1541768.992      351686.561
     1541491.806      351562.235     1539866.355      352441.713
#Sta/Elev= 30
       0  678.74      59  674.48   137.6   663.9   186.8  665.54   383.4  651.68
   471.7  652.83   559.4  630.51   578.9  629.33   754.4  632.45   851.6  642.61
   917.9  658.78  1004.4  662.86    1269  655.29  1337.9  661.18  1514.8  654.19
  1622.9  663.48  1790.1  660.95  1976.8  664.59    2085   670.9  2183.3  682.65
  2232.4   685.9  2340.6  684.28  2379.9  679.19  2409.4  671.91  2448.7  675.58
  2556.8  671.51  2615.8  673.73  2694.5  681.49  2763.3  683.72  3117.2  684.96
#Mann= 3 , 0 , 0
       0     .09       0   559.4    .045       0   754.4     .09       0
#XS Ineff= 2 , 0
                         1012.82          668.63
Permanent Ineff=
       F       F
Bank Sta=559.4,754.4
XS Rating Curve= 0 ,0
Exp/Cntr=0.3,0.1

Type RM Length L Ch R = 1 ,21521.9 ,1052,1091.3,1131.2
XS GIS Cut Line= 4
     1542288.957      352321.978     1542278.541       351887.95
     1541525.221      351499.572     1539775.615       352414.63
#Sta/Elev= 30
       0  672.69    77.2  660.41   144.7  655.46   299.1  650.92   541.3  650.46
   619.2  629.66   648.5  626.96   804.3  629.87     853  638.04   882.3  650.81
   901.8  655.78  1047.9  662.49  1184.3  660.62  1281.7  649.66  1370.1  653.65
  1399.6  657.35  1586.2  652.09  1664.8  662.74  1812.1  659.33  2008.6  660.76
  2146.1  667.13    2264  677.54  2381.9  674.81  2489.9  668.57  2568.5  673.38
  2656.9  673.28  2745.3  680.15  2814.1  682.36  3118.6  681.44  3256.2  684.24
#Mann= 3 , 0 , 0
       0     .09       0   619.2    .045       0   804.3     .08       0
#XS Ineff= 2 , 0
                         1086.54          670.66
Permanent Ineff=
       F       F
Bank Sta=619.2,804.3
XS Rating Curve= 0 ,0
Exp/Cntr=0.3,0.1

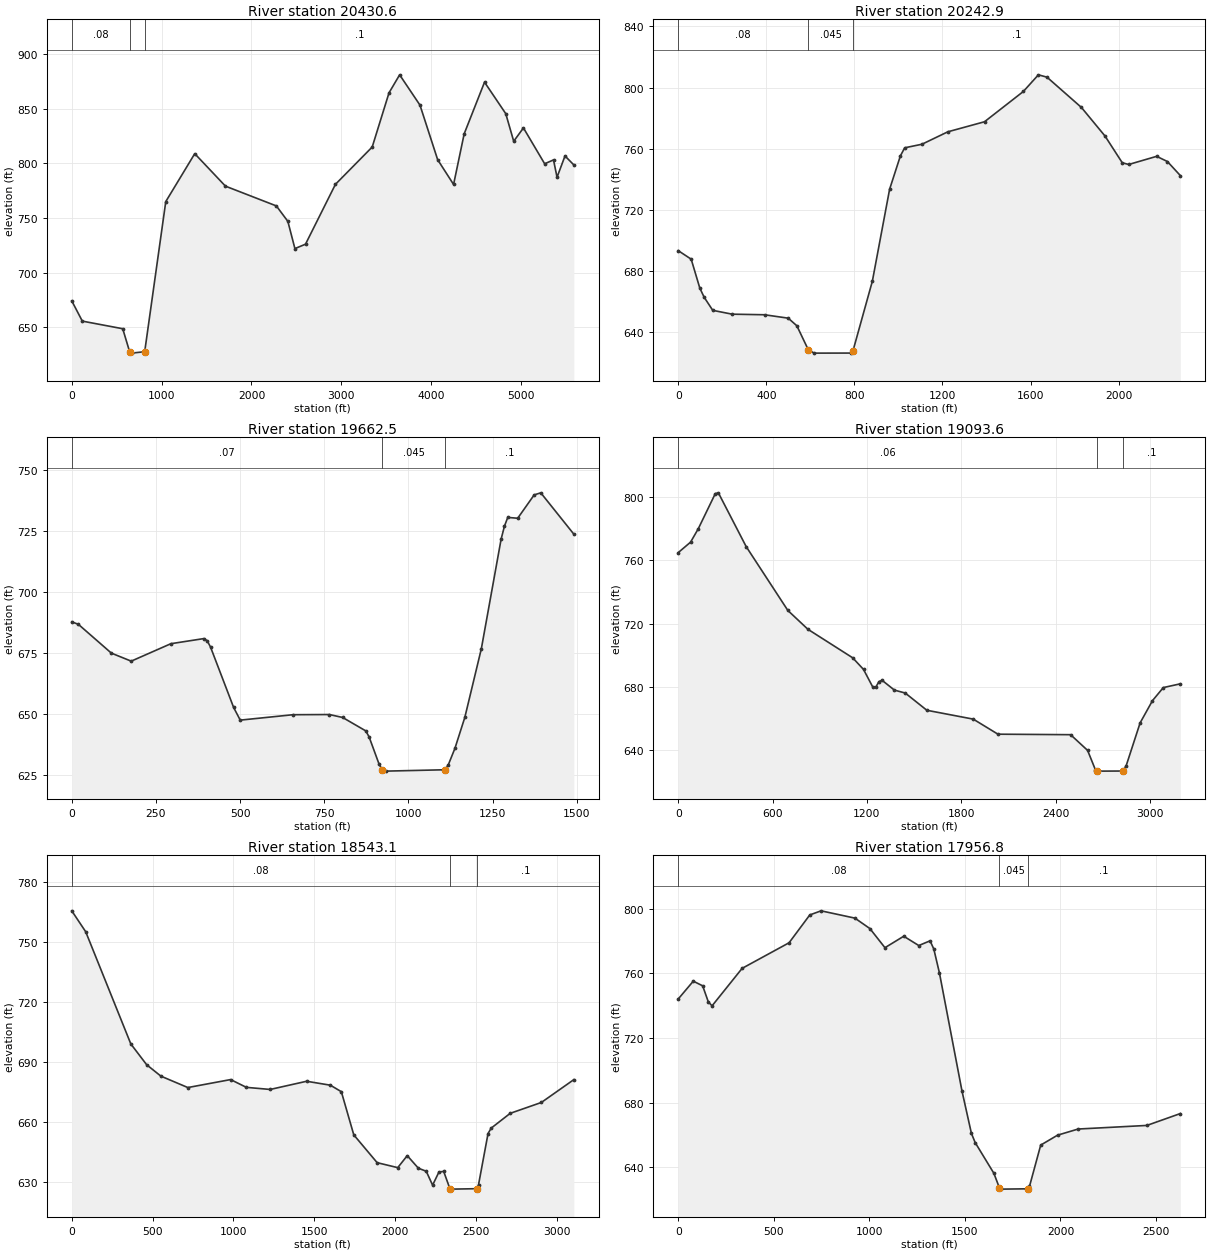
Type RM Length L Ch R = 1 ,20430.6 ,186.9,187.6,187.9
XS GIS Cut Line= 6
     1542330.103      352337.892     1543048.853      351473.309
     1542292.921       350616.42     1541723.477      350637.253
     1541285.977      350623.365     1538973.477      350637.253
#Sta/Elev= 30
       0   674.3   117.3  655.78     567  648.81   645.3   627.4   664.8   626.5
   811.5  627.79  1046.1  765.11  1368.5  808.94  1710.3  779.22  2276.8  761.14
  2404.5  747.04  2483.1  722.12    2601  726.14  2934.1  780.89  3343.4  815.04
  3530.4   864.6  3648.5  881.05  3874.8  853.34  4071.6  803.42  4248.8  780.78
  4366.8  827.09  4593.2  874.33  4829.4  845.54  4917.9  820.28  5026.2  832.48
  5262.3  799.69  5360.8  803.23  5400.1  787.38  5488.7  806.85  5587.1  798.63
#Mann= 3 , 0 , 0
       0     .08       0   645.3    .045       0   811.5      .1       0
Bank Sta=645.3,811.5
XS Rating Curve= 0 ,0
Exp/Cntr=0.3,0.1

Type RM Length L Ch R = 1 ,20242.9 ,581,580.4,579.8
XS GIS Cut Line= 3
     1542476.457      352460.867     1543456.011      351237.171
      1543306.81      350540.031
#Sta/Elev= 30
       0  693.46    58.8  687.89      98  668.99   117.6  663.04   156.8  654.45
   244.9  651.95   391.9  651.57   499.6  649.34   538.8  644.36   590.5628.7438
   617.2   626.5   783.7  626.54   793.5   627.9   881.7   673.5   960.1  733.62
  1009.1   755.4  1028.6  760.65    1107  762.98  1224.6  771.11  1391.1  777.67
  1567.5  797.46  1635.8  808.33  1674.9   806.8  1831.2  787.02  1938.6  768.31
  2016.7  750.89    2046  749.75    2173  755.08  2221.8  751.68  2280.4  742.52
#Mann= 3 , 0 , 0
       0     .08       0   590.5    .045       0   793.5      .1       0
Bank Sta=590.5,793.5
XS Rating Curve= 0 ,0
Exp/Cntr=0.3,0.1

Type RM Length L Ch R = 1 ,19662.5 ,568.9,568.9,568.9
XS GIS Cut Line= 2
     1542736.737      353102.707     1543639.652      351915.728
#Sta/Elev= 30
       0  687.68    19.6  686.66   117.7  674.85   176.6  671.57   294.4  678.72
   392.5  680.82   402.3  679.91   412.1  677.37   480.8  652.59   500.4   647.4
   657.4  649.62   765.3  649.69   804.6  648.49   873.2     643     883   640.6
   912.5   629.5   922.3  626.92   932.1   626.5  1108.7  627.06  1118.5  629.09
  1138.2  635.85  1167.6  648.54  1216.6  676.64  1275.5  721.66  1285.3   726.9
  1295.1  730.48  1324.6  730.13  1373.6  739.71  1393.2  740.55  1491.4  723.61
#Mann= 3 , 0 , 0
       0     .07       0   922.3    .045       0  1108.7      .1       0
Bank Sta=922.3,1108.7
XS Rating Curve= 0 ,0
Exp/Cntr=0.3,0.1

Type RM Length L Ch R = 1 ,19093.6 ,550.4,550.6,550.7
XS GIS Cut Line= 3
     1542842.744      355056.296     1542857.541      353878.074
     1544080.624      352276.839
#Sta/Elev= 30
       0  764.91    78.6  771.56   127.6  780.06   235.7  802.28   255.3  802.78
     432  768.74   697.2  728.27   824.8  716.34  1109.6  698.27  1178.3  690.93
  1237.3  679.75    1257  679.82  1276.6  683.18  1296.3  684.04  1374.9  677.81
  1443.7  675.97  1581.3  665.04  1876.2  659.44  2033.4   649.9  2495.4  649.58
  2603.5  639.64  2652.6  627.49  2662.5   626.6  2672.3   626.5  2829.6  626.57
  2849.2  630.03  2937.7  657.09  3016.3  671.16  3085.1  679.42  3193.2   681.8
#Mann= 3 , 0 , 0
       0     .06       0  2662.5    .045       0  2829.6      .1       0
Bank Sta=2662.5,2829.6
XS Rating Curve= 0 ,0
Exp/Cntr=0.3,0.1

Type RM Length L Ch R = 1 ,18543.1 ,603.4,586.3,569.2
XS GIS Cut Line= 6
     1544067.571      355244.954     1543928.682      354949.815
      1543902.64      353656.412     1543920.001      353387.315
     1544453.855      352697.211     1544228.161      352436.794
#Sta/Elev= 30
       0  765.46    86.3     755   365.4     699   463.4  688.61   551.6  682.91
   718.2  677.22   982.8   681.2  1080.8  677.31  1227.8  676.27  1453.2  680.36
  1600.2  678.39    1668  675.15    1745  653.59  1889.5  639.71    2017  637.23
  2075.8  643.22  2144.4  636.96  2193.4  635.41  2232.6  628.48  2271.8  635.03
  2301.2  635.36  2340.5  626.52  2350.3   626.5  2507.1  626.72  2516.9  628.72
  2575.7  654.25  2595.3  656.97    2713  664.35  2905.6  669.77  3106.6  681.18
#Mann= 3 , 0 , 0
       0     .08       0  2340.5    .045       0  2507.1      .1       0
Bank Sta=2340.5,2507.1
XS Rating Curve= 0 ,0
Exp/Cntr=0.3,0.1

Type RM Length L Ch R = 1 ,17956.8 ,573.3,551.7,530
XS GIS Cut Line= 4
     1545217.744      354847.963     1544810.659      353379.269
     1544755.971      352842.811      1544367.95      352433.957
#Sta/Elev= 30
       0  744.07    78.7  755.08   127.8  752.21   157.3  742.31     177  739.83
   334.3  763.01   580.1  778.84   688.3  796.03   747.3  798.58   924.3  794.07
  1002.9   787.6  1081.6  775.78  1179.9  782.87  1258.6  777.12  1317.6  780.03
  1337.2  774.98  1366.7  760.14  1484.7  687.14  1533.9  661.01  1553.5  655.32
  1651.5  636.29  1680.9  627.16  1690.7   626.5    1828   626.7  1837.8  628.18
  1896.6  653.73  1984.9  659.87  2092.5  663.66    2452  665.88    2627  673.22
#Mann= 3 , 0 , 0
       0     .08       0  1680.9    .045       0    1828      .1       0
Bank Sta=1680.9,1828
XS Rating Curve= 0 ,0
Exp/Cntr=0.3,0.1

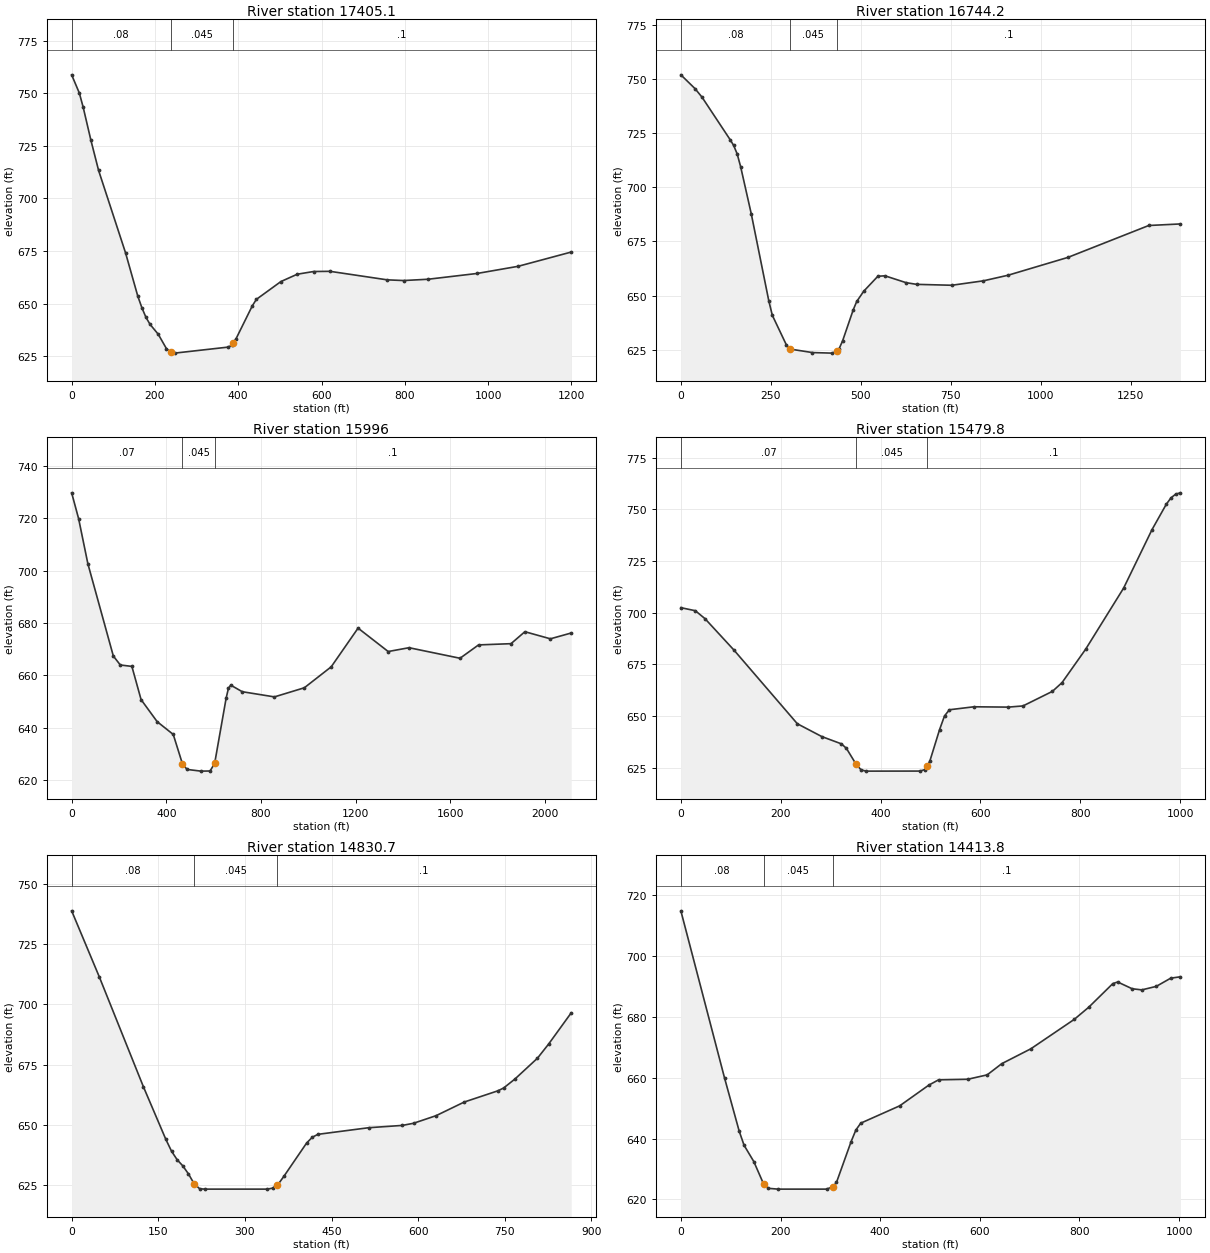
Type RM Length L Ch R = 1 ,17405.1 ,673.1,660.9,648.6
XS GIS Cut Line= 3
     1545383.575      352957.394     1545300.242      352858.436
     1544366.301       352335.78
#Sta/Elev= 30
       0  758.72    18.5  750.04    27.7  743.31    46.2  727.67    64.7  713.29
   129.4  674.15   158.8  653.58   168.6  648.07   178.5  643.45   188.3  640.14
   207.9  635.46   227.6  628.62   237.6626.8327   247.2  626.48   374.8  629.32
   384.7  630.18   387.6631.0767   394.5  633.21   433.8  648.95   443.6  652.03
   502.5  660.49   541.8  663.98     581  665.26   620.3  665.35   757.8   661.3
     797  660.97     856  661.59   973.8  664.34    1072  667.73  1199.6  674.51
#Mann= 3 , 0 , 0
       0     .08       0   237.6    .045       0   387.6      .1       0
Bank Sta=237.6,387.6
XS Rating Curve= 0 ,0
Exp/Cntr=0.3,0.1

Type RM Length L Ch R = 1 ,16744.2 ,752.1,748.3,744.4
XS GIS Cut Line= 2
     1545627.362      352116.596     1544239.536      352162.398
#Sta/Elev= 30
       0  751.92    39.1  745.59    58.7  741.63   136.9  721.99   146.7  719.33
   156.5  715.41   166.2  709.47   195.6  687.81   244.5   647.5   254.2  640.88
   293.4  627.16   303.1  625.28   365.8  623.66   420.5   623.4   433.3624.2374
     440  625.46   449.8  629.18   479.2  643.43   488.9  647.28   508.5  652.02
   547.6   658.9   567.2  659.11   625.8  655.95   655.2  655.16     753  654.74
     841  656.79   909.4  659.37  1075.7   667.6  1300.6  682.34  1388.6  683.06
#Mann= 3 , 0 , 0
       0     .08       0   303.1    .045       0   433.3      .1       0
Bank Sta=303.1,433.3
XS Rating Curve= 0 ,0
Exp/Cntr=0.3,0.1

Type RM Length L Ch R = 1 ,15996   ,515.5,516.2,516.8
XS GIS Cut Line= 5
     1545656.898      351205.715     1545436.711      351333.159
     1544723.268      351479.953     1544504.518       351419.19
     1543928.256        352110.9
#Sta/Elev= 30
       0  729.72    29.4  719.86    68.5  702.64   176.1  667.37   205.5  663.95
   254.4  663.41   293.3  650.72   361.2   642.3   429.2  637.41   468.1  626.15
   487.5  624.05   545.8   623.4   584.6  623.45     604  626.34   652.6  651.29
   662.3  655.06     672  656.25   720.6  653.74   856.5  651.76   982.8  655.24
  1096.3  663.25  1209.8  678.03    1337  669.09  1425.1  670.55  1640.4  666.52
  1718.7  671.62  1855.7  672.09  1914.4  676.66  2022.1  673.95  2110.1  676.17
#Mann= 3 , 0 , 0
       0     .07       0   468.1    .045       0     604      .1       0
Bank Sta=468.1,604
XS Rating Curve= 0 ,0
Exp/Cntr=0.3,0.1

Type RM Length L Ch R = 1 ,15479.8 ,655.8,649,642.3
XS GIS Cut Line= 4
     1545433.402      350725.537     1545325.763      350836.648
     1544735.485      350940.815      1544492.43      350982.481
#Sta/Elev= 30
       0  702.43      29  700.96    48.3  697.13   106.4  681.92   233.3  646.31
   282.4   640.1   321.7  636.58   331.6  634.42   351.2  626.66     361  624.04
   370.9   623.4     479  623.43   488.8  624.15   493.3625.9868   498.6  628.15
   518.3  643.52   528.1  650.08   537.9  653.07     587  654.51   655.8  654.35
   685.3  654.92   744.3  661.97   763.6  666.21     811  682.41   886.9   711.9
   943.8  740.18   972.2  752.37   981.7  755.52   991.2  757.33  1000.7  757.96
#Mann= 3 , 0 , 0
       0     .07       0   351.2    .045       0   493.3      .1       0
Bank Sta=351.2,493.3
XS Rating Curve= 0 ,0
Exp/Cntr=0.3,0.1

Type RM Length L Ch R = 1 ,14830.7 ,420,417,413.9
XS GIS Cut Line= 3
     1545155.624      350131.787     1545044.513      350187.342
     1544384.791      350524.148
#Sta/Elev= 30
       0   738.8    47.8  711.46   124.2  665.88   163.2  643.98     173  639.11
   182.7  635.58   192.4  633.07   202.2  629.73   211.9  625.71   221.7  623.54
   231.4   623.4   338.6   623.4   348.4  623.82   355.9625.1808   358.1  625.58
   367.9  628.86   406.9  642.53   416.6   644.9   426.4  646.12   514.1  648.86
   572.6  649.82     592  650.71     631  653.86   679.8  659.52   738.2  664.18
     748  665.34   767.5  669.05   806.5  677.68     826   683.6     865   696.5
#Mann= 3 , 0 , 0
       0     .08       0   211.9    .045       0   355.9      .1       0
Bank Sta=211.9,355.9
XS Rating Curve= 0 ,0
Exp/Cntr=0.3,0.1

Type RM Length L Ch R = 1 ,14413.8 ,337,332.3,327.6
XS GIS Cut Line= 3
      1544867.43       349777.62     1544322.291      350156.092
     1544142.343      350443.419
#Sta/Elev= 30
       0  714.72    87.8   659.8   117.1  642.42   126.9  637.78   146.4  632.45
   165.9  625.15   175.7  623.66   195.2   623.4   292.8   623.4   305.5624.2269
   312.3  625.58   341.6  638.94   351.3  642.81   361.1  645.05   439.2  650.73
   497.7  657.53   517.2  659.26   575.8  659.45   614.8  660.89   644.1  664.57
   702.4  669.44   789.6   679.1   818.6  683.08     867  690.84   876.7  691.37
   905.8  689.15   925.2  688.78   954.2  689.93   983.3  692.63  1002.7  693.07
#Mann= 3 , 0 , 0
       0     .08       0   165.9    .045       0   305.5      .1       0
Bank Sta=165.9,305.5
XS Rating Curve= 0 ,0
Exp/Cntr=0.3,0.1