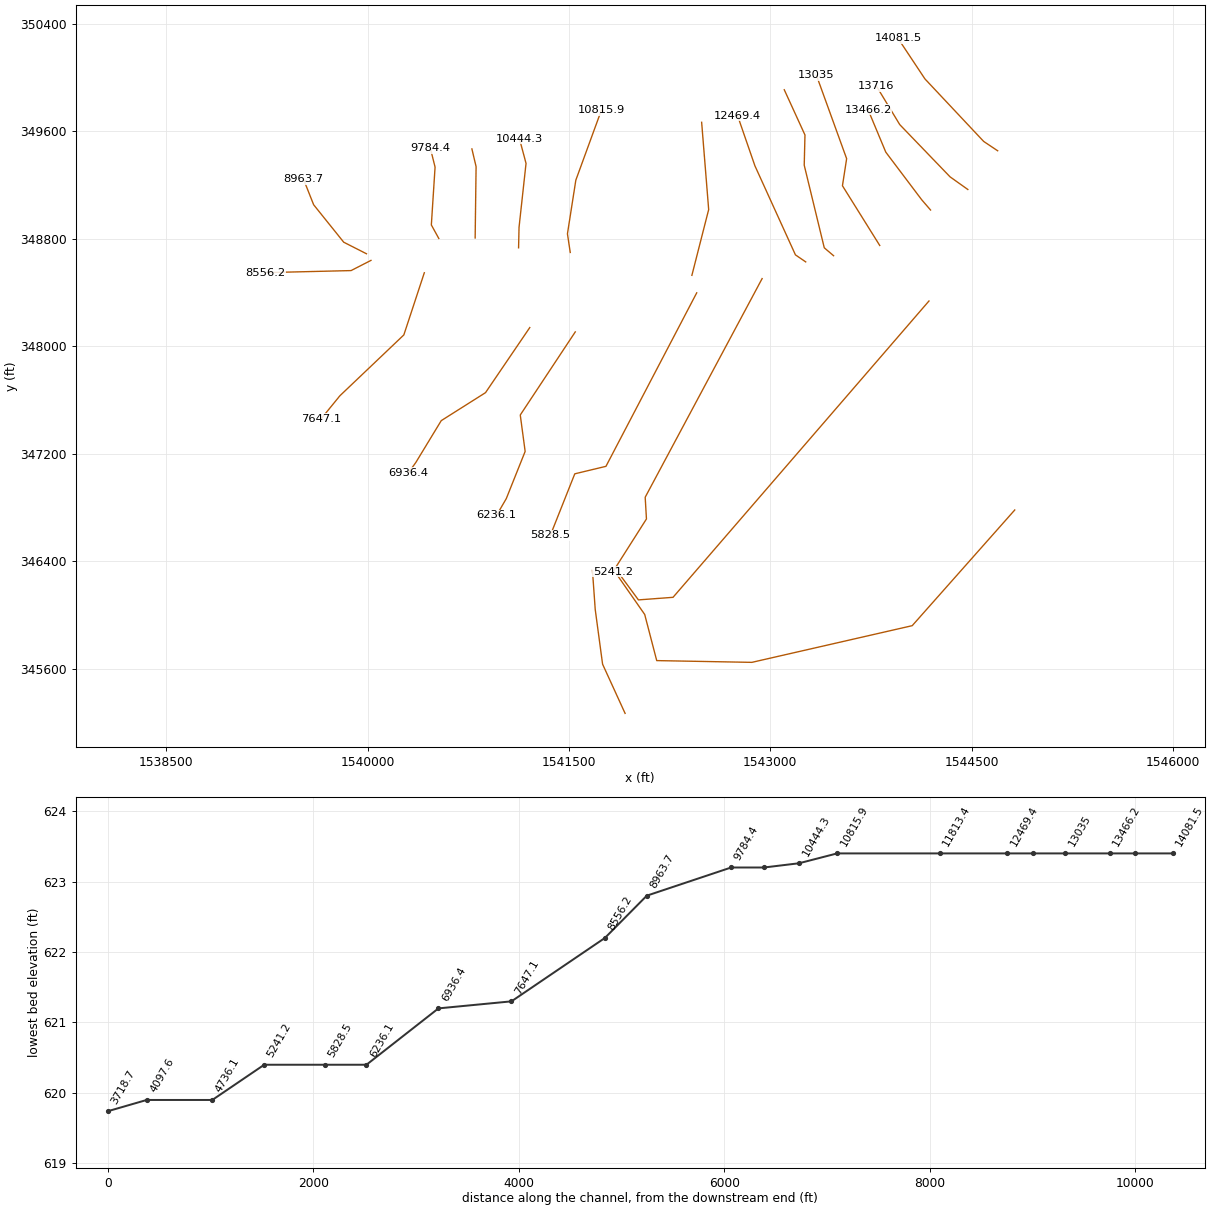
HEC-RAS study MDISLCRK1.prj: MDISLCRK1

--- MDISLCRK1.g01 (geometry) --- (continued)

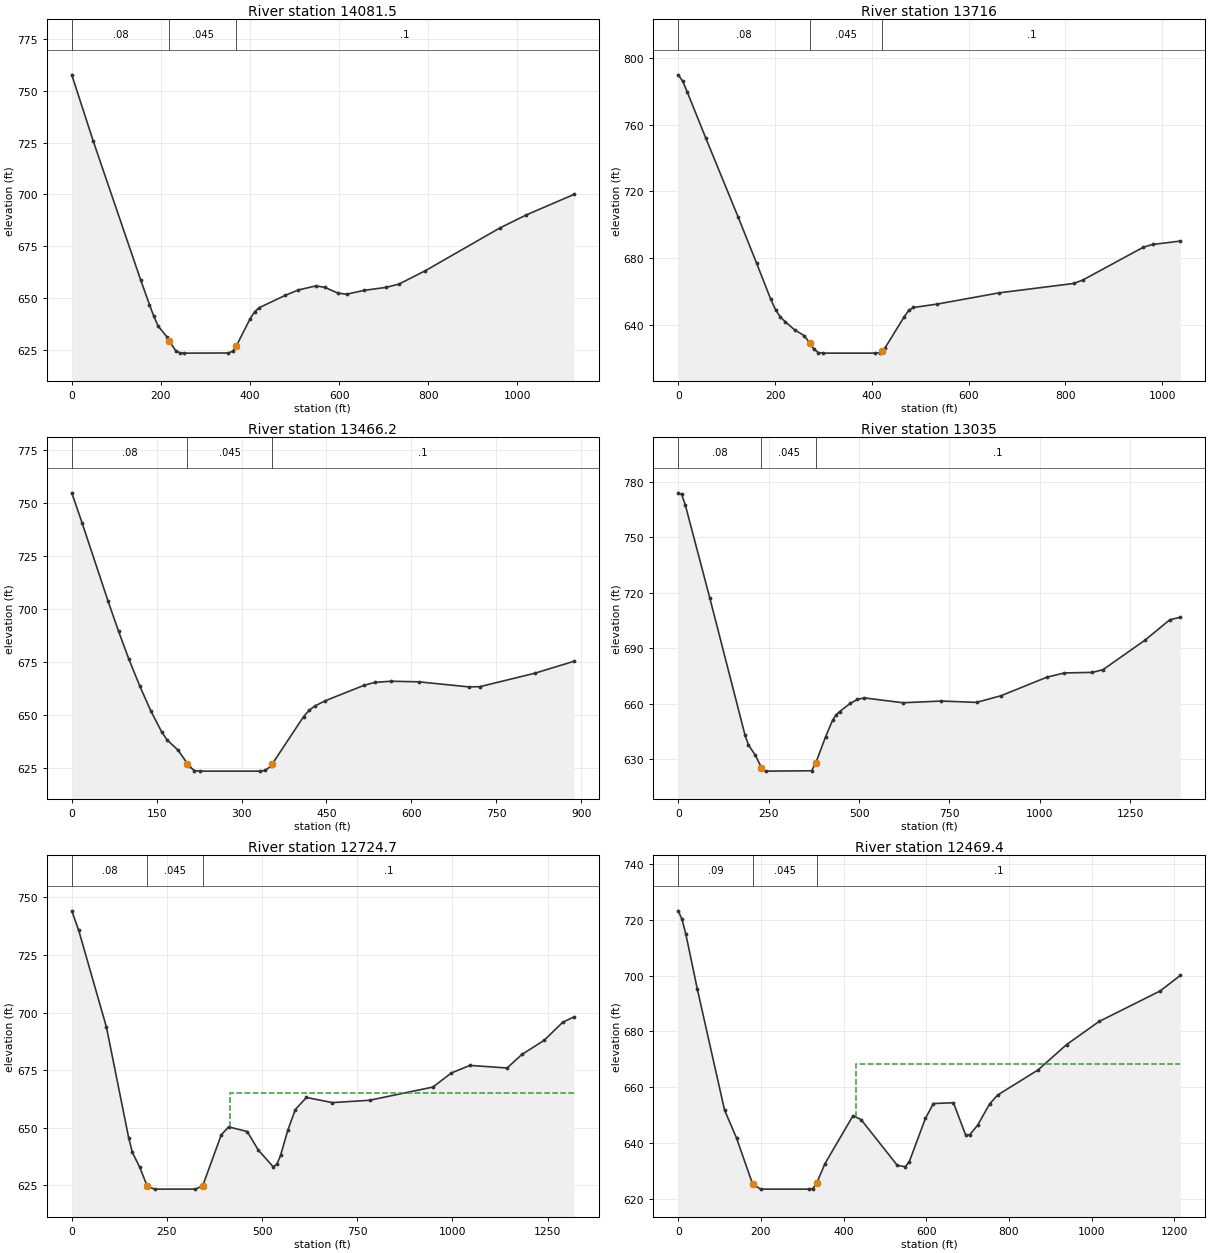
Type RM Length L Ch R = 1 ,14081.5 ,365.2,365.5,365.8
XS GIS Cut Line= 4
     1544693.818      349454.703     1544589.652      349524.148
     1544152.152      349989.426     1543951.371      350291.509
#Sta/Elev= 30
       0   757.7    48.2  725.72   154.7  658.64   174.3  646.85   184.2  641.13
     194   636.4   213.6  631.21     219629.2538   233.3  624.51   243.1  623.51
   252.9   623.4   351.2  623.47     361  624.28     369626.7126   400.3  640.05
   410.1  643.31     420  645.26   478.9  651.27   508.4  653.89   547.7  655.83
   567.3  655.19   596.8   652.4   616.5  651.82   655.8  653.68   704.9  655.12
   734.4  656.74   793.3  663.16   959.9  683.72  1018.7  689.97  1126.6  699.97
#Mann= 3 , 0 , 0
       0     .08       0     219    .045       0     369      .1       0
Bank Sta=219,369
XS Rating Curve= 0 ,0
Exp/Cntr=0.3,0.1

Type RM Length L Ch R = 1 ,13716   ,252.5,249.7,247
XS GIS Cut Line= 4
     1544471.596      349166.509     1544339.652      349260.259
     1543964.652      349649.148      1543790.78      349935.606
#Sta/Elev= 30
       0  789.69     9.5  785.72      19  779.17    57.1  751.78   123.8  704.69
   161.9  677.14   191.3  655.46   201.2  649.23     211  645.01   220.8  642.21
   240.4  637.32   260.1  633.87   271.5629.6816   279.7     626   289.6  623.71
   299.4   623.4   407.4   623.4   417.2  623.74   421.5624.9171   427.1  626.45
   466.4  644.93   476.2  648.98     486  650.67   535.1  652.72   662.8  659.41
     817  665.03   836.1  667.13   960.6  686.66   979.8  688.32  1037.2  690.36
#Mann= 3 , 0 , 0
       0     .08       0   271.5    .045       0   421.5      .1       0
Bank Sta=271.5,421.5
XS Rating Curve= 0 ,0
Exp/Cntr=0.3,0.1

Type RM Length L Ch R = 1 ,13466.2 ,433.1,431.2,429.3
XS GIS Cut Line= 4
     1544193.818      349013.731     1544127.846       349090.12
     1543860.485      349444.287     1543728.541      349760.259
#Sta/Elev= 30
       0  754.63    18.4  740.32    64.2  703.51    82.6   689.4   100.9  676.21
   120.2  663.51   139.5  651.88   158.8  641.94   168.5   638.1   187.8  633.31
   204.4626.9006     207  625.82   216.7  623.66   226.3   623.4   332.5   623.4
   342.1  623.73   351.8  625.83   354.4626.8402   409.6  649.11   419.3  652.08
   428.9  654.02   448.2  656.62   515.8   663.8     535  665.24   564.2  665.79
   613.2  665.51   701.2  663.13   720.8  663.21   818.6   669.6   887.1  675.18
#Mann= 3 , 0 , 0
       0     .08       0   204.4    .045       0   354.4      .1       0
Bank Sta=204.4,354.4
XS Rating Curve= 0 ,0
Exp/Cntr=0.3,0.1

Type RM Length L Ch R = 1 ,13035   ,317.7,310.4,303.1
XS GIS Cut Line= 4
     1543815.346      348749.842     1543537.568      349194.287
     1543568.818      349395.676     1543343.703      350016.565
#Sta/Elev= 30
       0  774.08     9.7  773.18    19.4  767.61    87.4  717.04   184.4  643.12
   194.1  637.62   213.5  631.92   230.1625.3349   232.9  624.29   242.6   623.4
   368.8   623.6   380.1627.6836   407.6  642.05     427  651.05   436.8  653.91
   446.5  655.67   475.6  660.06     495   662.2   514.4  663.06   621.2  660.42
   727.9  661.35     825  660.62     893  664.26  1019.3  674.26  1067.8  676.56
  1145.5  676.87  1174.7  678.33  1291.2  694.38  1359.2  705.33  1388.4  706.72
#Mann= 3 , 0 , 0
       0     .08       0   230.1    .045       0   380.1      .1       0
Bank Sta=230.1,380.1
XS Rating Curve= 0 ,0
Exp/Cntr=0.3,0.1

Type RM Length L Ch R = 1 ,12724.7 ,251,255.3,259.5
XS GIS Cut Line= 6
     1543471.596      348673.453     1543402.152      348732.481
     1543252.846      349347.065      1543255.99       349474.92
     1543258.382      349572.169     1543104.119      349908.926
#Sta/Elev= 30
       0  744.14    18.2  735.68    91.1  693.67   149.5   645.7   159.2  639.37
   178.7  632.86   198.2   624.7   217.6   623.4   324.7   623.4   344.1  624.84
   392.8  646.97   412.2   650.4   460.9   648.4   490.1  640.35     529  633.14
   538.7  634.14   548.5  637.99   567.9  649.09   587.4  657.94   616.6  663.17
   684.7  660.94   782.6  661.96   948.8  667.68   997.5  673.81  1046.2  677.08
  1143.7  675.96  1182.7  681.81  1241.2  687.98  1289.9  695.78  1319.2   698.1
#Mann= 3 , 0 , 0
       0     .08       0   198.2    .045       0   344.1      .1       0
#XS Ineff= 2 , 0
                          415.38          665.06
Permanent Ineff=
       F       F
Bank Sta=198.2,344.1
XS Rating Curve= 0 ,0
Exp/Cntr=0.3,0.1

Type RM Length L Ch R = 1 ,12469.4 ,671.3,656,640.7
XS GIS Cut Line= 4
     1543263.842      348627.676     1543187.453      348679.759
     1542885.369      349342.954     1542756.897      349714.481
#Sta/Elev= 30
       0  723.32     9.2  720.24    18.5  714.88    46.2   695.2   111.9  651.85
     141  641.72   179.9  625.22   199.3   623.4   315.9   623.4   325.7  623.62
   335.4  625.74   354.8  632.53   422.8  649.79   442.3  648.36   529.7  631.96
   549.1  631.43   558.9  633.29   597.7  648.76   617.2  654.14   665.7  654.41
   694.9  642.92   704.6  642.87     724  646.32   753.2  654.03   772.6  657.19
   870.4  666.22   939.1  675.28  1017.8  683.59  1165.2  694.53  1214.3  700.12
#Mann= 3 , 0 , 0
       0     .09       0   179.9    .045       0   335.4      .1       0
#XS Ineff= 2 , 0
                          429.49           668.4
Permanent Ineff=
       F       F
Bank Sta=179.9,335.4
XS Rating Curve= 0 ,0
Exp/Cntr=0.3,0.1

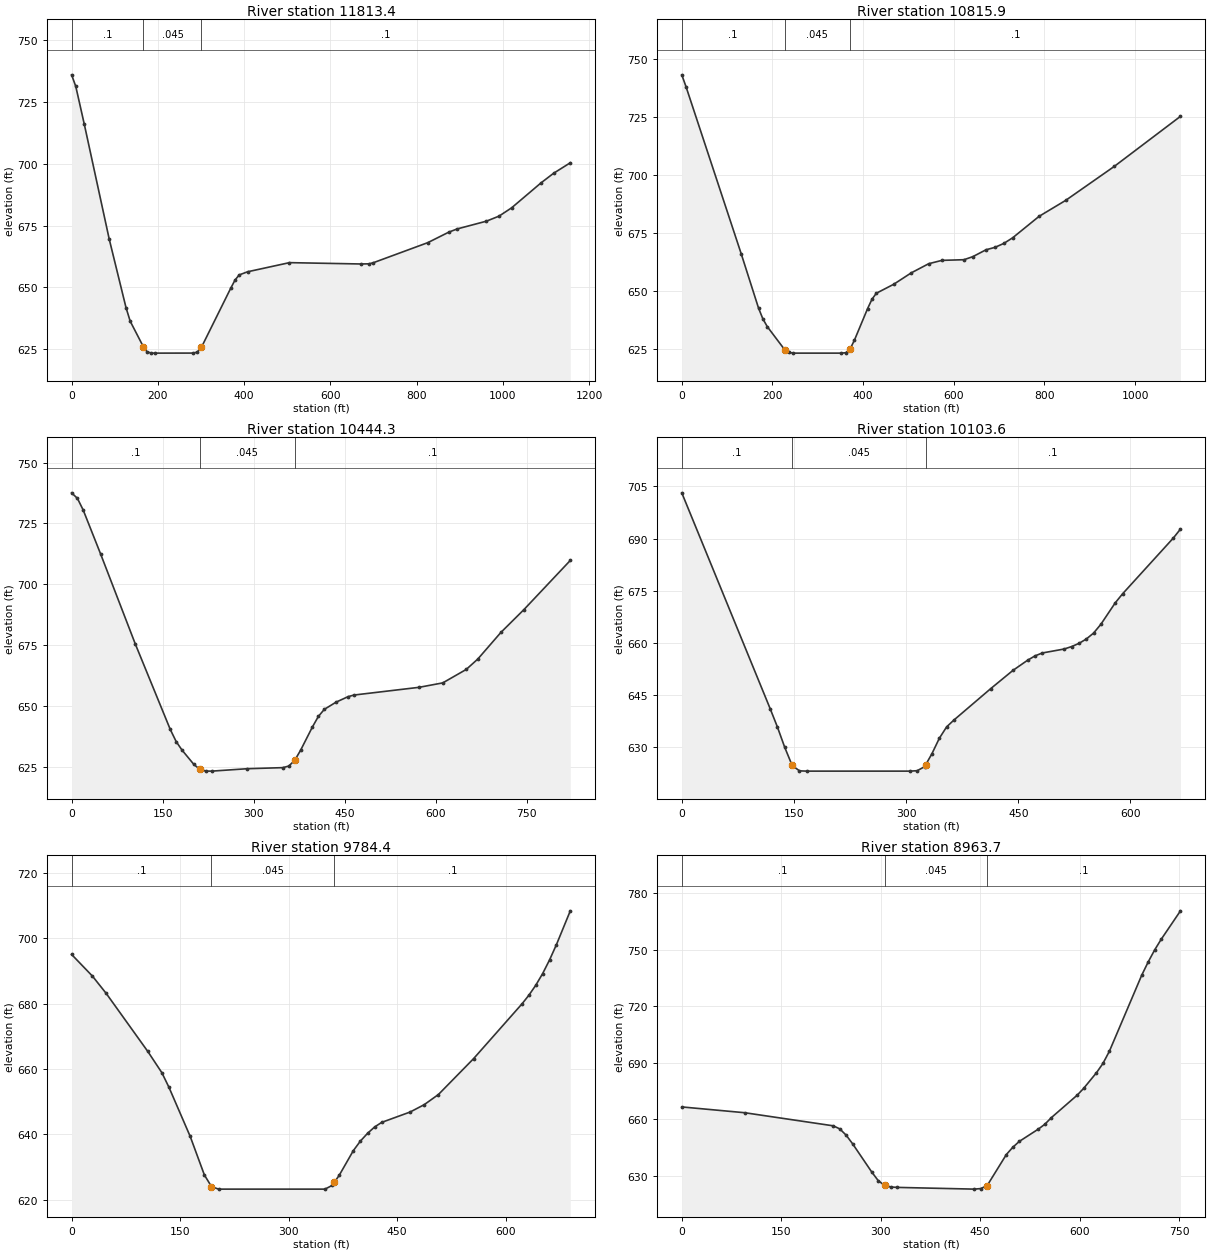
Type RM Length L Ch R = 1 ,11813.4 ,995.3,997.5,999.5
XS GIS Cut Line= 3
     1542416.041       348527.62     1542541.041      349017.203
     1542488.697      349666.509
#Sta/Elev= 30
       0  736.06     9.7  731.36    29.2  716.25    87.4  669.45   126.3  641.75
     136  636.28   166.6 625.931   174.9  623.98   184.6  623.41   194.3   623.4
   281.8  623.42   291.5  623.82   301.2  625.78   369.2  649.71     379  652.96
   388.7  655.06   408.1  656.33   505.3  660.03   670.6  659.49     690  659.55
   699.7  659.99   826.1  668.12   874.8  672.37   894.2  673.67   962.2  676.82
   991.4  678.86  1020.6  682.22  1088.6  692.29  1117.8  696.19  1156.7  700.46
#Mann= 3 , 0 , 0
       0      .1       0   166.6    .045       0   301.2      .1       0
Bank Sta=166.6,301.2
XS Rating Curve= 0 ,0
Exp/Cntr=0.3,0.1

Type RM Length L Ch R = 1 ,10815.9 ,370.6,371.6,372.6
XS GIS Cut Line= 4
     1541509.791      348697.759     1541488.957      348836.648
     1541551.457      349235.953     1541742.169      349757.655
#Sta/Elev= 30
       0  743.03     9.4   737.9   131.1   666.1   169.3  642.77   178.9  638.11
   188.6  634.79     227  624.87   236.7  623.67   246.3   623.4   352.2   623.4
   361.8  623.58   371.4  625.19     381  629.05   409.9  642.54   419.5  646.54
   429.1  649.13   467.6  653.01   506.1  657.89   544.6  661.83   573.8  663.27
   622.6  663.56   642.1  664.88   671.3  667.84   690.8  668.86   710.3  670.55
   729.8  672.96   788.2   682.2   846.7  689.04   953.9  703.64  1100.1  725.19
#Mann= 3 , 0 , 0
       0      .1       0     227    .045       0   371.4      .1       0
Bank Sta=227,371.4
XS Rating Curve= 0 ,0
Exp/Cntr=0.3,0.1

Type RM Length L Ch R = 1 ,10444.3 ,338.5,340.7,342.8
XS GIS Cut Line= 4
     1541124.922       348732.36     1541128.395      348885.138
     1541180.478      349360.832     1541131.318      349544.981
#Sta/Elev= 30
       0  737.55     9.6  735.27    19.1  730.49    47.8  712.45   105.1  675.41
   162.6   640.4   172.4  635.38   182.1  631.87   201.6     626   211.4  623.95
   221.2  623.28     231  623.26   289.5  624.25   348.1  624.69   357.9  625.33
   367.7  627.67   377.4  631.81     397  641.43   406.7   645.7   416.5  648.62
     436   651.6   455.6  653.83   465.3   654.5   572.8  657.68   611.8   659.5
   650.4  665.01   669.5  669.28   707.6  680.22   745.7  689.63     822  709.79
#Mann= 3 , 0 , 0
       0      .1       0   211.4    .045       0   367.7      .1       0
Bank Sta=211.4,367.7
XS Rating Curve= 0 ,0
Exp/Cntr=0.3,0.1

Type RM Length L Ch R = 1 ,10103.6 ,320.4,319.2,318.1
XS GIS Cut Line= 3
     1540801.457      348805.398     1540808.402      349336.648
     1540777.152      349468.592
#Sta/Elev= 30
       0  703.15   118.1  641.19   127.9  635.87   137.7  630.02   147.6  624.83
   157.4  623.28   167.3   623.2     305   623.2   314.8  623.32   324.7  624.48
   326.2625.0479   334.5  628.19   344.4  632.63   354.2  635.92     364  637.89
   413.2  646.91   442.8  652.13   462.4  655.05   472.3   656.3   482.1  657.14
   511.6  658.29   521.5     659   531.3  659.91     541  661.16   550.7  662.86
   560.4  665.37   579.7  671.56   589.4  674.12   657.2  690.13   666.9  692.74
#Mann= 3 , 0 , 0
       0      .1       0   147.6    .045       0   326.2      .1       0
Bank Sta=147.6,326.2
XS Rating Curve= 0 ,0
Exp/Cntr=0.3,0.1

Type RM Length L Ch R = 1 ,9784.4  ,803.9,820.8,837.4
XS GIS Cut Line= 4
     1540530.624      348801.926     1540475.068       348902.62
     1540502.846      349333.176     1540468.124      349472.065
#Sta/Elev= 30
       0  695.03    28.8   688.4    47.9  683.09   105.4  665.33   124.8  658.84
   134.6  654.38     164  639.33   183.6  627.54   193.4  623.98   203.2   623.2
   350.3   623.2   360.2  624.32   363.3625.2974     370  627.41   389.6  634.99
   399.4  637.92   409.2  640.27     419  642.22   428.8  643.63     468  646.79
   487.6  649.05   507.2  652.15     556  663.17   622.8   679.9   632.4  682.57
   641.9  685.62   651.4  689.19     661  693.39   670.5  698.07   689.6  708.38
#Mann= 3 , 0 , 0
       0      .1       0   193.4    .045       0   363.3      .1       0
Bank Sta=193.4,363.3
XS Rating Curve= 0 ,0
Exp/Cntr=0.3,0.1

Type RM Length L Ch R = 1 ,8963.7  ,386.6,407.5,428.4
XS GIS Cut Line= 4
     1539991.562       348688.21     1539822.291      348774.148
     1539598.332      349052.794     1539522.812      349242.898
#Sta/Elev= 30
       0  666.49    94.9  663.41   228.5  656.44   238.2  654.82   247.8  651.49
   257.5  646.93   286.5  631.85   296.1  627.35   305.8  624.75   315.4  623.92
   325.1  623.72     441   622.8   450.7  623.09   460.4  624.67   489.4   641.2
     499  645.01   508.7  648.12   537.7  654.73   547.3  657.25   557.1  660.76
     596  672.69   605.8  676.31   625.2  684.65     635   689.6   644.7  696.08
   693.4  736.45   703.2  743.54   712.9  749.89   722.7  755.52   751.9  770.72
#Mann= 3 , 0 , 0
       0      .1       0   305.8    .045       0   460.4      .1       0
Bank Sta=305.8,460.4
XS Rating Curve= 0 ,0
Exp/Cntr=0.3,0.1

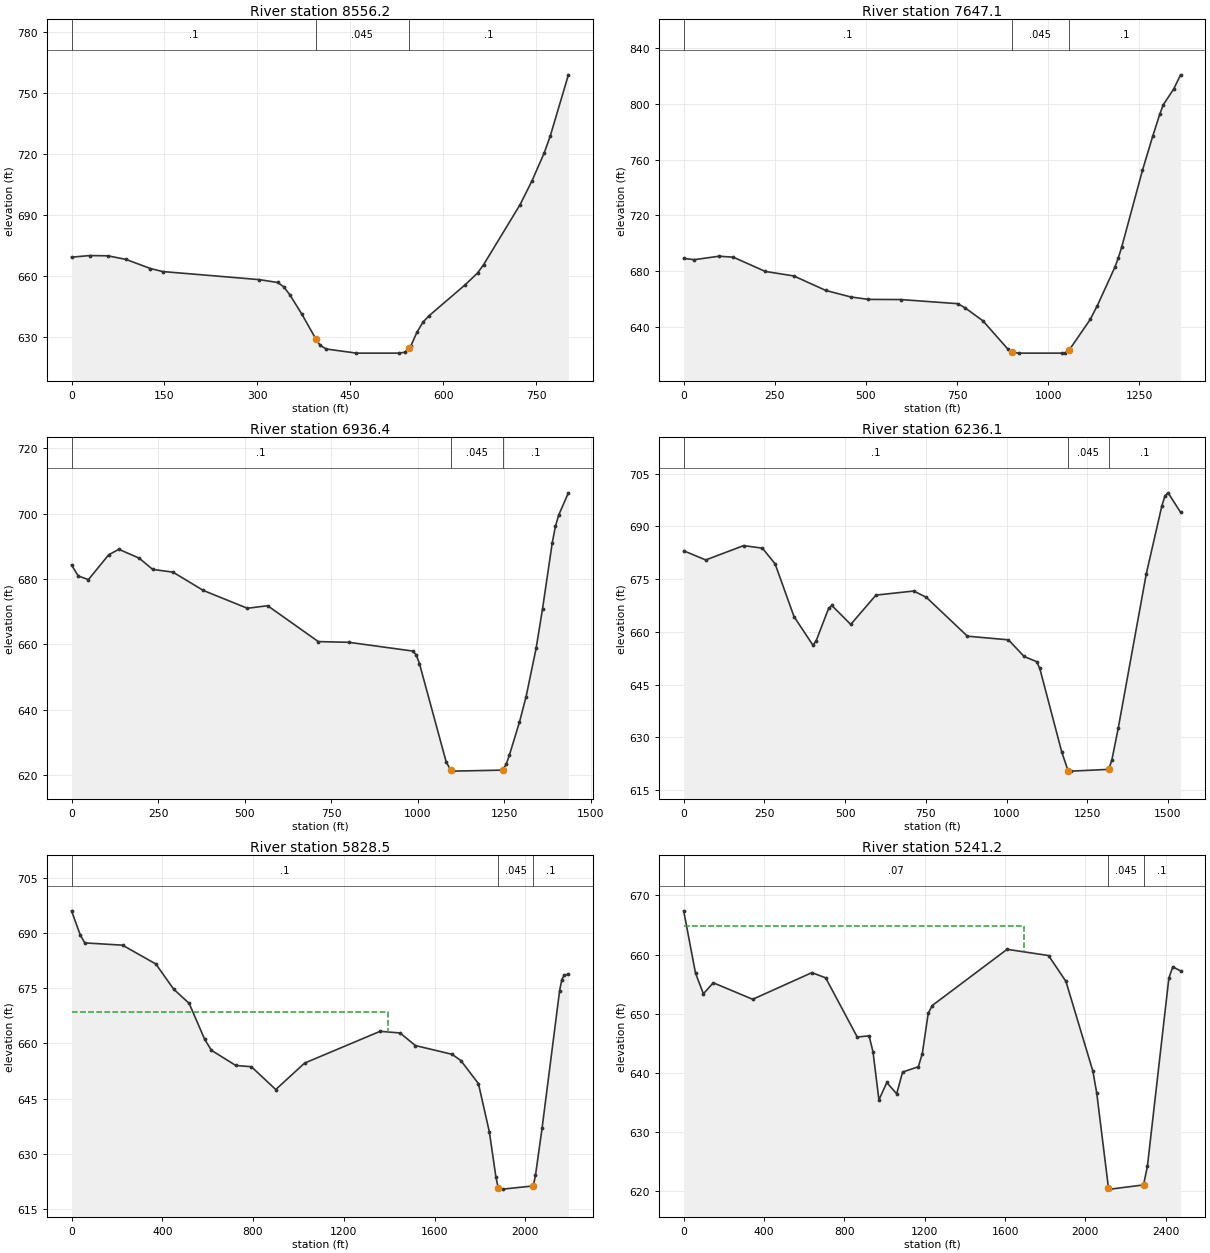
Type RM Length L Ch R = 1 ,8556.2  ,892.4,909.1,925.8
XS GIS Cut Line= 3
     1540025.416      348638.731     1539877.111        348562.9
     1539241.562      348547.585
#Sta/Elev= 30
       0  669.41    29.4   670.2    58.8  670.07    88.2  668.28   127.4  663.83
     147  662.34   303.5  658.35   332.8  656.95   342.6  654.86   352.4  650.96
     372  641.33   394.5629.1755   401.3  626.06   411.1  624.25     460   622.2
   528.4   622.2   538.2  622.64   544.5624.6971     548  625.84   557.8  632.49
   567.6   637.5   577.4  640.61     636  655.92   655.6  661.61   665.4  665.72
   724.1  695.15   743.6  707.02   763.2  720.66     773     729   802.3  759.11
#Mann= 3 , 0 , 0
       0      .1       0   394.5    .045       0   544.5      .1       0
Bank Sta=394.5,544.5
XS Rating Curve= 0 ,0
Exp/Cntr=0.3,0.1

Type RM Length L Ch R = 1 ,7647.1  ,704.8,710.7,716.6
XS GIS Cut Line= 4
     1540422.725      348546.717     1540270.207      348084.044
     1539793.645      347630.919     1539655.624      347461.648
#Sta/Elev= 30
       0  689.15    29.2  688.28    97.4  690.76   136.4  690.02   224.1  679.82
     302  676.62   389.7  666.23   457.9  661.58   506.8   659.8   595.1  659.69
   752.2  656.73   771.8   653.8   820.9  644.46   889.6  624.14   899.4  621.89
     919   621.3  1036.8   621.3  1046.6  621.48  1056.8623.2133  1115.3  645.42
    1135  655.42  1182.7  682.72  1192.2  689.33  1201.7   697.3  1258.7  752.35
  1287.2  777.08  1306.2  792.55  1315.7  799.25  1344.2   810.5  1363.2  820.72
#Mann= 3 , 0 , 0
       0      .1       0   899.4    .045       0  1056.8      .1       0
Bank Sta=899.4,1056.8
XS Rating Curve= 0 ,0
Exp/Cntr=0.3,0.1

Type RM Length L Ch R = 1 ,6936.4  ,696.5,700.3,704
XS GIS Cut Line= 5
     1541208.315      348138.731     1540878.561      347654.259
     1540548.853      347446.023     1540358.749      347133.523
     1540304.062      347058.002
#Sta/Elev= 30
       0  684.28    19.5  680.91    48.8   679.8   107.4  687.39   136.7  689.07
   195.4  686.37   234.4  682.92     293  682.08   380.9  676.47   507.9  671.03
   566.5  671.81   712.8  660.83   800.5  660.62   985.6  657.94   995.3  656.82
  1004.9  654.08  1081.9  624.07  1094.9621.5358  1101.1   621.2  1244.9621.5094
  1255.2  623.26  1264.8  626.18  1293.7   636.2  1312.9  644.03  1341.8  658.79
  1360.4  670.93  1388.4  691.08  1397.7  696.16  1407.1  699.58    1435  706.35
#Mann= 3 , 0 , 0
       0      .1       0  1094.9    .045       0  1244.9      .1       0
Bank Sta=1094.9,1244.9
XS Rating Curve= 0 ,0
Exp/Cntr=0.3,0.1

Type RM Length L Ch R = 1 ,6236.1  ,407.5,407.6,407.6
XS GIS Cut Line= 5
     1541547.262      348106.582     1541137.527      347488.091
     1541173.853      347216.856     1541033.228      346865.294
     1540960.312      346740.294
#Sta/Elev= 30
       0  683.05    68.3  680.44   185.5  684.52     244  683.79   283.1  679.34
   341.7  664.34   400.2  656.22     410  657.39     449   666.7   458.8   667.5
   517.4  662.12   595.5  670.45   712.6  671.61   751.7  669.81   878.7  658.77
  1005.8  657.73  1054.4     653  1093.2  651.53  1102.9   649.6  1170.9  625.85
  1190.3  620.55    1200   620.4  1316.5   620.9  1326.2   623.6  1345.7  632.55
  1432.8  676.55    1481  695.84  1490.7  698.68  1500.3  699.53  1538.9     694
#Mann= 3 , 0 , 0
       0      .1       0  1190.3    .045       0  1316.5      .1       0
Bank Sta=1190.3,1316.5
XS Rating Curve= 0 ,0
Exp/Cntr=0.3,0.1

Type RM Length L Ch R = 1 ,5828.5  ,591.6,587.3,583.1
XS GIS Cut Line= 4
     1542452.022      348397.383      1541775.81      347105.909
     1541543.645       347050.19     1541361.353      346591.856
#Sta/Elev= 30
       0     696    39.1  689.37    58.7  687.29     225  686.67   371.8  681.55
   450.1  674.73   518.5  670.85     587  661.08   616.4  658.12     724  653.99
   792.5  653.66   900.1  647.46  1027.3  654.64    1360  663.27    1448  662.82
  1515.1  659.41  1677.4  657.02  1715.9  655.32  1793.3  649.07  1841.6  635.91
  1870.6  623.58  1880.3  620.83  1899.7   620.4  2035.1  621.27  2044.7  624.13
  2073.8  636.97  2151.1  674.31  2160.8   677.3  2170.5  678.46  2189.8  678.81
#Mann= 3 , 0 , 0
       0      .1       0  1880.3    .045       0  2035.1      .1       0
#XS Ineff= 2 , 0
         1394.23  668.62
Permanent Ineff=
       F       F
Bank Sta=1880.3,2035.1
XS Rating Curve= 0 ,0
Exp/Cntr=0.3,0.1

Type RM Length L Ch R = 1 ,5241.2  ,508.4,505.1,501.8
XS GIS Cut Line= 4
     1542939.189      348503.284     1542068.123      346875.987
     1542077.499      346714.252     1541827.499      346321.023
#Sta/Elev= 30
       0   667.4    58.9  656.87    98.2  653.39   147.3  655.25   343.6  652.46
   638.2  656.96   706.9  656.08     864  646.09   922.9  646.29   942.5  643.59
     972  635.47  1011.2  638.41  1060.3   636.5  1089.8  640.17  1168.3  641.07
    1188   643.3  1217.4  650.08  1237.1   651.4  1610.1   660.9  1816.3  659.85
  1902.9  655.49  2036.9  640.35  2056.3  636.64  2114.6  620.62  2124.3   620.4
  2289.3  621.11  2308.7  624.29  2415.5  656.06  2434.9  657.94  2473.7  657.26
#Mann= 3 , 0 , 0
       0     .07       0  2114.6    .045       0  2289.3      .1       0
#XS Ineff= 2 , 0
         1691.85  664.82
Permanent Ineff=
       F       F
Bank Sta=2114.6,2289.3
XS Rating Curve= 0 ,0
Exp/Cntr=0.3,0.1

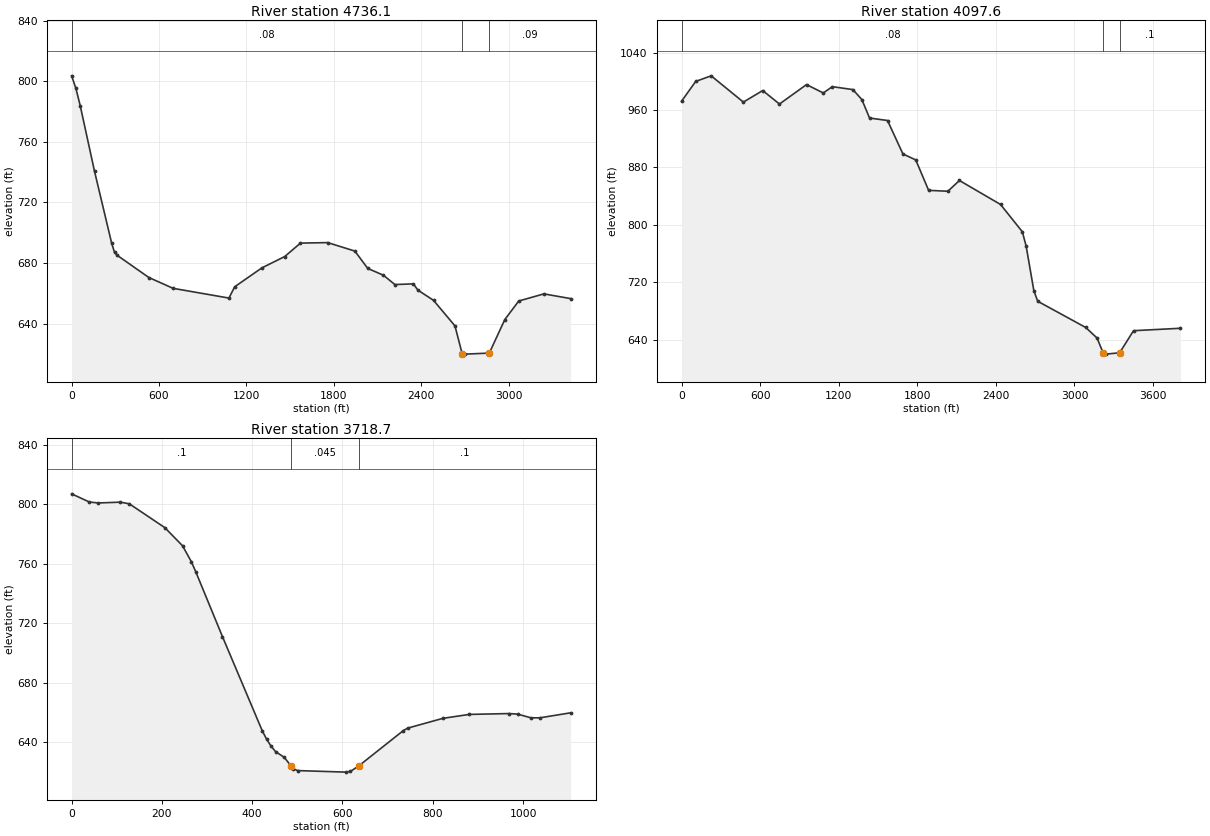
Type RM Length L Ch R = 1 ,4736.1  ,687.9,638.5,589
XS GIS Cut Line= 4
     1544182.244      348336.617     1542275.416      346130.919
     1542017.667      346111.826     1541869.166       346313.21
#Sta/Elev= 30
       0  803.59    29.4  795.33    58.9  783.93   157.1  740.63   274.9  693.06
   294.5  687.08   314.2  685.03   530.1  670.47     697  663.31  1079.9   656.9
  1119.1  664.35  1305.7  676.82  1462.7  684.32  1570.7  693.18  1757.2  693.51
  1943.8  687.93  2032.1  676.49  2140.1  671.97  2218.6  665.82  2346.3  666.28
  2375.7  662.18  2483.7  655.42    2631  638.54  2680.1  620.23  2699.7   619.9
  2866.6  620.59  2973.1  642.72  3068.8  654.98  3241.5  659.66  3424.3  656.56
#Mann= 3 , 0 , 0
       0     .08       0  2680.1    .045       0  2866.6     .09       0
Bank Sta=2680.1,2866.6
XS Rating Curve= 0 ,0
Exp/Cntr=0.3,0.1

Type RM Length L Ch R = 1 ,4097.6  ,381.7,378.9,376.2
XS GIS Cut Line= 6
     1544821.133      346781.061     1544057.244       345919.95
     1542862.697      345646.885     1542154.032      345659.977
     1542064.449      346003.553     1541853.541      346305.398
#Sta/Elev= 30
       0  972.28   108.2  999.97   226.3 1007.75   472.2  971.15   619.8  987.24
   747.7  968.45   954.3  995.54  1082.2  983.86  1151.1  992.64    1308  988.59
  1376.6  974.73  1435.4  948.94  1572.6  945.49  1690.3  898.85  1788.3  890.53
  1886.3  848.16  2033.4  846.88  2121.6  861.88  2435.2  828.49  2601.6   790.5
  2630.9  770.47  2689.6  708.47    2719  693.59  3085.7  657.04  3172.1  642.36
    3220  621.09  3239.2   619.9  3344.8   621.8  3450.5  652.55    3809  655.95
#Mann= 3 , 0 , 0
       0     .08       0    3220    .045       0  3344.8      .1       0
Bank Sta=3220,3344.8
XS Rating Curve= 0 ,0
Exp/Cntr=0.3,0.1

Type RM Length L Ch R = 1 ,3718.7  ,328.2,323.2,318.3
XS GIS Cut Line= 4
     1541918.356      345267.172     1541750.676      345633.523
     1541695.989      346039.773     1541675.155       346331.44
#Sta/Elev= 30
       0  807.11    39.3  801.59      59  800.95   108.1   801.5   127.8   800.4
   206.4  784.36   245.7  772.15   265.3  761.36   275.2  754.48   334.1  710.99
   422.4  647.48   432.2  641.76   441.9  637.21   451.7  633.58   471.2  629.64
     486623.8864   490.7  622.05   500.5  620.78   607.9  619.74   617.6  620.21
     636623.9158   734.7   647.7   744.5  649.37   822.6  655.97     881   658.6
   968.8  659.17   988.3  658.77  1017.5   656.3    1037   656.3  1105.2  659.67
#Mann= 3 , 0 , 0
       0      .1       0     486    .045       0     636      .1       0
Bank Sta=486,636
XS Rating Curve= 0 ,0
Exp/Cntr=0.3,0.1