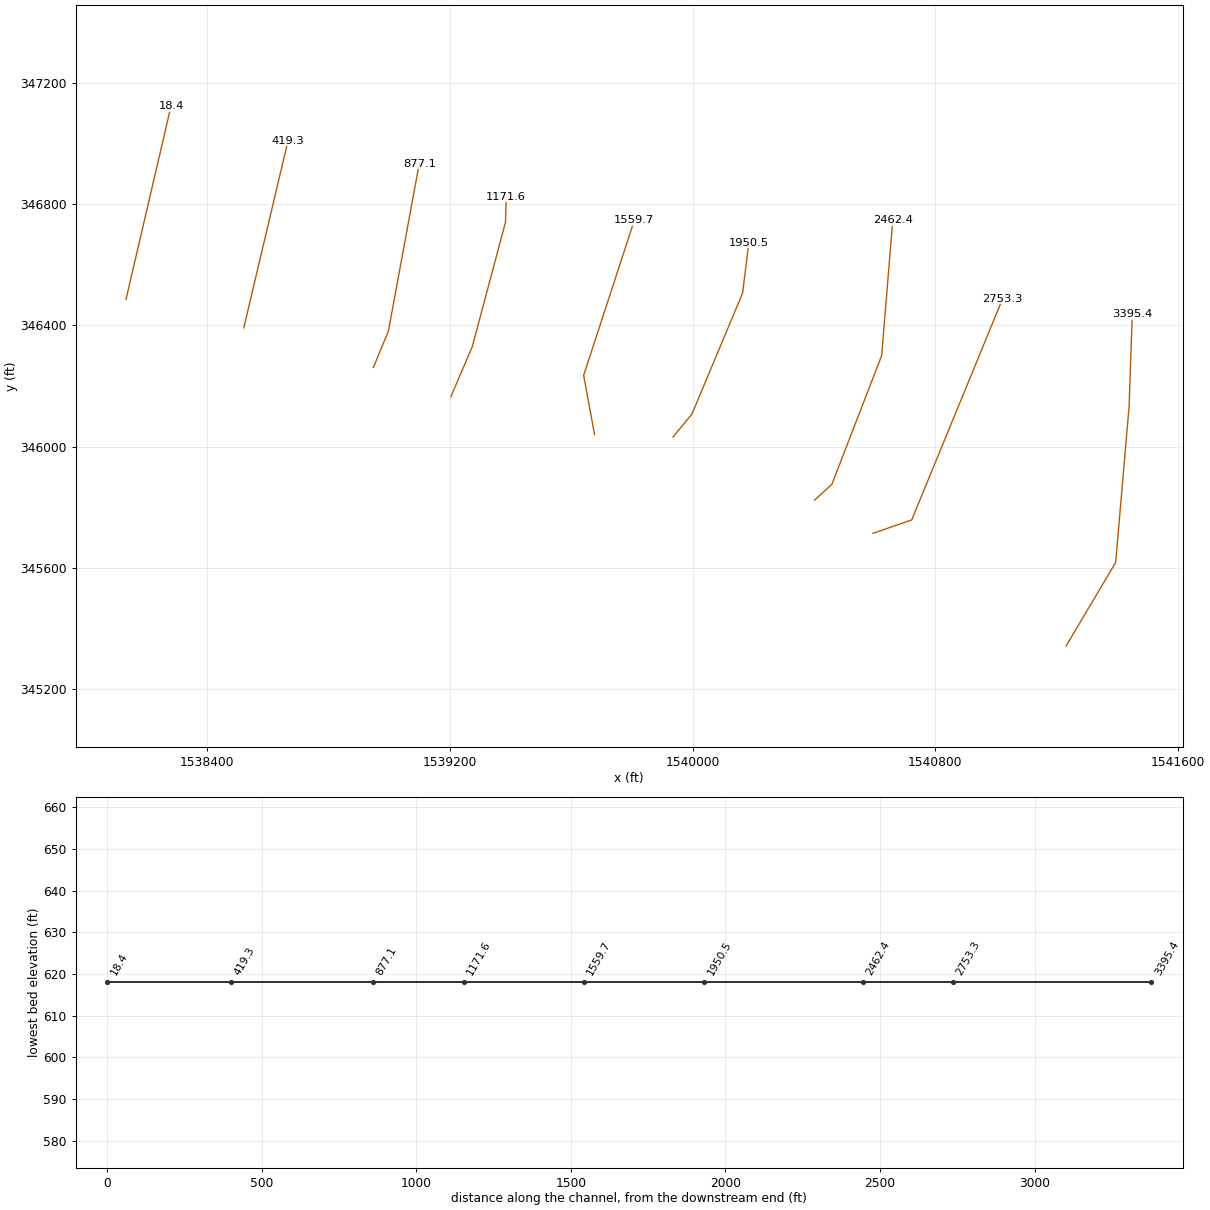
HEC-RAS study MDISLCRK1.prj: MDISLCRK1

--- MDISLCRK1.g01 (geometry) --- (continued)

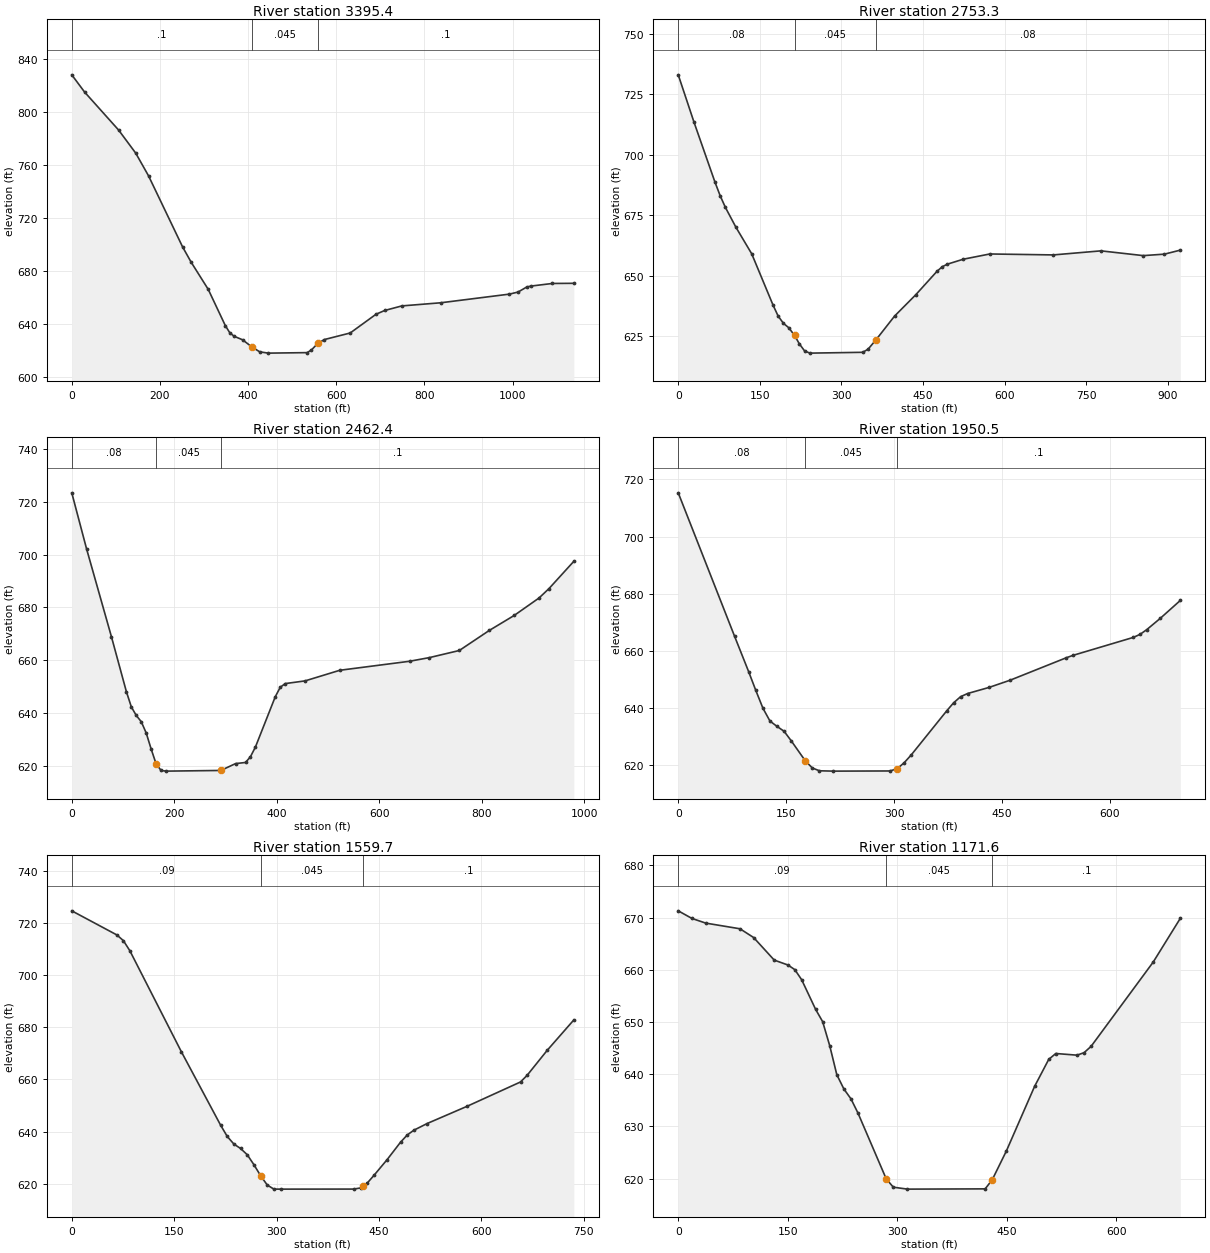
Type RM Length L Ch R = 1 ,3395.4  ,648.8,642.1,635.1
XS GIS Cut Line= 4
     1541230.856      345343.561     1541393.905      345617.898
     1541438.176      346133.523     1541448.593      346435.606
#Sta/Elev= 30
       0  828.22      29  815.24   106.4  786.45   145.1  769.06   174.1  751.94
   251.4  698.22   270.8  686.69   309.5   666.2   348.4  638.74   358.2  633.52
     368  630.76   387.5  628.07   407.8622.8549   426.5  618.95   446.1     618
     534  618.38   543.7  620.39   557.8625.2955     573  628.26   631.6  633.21
   690.2  647.38   709.7   650.2   748.8  653.67   836.6  656.02   992.7  662.57
  1012.2  664.12  1031.7  667.88  1041.4  668.64  1090.2  670.62  1138.9  670.74
#Mann= 3 , 0 , 0
       0      .1       0   407.8    .045       0   557.8      .1       0
Bank Sta=407.8,557.8
XS Rating Curve= 0 ,0
Exp/Cntr=0.3,0.1

Type RM Length L Ch R = 1 ,2753.3  ,290.4,290.9,291.4
XS GIS Cut Line= 3
     1540594.426      345714.252      1540722.03      345758.523
     1541021.509       346487.69
#Sta/Elev= 30
       0  733.05    28.9  713.54    67.5  688.73    77.2  683.01    86.8  678.21
   106.1  670.03   135.1  659.07     174  638.04   183.7  633.32   193.5  630.31
   203.2  628.51     214625.2934   222.6  621.88   232.4   618.9   242.1     618
   339.4  618.34   349.2  619.65     364623.6016   397.8   633.3   436.8  642.13
   475.7  651.79   485.4   653.7   495.1  654.79   524.3  656.83     573  658.99
   689.8   658.6   777.4  660.28   855.2  658.31   894.1  658.92   923.3  660.58
#Mann= 3 , 0 , 0
       0     .08       0     214    .045       0     364     .08       0
Bank Sta=214,364
XS Rating Curve= 0 ,0
Exp/Cntr=0.3,0.1

Type RM Length L Ch R = 1 ,2462.4  ,512.5,511.9,511.3
XS GIS Cut Line= 4
     1540401.718      345823.627     1540459.009       345875.71
     1540623.072       346300.19      1540659.53      346745.502
#Sta/Elev= 30
       0  723.36      29  702.05    77.4  668.86   106.5  648.11   116.2   642.3
   125.8  639.08   135.5  636.73   145.2  632.43   154.9  626.33   164.6   620.7
   174.2  618.26   183.9     618   290.7618.2529   319.5  620.85   338.9  621.28
   348.5  623.44   358.2  627.12     397   646.2   406.6  649.73   416.3  651.14
     455  652.16   522.8  656.18   658.8  659.59   697.6  660.98   755.9  663.67
   814.2  671.24   862.8  676.92   911.3  683.53   930.8   687.1   979.3  697.44
#Mann= 3 , 0 , 0
       0     .08       0   164.6    .045       0   290.7      .1       0
Bank Sta=164.6,290.7
XS Rating Curve= 0 ,0
Exp/Cntr=0.3,0.1

Type RM Length L Ch R = 1 ,1950.5  ,389,390.8,392.6
XS GIS Cut Line= 4
     1539935.572       346031.96     1539998.072      346107.481
     1540164.739      346505.919     1540185.572      346672.585
#Sta/Elev= 30
       0  715.31    78.4   665.1      98   652.7   107.8  646.24   117.7  640.01
   127.5  635.51   137.3  633.64   147.1  631.94   156.9  628.66   176.6  621.61
   186.4   619.1   196.2  618.12   215.8     618   294.3  618.06   304.2  618.81
     314  620.92   323.8  623.64   372.9  638.99   382.7  641.87   392.5  644.03
   402.3  645.14   431.8  647.25   461.2  649.78   539.2  657.62   548.6  658.47
   632.6  664.76   641.9  665.82   651.2  667.46   669.9  671.39   697.9  677.68
#Mann= 3 , 0 , 0
       0     .08       0   176.6    .045       0   304.2      .1       0
Bank Sta=176.6,304.2
XS Rating Curve= 0 ,0
Exp/Cntr=0.3,0.1

Type RM Length L Ch R = 1 ,1559.7  ,386.8,388.1,389.3
XS GIS Cut Line= 3
      1539677.13      346039.918     1539641.301      346235.085
     1539807.968      346745.502
#Sta/Elev= 30
       0  724.57    66.1  715.33    75.6  713.15      85  709.32   160.6  670.57
     218   642.5   227.7  638.18   237.5  635.25   247.2  633.57     257  631.18
   266.8  627.35     277622.9773   286.3  619.58     296  618.01   305.8     618
   413.2  618.02     423  618.46     427619.2147   432.7  620.29   442.5  623.23
     462  629.33   481.5  635.95   491.3  638.72   501.1  640.57   520.6  643.13
   579.2  649.74   657.3  659.04     667  661.59   696.3  671.13   735.4   682.8
#Mann= 3 , 0 , 0
       0     .09       0     277    .045       0     427      .1       0
Bank Sta=277,427
XS Rating Curve= 0 ,0
Exp/Cntr=0.3,0.1

Type RM Length L Ch R = 1 ,1171.6  ,292.7,294.5,296.2
XS GIS Cut Line= 4
     1539203.801      346164.773     1539274.114      346328.835
     1539383.813      346740.207     1539386.093      346823.627
#Sta/Elev= 30
       0  671.31    18.8  669.85    37.6  668.96    84.6  667.87   103.3  666.19
   131.5  661.87   150.3  660.93   159.7  660.04   169.1   658.1   188.2  652.43
   197.8  650.08   207.5  645.47   217.2  639.92   226.9  637.18   236.6  635.29
   246.2  632.57   284.9  619.96   294.6  618.37     314     618   420.4  618.05
   430.1   619.8   449.4  625.29   488.1  637.68   507.5  642.86   517.2  643.98
   546.2  643.66   555.9  644.14   565.5  645.35   650.6   661.5   687.7  669.87
#Mann= 3 , 0 , 0
       0     .09       0   284.9    .045       0   430.1      .1       0
Bank Sta=284.9,430.1
XS Rating Curve= 0 ,0
Exp/Cntr=0.3,0.1

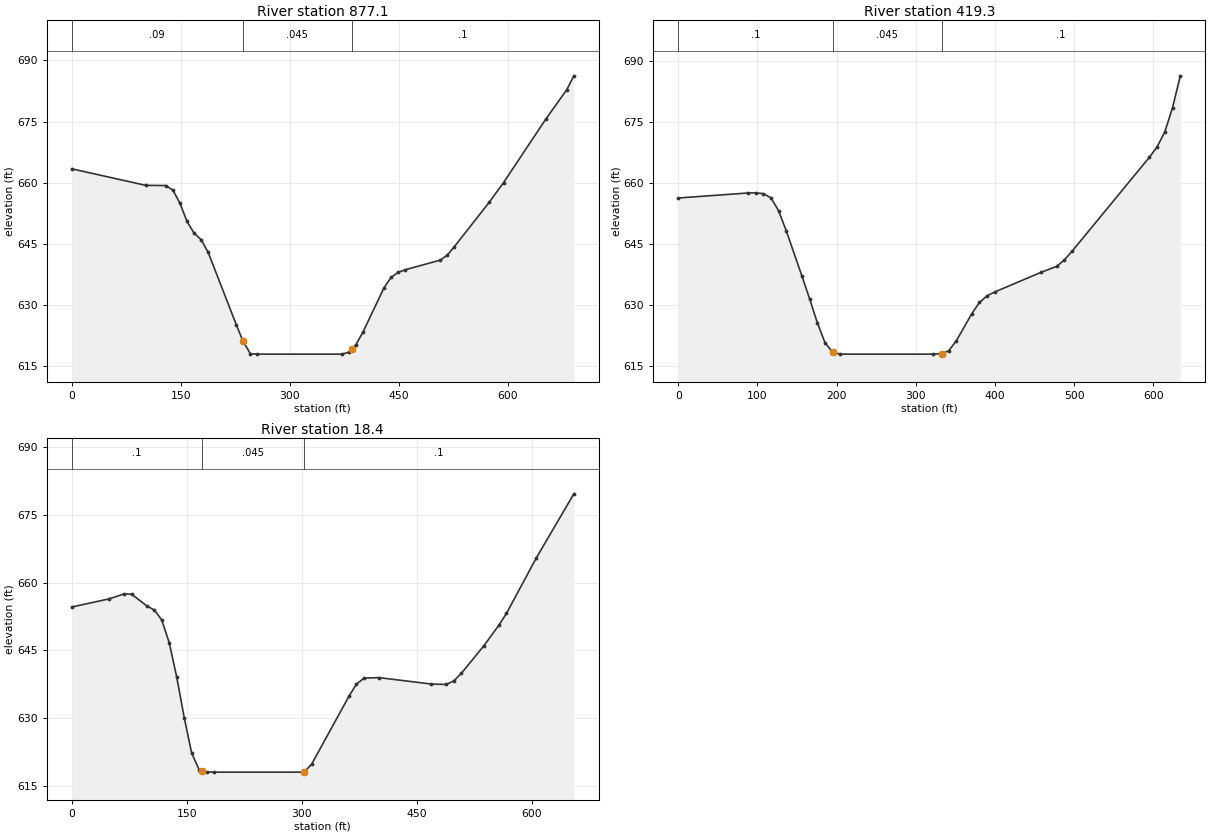
Type RM Length L Ch R = 1 ,877.1   ,459,457.8,456.7
XS GIS Cut Line= 3
     1538948.593      346261.127     1538998.072      346380.919
     1539099.634      346933.002
#Sta/Elev= 30
       0  663.41   101.8  659.36   129.6  659.31   139.3  658.17     149  654.93
   158.6  650.51   168.3  647.66     178  646.06   187.7  642.95   226.4  625.22
   235.3621.3113   245.8   618.1   255.4     618   371.6     618   381.2  618.44
   385.3 619.205   390.9  620.25   400.6  623.34   429.6  634.21   439.3  636.78
     449  638.02   458.7  638.67   507.1  641.03   516.7  642.25   526.4   644.3
   574.8  655.28   594.2  660.02   652.2  675.54   681.3  682.81     691   686.2
#Mann= 3 , 0 , 0
       0     .09       0   235.3    .045       0   385.3      .1       0
Bank Sta=235.3,385.3
XS Rating Curve= 0 ,0
Exp/Cntr=0.3,0.1

Type RM Length L Ch R = 1 ,419.3   ,400.7,400.8,400.9
XS GIS Cut Line= 2
     1538521.509      346391.335     1538667.343      347008.523
#Sta/Elev= 30
       0  656.31    87.8  657.54    97.6  657.57   107.3  657.39   117.1  656.36
   126.8  653.18   136.6  648.18   156.1  637.24   165.9   631.6   175.6  625.75
   185.4  620.81   195.1  618.44   204.9     618     322     618   332.7618.1355
   341.5   618.8   351.2  621.24   370.8  627.92   380.5  630.68   390.3  632.34
     400  633.27   458.6   638.1   478.1  639.54   487.8  641.13   497.6  643.28
   595.2  666.32   604.9  668.86   614.7  672.56   624.4  678.48   634.2  686.29
#Mann= 3 , 0 , 0
       0      .1       0   195.1    .045       0   332.7      .1       0
Bank Sta=195.1,332.7
XS Rating Curve= 0 ,0
Exp/Cntr=0.3,0.1

Type RM Length L Ch R = 1 ,18.4    ,21,18.4,15.9
XS GIS Cut Line= 2
     1538133.489      346485.085     1538281.926      347123.106
#Sta/Elev= 30
       0  654.62    48.9  656.43    68.4  657.53    78.2  657.45    97.8  654.88
   107.6  653.96   117.3  651.78   127.1  646.74   136.9  639.11   146.7  630.11
   156.4  622.25   166.2  618.53   170.4618.3072     176  618.01   185.8     618
   303.1     618   312.9  619.74   361.8  634.87   371.5  637.52   381.3  638.84
   400.9  638.96   469.3  637.53   488.8  637.45   498.6  638.25   508.4  639.93
   537.7  646.02   557.3  650.59   567.1  653.18   606.2  665.52   655.1  679.72
#Mann= 3 , 0 , 0
       0      .1       0   170.4    .045       0   303.1      .1       0
Bank Sta=170.4,303.1
XS Rating Curve= 0 ,0
Exp/Cntr=0.3,0.1

Chan Stop Cuts=-1
Use User Specified Reach Order=0
Composite Channel Slope=5

--- MDISLCRK1.g02 (geometry) ---

Geom Title=USGS 10m DEM_old
Program Version=4.10

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
River Reach=MDISLCRK1       ,Main

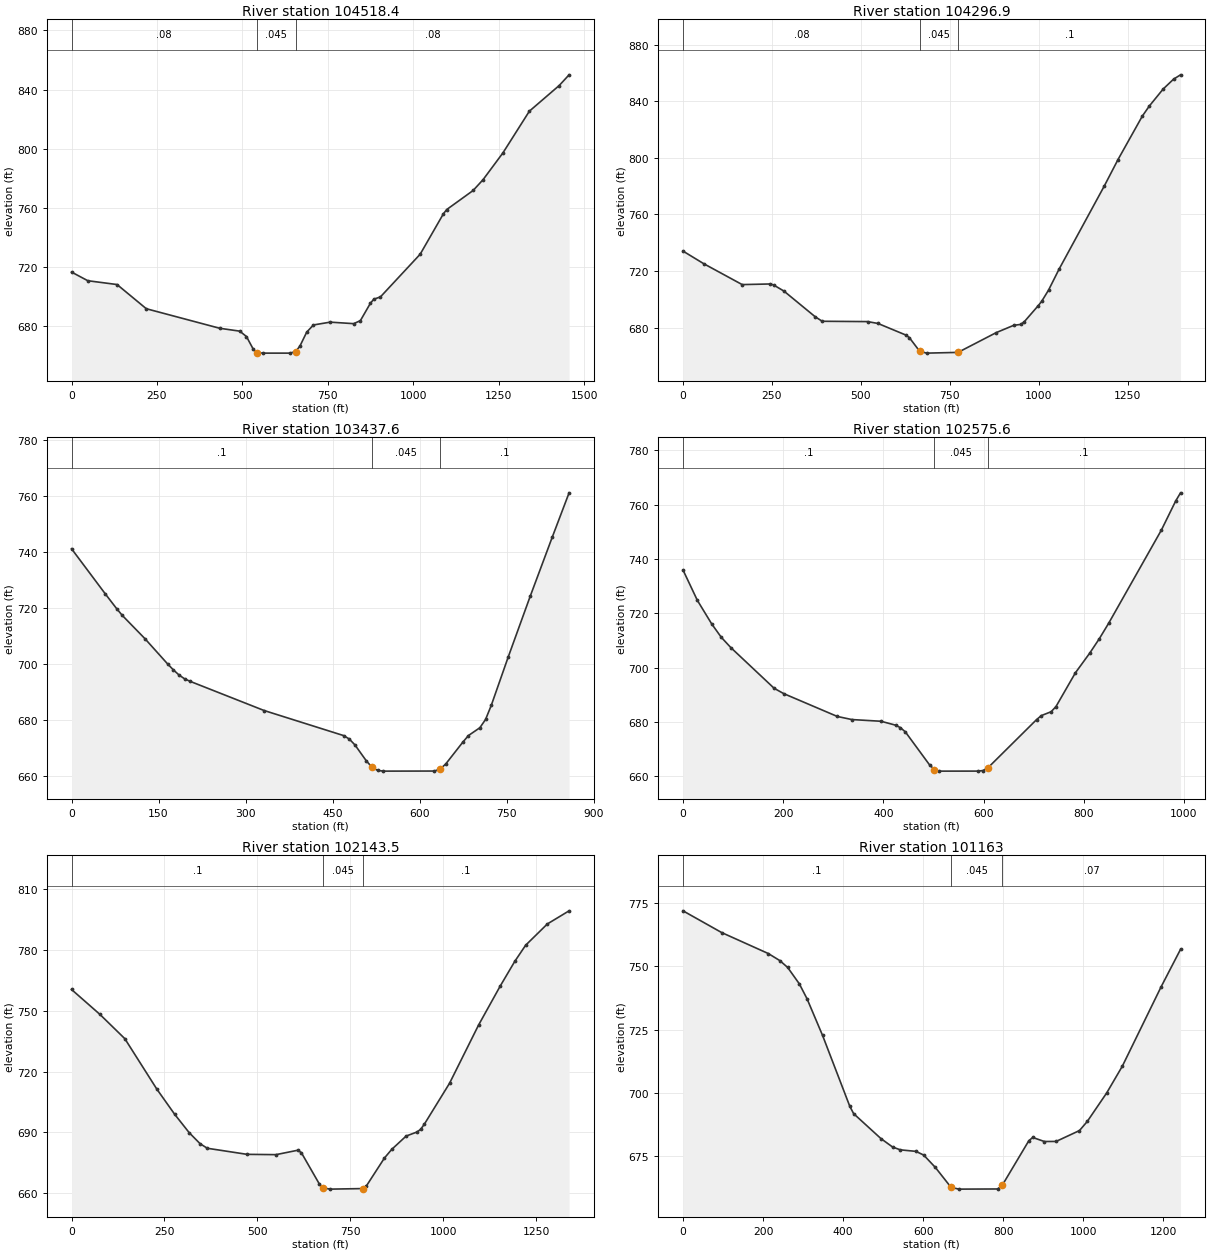
Type RM Length L Ch R = 1 ,104518.4,220.8,221.5,222.2
XS GIS Cut Line= 4
     1567886.737      365239.296     1567648.857      365336.229
      1567057.68       365599.18     1566925.799      366135.129
#Sta/Elev= 30
       0  716.68    47.6  710.83   133.2  708.25   218.8   691.9   433.3  678.71
   492.2  676.75   511.8  673.11   531.4   664.7   541.2  662.16   560.8   661.9
   639.2   661.9   656.1  662.96   668.6  666.84   688.2  676.12   707.8  680.94
   756.8  682.84   825.5  681.82   845.1  683.84   874.5  695.62   884.3  698.32
   903.9  699.91  1020.1  728.75  1087.9     756  1097.6   758.9    1175  771.81
  1204.1  779.12  1262.2  797.21  1339.6  825.41  1426.8  842.73  1455.8  849.97
#Mann= 3 , 0 , 0
       0     .08       0   541.2    .045       0   656.1     .08       0
Bank Sta=541.2,656.1
XS Rating Curve= 0 ,0
Exp/Cntr=0.3,0.1

Type RM Length L Ch R = 1 ,104296.9,857.2,859.2,861
XS GIS Cut Line= 3
      1567942.95      364989.536     1567009.132      365369.504
     1566618.507      365374.712
#Sta/Elev= 30
       0  734.04    58.7  725.07   166.4  710.35   244.7  710.79   254.5  710.11
   283.8  705.77   371.9  687.56   391.5  684.42   518.8  684.19   548.1  682.88
   626.4   674.7   636.2  672.91   665.6  663.16   685.2   661.9   773.2  662.42
   880.9  676.43   929.9  681.57   949.4  682.19   959.2  684.01   998.4  695.35
  1008.2  698.44  1027.7  706.44    1057  721.12    1184  779.85    1223  798.75
  1291.4  829.48  1310.9  836.55    1350  848.63  1379.3  855.61  1398.8  858.65
#Mann= 3 , 0 , 0
       0     .08       0   665.6    .045       0   773.2      .1       0
Bank Sta=665.6,773.2
XS Rating Curve= 0 ,0
Exp/Cntr=0.3,0.1

Type RM Length L Ch R = 1 ,103437.6,861.2,862.1,862.7
XS GIS Cut Line= 4
     1567537.778       364273.15     1567386.737      364340.858
     1566834.653      364510.129     1566727.882      364551.796
#Sta/Elev= 30
       0  741.14    58.4     725    77.9  719.76    87.6  717.36   126.6  709.08
   165.5  700.12   175.3  698.03   185.1  696.18   194.9  694.79   204.7  693.87
   331.9   683.5   468.9  674.57   478.7  673.35   488.5  671.24   508.1  665.56
   517.9  663.29   527.6  662.16   537.4   661.9   625.5  661.93   635.3  662.62
   645.1  664.48   674.5  672.24   684.2  674.59   703.8  677.36   713.6   680.3
   723.4  685.29   752.5  702.46   790.7  724.27   828.9  745.44   857.6  761.07
#Mann= 3 , 0 , 0
       0      .1       0   517.9    .045       0   635.3      .1       0
Bank Sta=517.9,635.3
XS Rating Curve= 0 ,0
Exp/Cntr=0.3,0.1

Type RM Length L Ch R = 1 ,102575.6,433.3,432,430.4
XS GIS Cut Line= 4
     1567340.296      363550.059     1567201.407      363515.337
     1566583.351      363682.004     1566482.657      363866.032
#Sta/Elev= 30
       0  735.97    28.6   724.8    57.3   716.1    76.4  711.18    95.4   707.4
     182  692.39   201.4  690.41     308  682.03   337.1  680.89   395.3  680.26
   424.4  678.82   434.1  677.88   443.8  676.36   492.3  664.16     502  662.46
   511.7   661.9   589.3  661.91     599  662.12   608.7  663.13   705.7  680.86
   715.4  682.36   734.8  683.77   744.5  685.68   783.3  698.12   811.9  705.36
     831  710.66     850  716.46   954.9  750.67   983.5   761.4   993.1  764.37
#Mann= 3 , 0 , 0
       0      .1       0     502    .045       0   608.7      .1       0
Bank Sta=502,608.7
XS Rating Curve= 0 ,0
Exp/Cntr=0.3,0.1

Type RM Length L Ch R = 1 ,102143.5,983.1,980.5,977.7
XS GIS Cut Line= 4
      1567378.49      363119.504     1567138.907      363053.532
     1566392.379      363307.004     1566170.157      363511.865
#Sta/Elev= 30
       0  760.57    76.5  748.24   143.4  736.26   229.4  711.37   277.7  698.85
   316.6  689.81   345.8  684.38   365.3   682.1   472.4  679.09   550.2  678.94
   608.6  681.11   618.4  679.96     667  664.42   676.8  662.51   696.2   661.9
   783.8  662.17   793.6  663.49   842.2  677.29   861.7  681.53   900.6  688.14
   929.8  690.13   939.6  691.48   949.3  693.93  1017.4  714.23  1095.4  742.97
  1153.9  762.32  1192.9  774.46  1222.1  782.43  1280.6  792.96  1339.1  799.45
#Mann= 3 , 0 , 0
       0      .1       0   676.8    .045       0   783.8      .1       0
Bank Sta=676.8,783.8
XS Rating Curve= 0 ,0
Exp/Cntr=0.3,0.1

Type RM Length L Ch R = 1 ,101163  ,437.5,438.3,439.3
XS GIS Cut Line= 4
     1567074.895      361951.341     1566725.712      362119.504
      1566128.49      362404.226     1565951.407      362484.087
#Sta/Elev= 30
       0  772.01    96.9  763.39   213.2  755.11   242.2   752.3   261.6   749.6
   290.7  743.13     310  737.21   348.8  722.71   416.8  694.69   426.5  691.75
   494.6  681.91   523.8  678.56   543.2  677.44   582.2  676.84   601.6  675.37
   630.8  670.46   669.7  662.64   689.2   661.9   786.5  661.96   797.7  663.38
   864.3  681.06     874  682.34   903.2  680.74   932.4  680.77   990.8  685.07
  1010.3  688.67  1058.9  699.97  1097.8   710.5  1194.9  741.96  1243.4  756.78
#Mann= 3 , 0 , 0
       0      .1       0   669.7    .045       0   797.7     .07       0
Bank Sta=669.7,797.7
XS Rating Curve= 0 ,0
Exp/Cntr=0.3,0.1

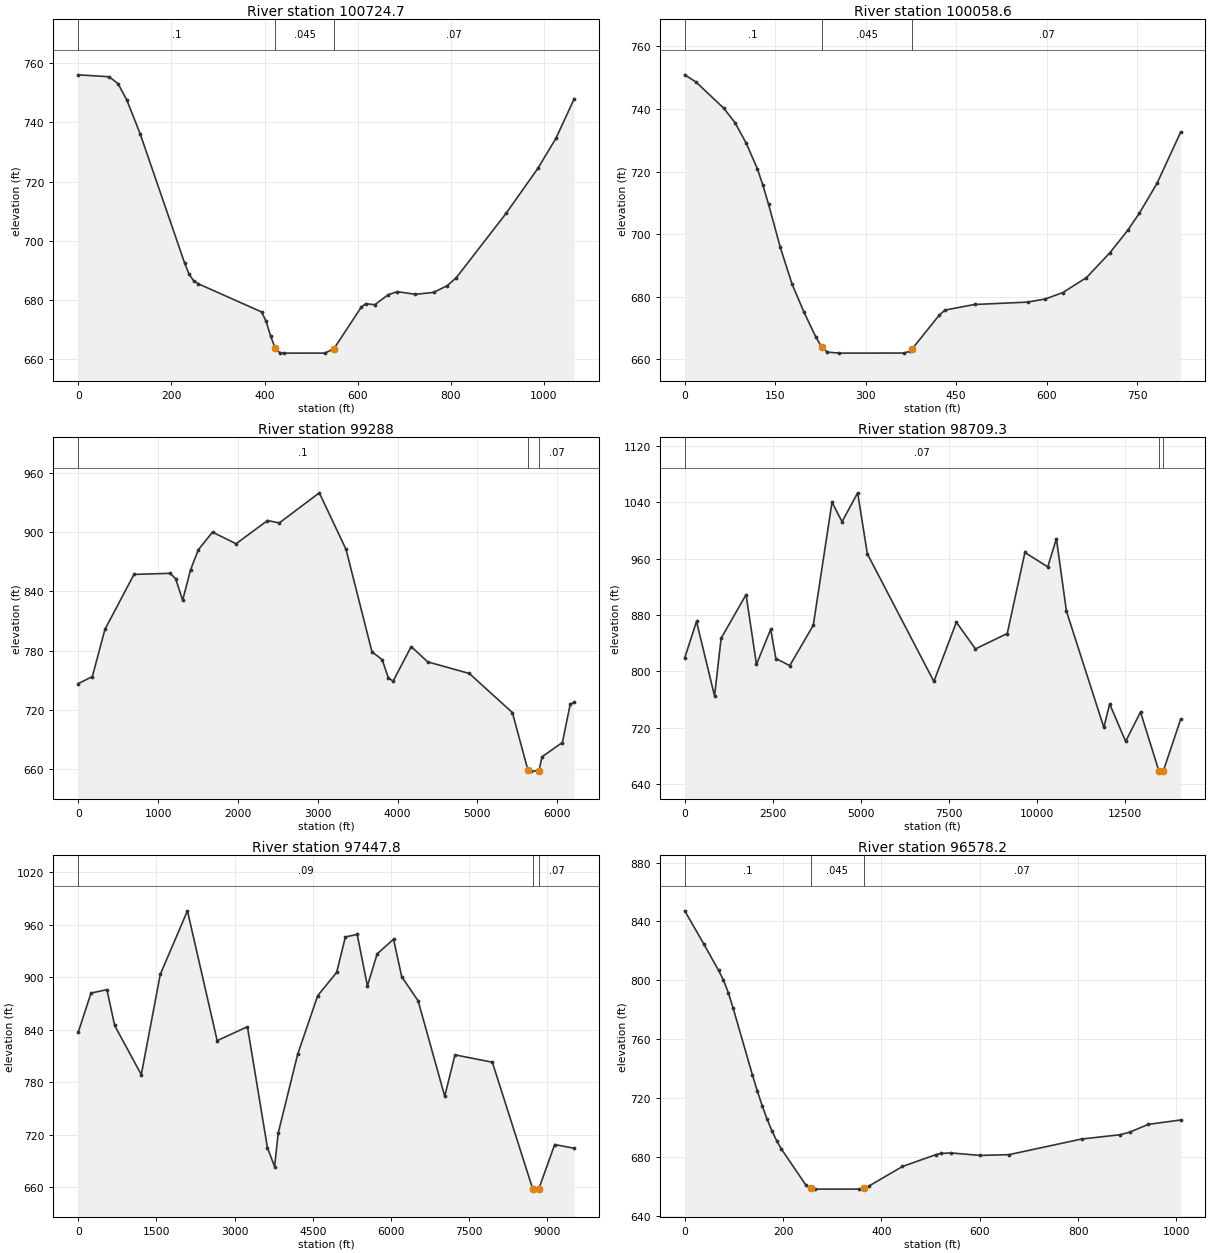
Type RM Length L Ch R = 1 ,100724.7,667,666,664.9
XS GIS Cut Line= 4
     1566677.101      361588.254      1566534.74      361741.032
     1565927.101      362001.448     1565802.101      362150.754
#Sta/Elev= 30
       0  756.14    66.4  755.49    85.4  753.17   104.4   747.6   132.9   736.2
   228.3  692.48     238  688.64   247.7  686.46   257.4  685.41   393.5  675.86
   403.3  672.73     413   667.7   422.7  663.64   432.4  662.08   442.2   661.9
   529.6  661.91   549.1  663.42   607.4  677.39   617.2  678.67   636.6  678.28
   665.8   681.7   685.2  682.71   724.1  681.82     763  682.46   792.1  684.74
   811.6  687.42   918.6  709.23   986.8  724.45  1025.7  734.67  1064.6  747.95
#Mann= 3 , 0 , 0
       0      .1       0   422.7    .045       0   549.1     .07       0
Bank Sta=422.7,549.1
XS Rating Curve= 0 ,0
Exp/Cntr=0.3,0.1

Type RM Length L Ch R = 1 ,100058.6,767.5,770.7,773.8
XS GIS Cut Line= 3
     1566348.976      361128.184     1566211.823      361150.754
      1565597.24      361449.365
#Sta/Elev= 30
       0  750.93    18.5  748.66    64.9  740.22    83.4   735.6   101.9  729.08
   120.5  720.87   129.7  715.55     139   709.5   158.5  695.71     178  683.97
   197.6  675.06   217.1  667.19   227.1   663.8   236.6  662.24   256.1   661.9
   363.5  661.93   373.3  662.47   377.1  663.24   422.1  674.08   431.8  675.68
   480.6  677.46   568.5  678.22   597.8  679.22   627.1  681.28   666.1  686.05
   705.2  694.05   734.4  701.14     754   706.7   783.2  716.22   822.3  732.57
#Mann= 3 , 0 , 0
       0      .1       0   227.1    .045       0   377.1     .07       0
Bank Sta=227.1,377.1
XS Rating Curve= 0 ,0
Exp/Cntr=0.3,0.1

Type RM Length L Ch R = 1 ,99288   ,580,578.7,577.4
XS GIS Cut Line= 3
     1571112.851      358747.359      1566323.96      360342.346
      1565215.99      360701.796
#Sta/Elev= 30
       0  746.58   177.1  753.71   334.5  801.44   698.6  857.15  1151.2  858.26
  1220.1   852.9  1308.6  830.96    1407  861.77  1505.4  882.18  1682.5  899.96
  1977.7  888.19  2371.2  911.69  2518.8  909.24  3020.6  939.74  3355.2  882.47
  3679.9  778.86  3807.8  770.81  3886.5  752.17  3945.5  749.18  4171.8   784.1
  4378.4  768.62  4899.9  756.84  5439.1   717.3  5632.4  659.51    5674     658
  5771.9  658.37    5811  672.54  6065.5  686.98  6163.4  725.56  6212.3  727.84
#Mann= 3 , 0 , 0
       0      .1       0  5632.4    .045       0  5771.9     .07       0
Bank Sta=5632.4,5771.9
XS Rating Curve= 0 ,0
Exp/Cntr=0.3,0.1

Type RM Length L Ch R = 1 ,98709.3 ,1271.4,1261.4,1251.1
XS GIS Cut Line= 6
     1570460.941      350776.872     1571445.488      357781.582
     1568745.007      359010.831     1565982.989      359954.863
     1565688.212      359930.962     1564920.851      360229.573
#Sta/Elev= 30
       0  819.11   334.5  870.84   846.1  764.93    1033   846.9  1741.3   908.9
  2036.5  809.72  2439.8  859.62  2587.4  818.13  2980.9  807.99  3649.9  865.42
  4181.2 1040.43  4466.5 1012.51  4909.2 1053.68  5184.7  966.88  7073.6  785.49
  7712.2  869.76  8252.5  831.79  9156.4  853.65  9657.5  968.85   10306  948.42
 10551.7  988.32 10836.7  885.51 11898.1  720.23 12065.2   753.4 12517.3  700.24
 12939.9  742.08 13461.2  658.33   13471     658 13588.6   658.4 14078.7  731.56
#Mann= 3 , 0 , 0
       0     .07       0 13461.2    .045       0 13588.6     .07       0
Bank Sta=13461.2,13588.6
XS Rating Curve= 0 ,0
Exp/Cntr=0.3,0.1

Type RM Length L Ch R = 1 ,97447.8 ,892.5,869.6,846.7
XS GIS Cut Line= 6
     1566539.491      351243.659     1567120.984      356762.478
     1565158.137      358285.972     1565163.907      358562.907
     1565073.629      358687.907     1564358.351      359455.268
#Sta/Elev= 30
       0  837.22     246   882.1     551  885.95   698.6  845.11  1210.2  788.81
  1574.3  903.39  2095.8  976.04  2666.4   827.7    3247   843.6  3630.7  705.22
  3768.4  683.79  3837.3  722.12  4211.2  812.21    4595  879.13    4959   905.7
  5126.3  946.22  5352.6  949.05  5549.4  890.26    5736  926.91  6050.2   943.6
  6207.4  900.68  6521.6  873.22  7032.3  764.11  7228.8  811.46  7945.7  803.06
  8720.2  658.34    8730  658.02  8837.8  658.39  9141.8  708.94  9514.3  704.73
#Mann= 3 , 0 , 0
       0     .09       0  8720.2    .045       0  8837.8     .07       0
Bank Sta=8720.2,8837.8
XS Rating Curve= 0 ,0
Exp/Cntr=0.3,0.1

Type RM Length L Ch R = 1 ,96578.2 ,752.3,734.6,716.8
XS GIS Cut Line= 3
     1564077.101      358309.434      1564309.74      359184.434
     1564379.184      359260.823
#Sta/Elev= 30
       0  847.21    39.4  824.32    68.9  806.64    78.7  800.16    88.6  791.58
    98.4  781.09   137.8  735.49   147.6  724.72   157.5  714.78   167.3  705.78
   177.1  697.79     187   690.9   196.8  685.17     246  660.92   255.9  658.46
   265.7     658   354.3  658.04   364.1  658.49     374  659.96   442.9  673.42
   511.8  681.54   521.6  682.25   541.3  682.61   600.3  680.93   659.4  681.43
     807  692.05   885.7     695   905.4  696.76   942.9  702.03  1008.6     705
#Mann= 3 , 0 , 0
       0      .1       0   255.9    .045       0   364.1     .07       0
Bank Sta=255.9,364.1
XS Rating Curve= 0 ,0
Exp/Cntr=0.3,0.1

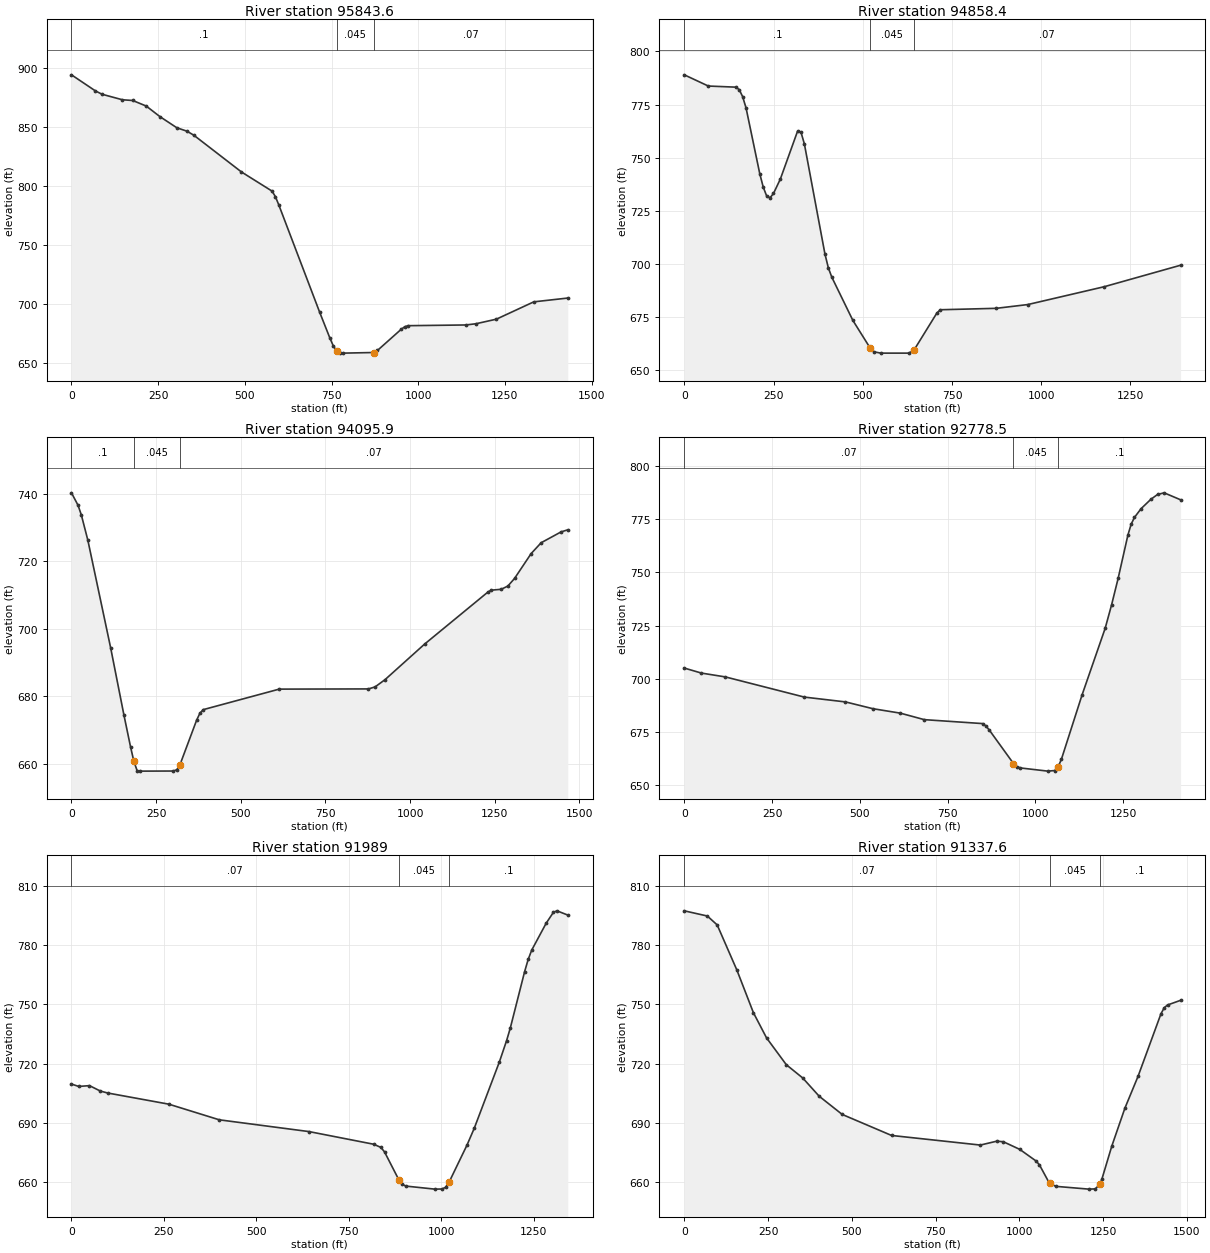
Type RM Length L Ch R = 1 ,95843.6 ,1004.7,985.2,965.8
XS GIS Cut Line= 2
     1563031.492      358786.411     1564268.073      359507.351
#Sta/Elev= 30
       0  894.12    68.6  880.56    88.2  877.63   147.1  872.94   176.5  872.36
   215.7  867.62   254.9   858.7   303.9   849.2   333.3  846.27     353  842.86
   490.2  811.72   578.4  795.48   588.2  790.73     598   783.7   715.7  692.78
   745.1  670.91   754.9   664.3   764.7  659.78   774.5  658.17   784.3     658
   872.6  658.53   882.4  660.25     951  678.23   960.8  680.27   970.6  681.28
  1137.3  681.89  1166.7  682.93  1225.5  686.81  1333.4  701.51  1431.4  704.73
#Mann= 3 , 0 , 0
       0      .1       0   764.7    .045       0   872.6     .07       0
Bank Sta=764.7,872.6
XS Rating Curve= 0 ,0
Exp/Cntr=0.3,0.1

Type RM Length L Ch R = 1 ,94858.4 ,778.6,762.5,746.4
XS GIS Cut Line= 4
     1562962.048      360216.966     1563365.296      360198.323
     1563976.407      359986.518     1564195.157      359726.101
#Sta/Elev= 30
       0     789    67.3  783.72   144.2   783.2   153.8  782.05   163.4  778.75
     173  773.42   211.4  742.48   221.1  736.17   230.7     732   240.3  731.13
   249.9  733.16   269.1  739.94   317.2   762.4   326.8  762.06   336.4  756.51
   394.1  704.63   403.7  698.06   413.5  693.67   472.3   673.4   521.3  660.25
   531.1  658.62   550.7     658   629.1     658     643  659.27   707.5  676.82
   717.3  678.42   874.1  679.09   962.3  680.86  1176.8  689.27  1390.6  699.38
#Mann= 3 , 0 , 0
       0      .1       0   521.3    .045       0     643     .07       0
Bank Sta=521.3,643
XS Rating Curve= 0 ,0
Exp/Cntr=0.3,0.1

Type RM Length L Ch R = 1 ,94095.9 ,1292,1317.4,1342.7
XS GIS Cut Line= 4
     1563851.696      360829.834     1563964.543      360803.792
     1564433.293       359992.16     1564826.528      359866.344
#Sta/Elev= 30
       0  740.23    19.3  736.56      29  733.73    48.3  726.23   115.8  694.33
   154.9  674.51   174.4  665.11   184.2  660.84   193.9  658.04   203.7   657.9
   301.3  657.93   311.1  658.31   320.2  659.73   369.7  672.98   379.4  675.04
   389.2  676.09   613.7  682.16   877.3  682.22   896.9  682.82   926.2  684.96
  1043.3   695.5    1230  710.87  1239.9  711.43  1269.4  711.69    1289  712.65
  1308.7  714.89  1357.8  722.26  1387.3  725.46  1446.3  728.68    1466  729.28
#Mann= 3 , 0 , 0
       0      .1       0   184.2    .045       0   320.2     .07       0
Bank Sta=184.2,320.2
XS Rating Curve= 0 ,0
Exp/Cntr=0.3,0.1

Type RM Length L Ch R = 1 ,92778.5 ,776.3,789.5,802.5
XS GIS Cut Line= 4
     1564007.512      361381.049     1565156.818      361467.855
     1565258.141      361460.785     1565404.653      361397.594
#Sta/Elev= 30
       0  705.01    48.8  702.65   117.2  700.84   341.9  691.35   459.1  689.08
   537.2  685.89   615.4  683.79   683.7  680.73   849.8  678.88   859.6  677.68
   869.3  675.72   937.7  660.07   947.5  658.64   957.2     658  1035.4   656.5
  1054.9  656.77  1064.7   658.4  1074.4   662.2    1133  692.36  1198.8  723.71
  1217.2  734.82  1235.7  747.18  1263.5  767.54  1272.9  772.75  1282.3  775.94
  1301.1  780.04  1329.2  784.48    1348  786.72  1366.8   787.5  1413.7  784.22
#Mann= 3 , 0 , 0
       0     .07       0   937.7    .045       0  1064.7      .1       0
Bank Sta=937.7,1064.7
XS Rating Curve= 0 ,0
Exp/Cntr=0.3,0.1

Type RM Length L Ch R = 1 ,91989   ,650.3,651.4,652.4
XS GIS Cut Line= 4
     1563859.617      361506.897     1564205.429      361822.021
     1564721.054      362217.855     1564924.179      362311.605
#Sta/Elev= 30
       0  709.62    19.5  708.42    48.7  708.82      78  706.09    97.5  705.11
   263.2  699.45   399.6  691.54   642.5  685.58   817.1  679.19   836.5  677.58
   846.2  675.34     885  661.19   894.8  658.84   904.4  658.03   982.1   656.5
  1001.5  656.56  1011.2   657.4  1020.9  660.07  1069.4  678.85  1088.8  687.27
  1156.8  720.85  1176.3  731.63    1186  737.77  1224.9  766.42  1234.6  772.65
  1244.3   777.4  1283.2  790.94  1302.7  796.43  1312.4   797.2  1341.6  795.06
#Mann= 3 , 0 , 0
       0     .07       0     885    .045       0  1020.9      .1       0
Bank Sta=885,1020.9
XS Rating Curve= 0 ,0
Exp/Cntr=0.3,0.1

Type RM Length L Ch R = 1 ,91337.6 ,249,237.9,226.4
XS GIS Cut Line= 4
     1563125.242      362038.147     1563773.137      362268.202
     1564250.568      362676.188     1564406.818      362732.611
#Sta/Elev= 30
       0  797.34    68.8  794.71    98.2   790.2   157.2  767.27   206.3  745.79
   245.6  733.02   304.5  719.47   353.6  712.74   402.7  703.51   471.4   694.3
   618.8  683.66   883.8   678.8   932.8  680.76   952.5  680.48  1001.5  676.62
  1050.6  670.69  1060.4  668.74  1090.3   659.4  1109.5   657.9  1207.6   656.5
  1227.2  656.62  1240.3  658.97  1246.8  661.61  1276.3  678.28  1315.5  697.52
  1354.6  713.56    1423   745.2  1432.8   748.3  1442.6  749.68  1481.7  752.05
#Mann= 3 , 0 , 0
       0     .07       0  1090.3    .045       0  1240.3      .1       0
Bank Sta=1090.3,1240.3
XS Rating Curve= 0 ,0
Exp/Cntr=0.3,0.1

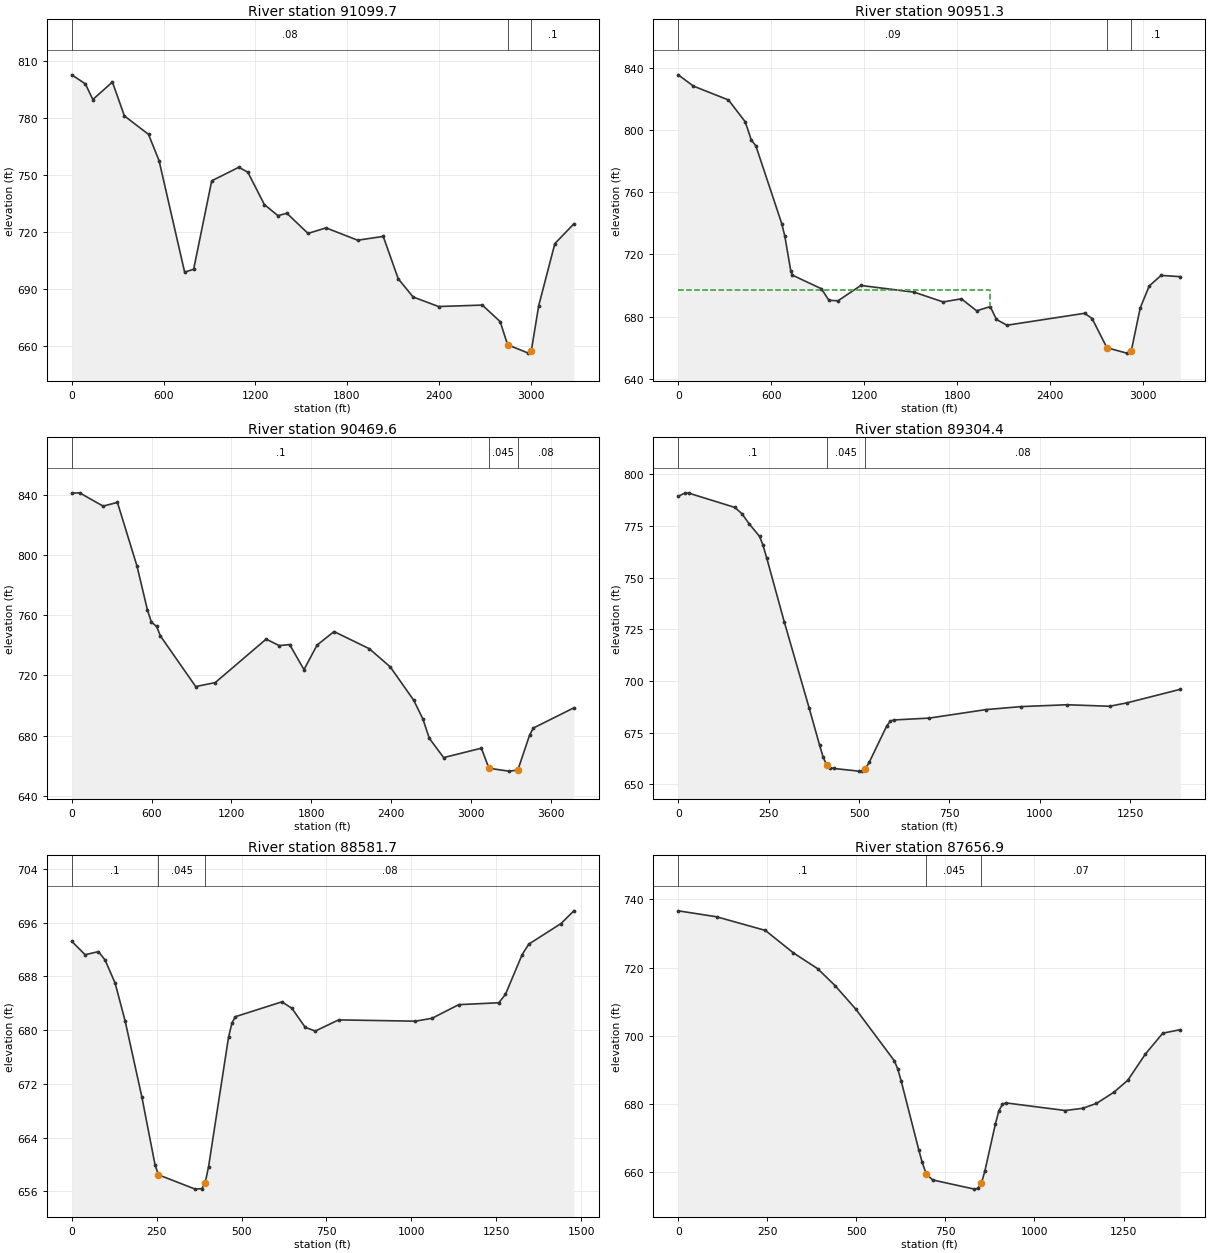
Type RM Length L Ch R = 1 ,91099.7 ,147.7,148.4,147.7
XS GIS Cut Line= 6
     1561220.793      361656.346     1563116.887      362549.452
     1563366.887      362591.118     1563681.991      362614.556
     1564098.658       362773.41     1564265.325      362815.077
#Sta/Elev= 30
       0  802.85    88.6  798.12   137.8  789.87   265.7  799.06   344.4  781.22
   501.8  771.55   570.7  757.78     738  699.13     797  700.58   915.1   747.1
  1092.2  754.24  1151.3  751.66  1259.5  734.63  1348.1   728.8  1407.1  730.03
  1544.9  719.46    1663  722.36  1869.6  715.88  2036.9  717.88  2134.9  695.61
  2232.4  686.02  2398.5  681.01    2685  681.76  2801.7  673.05  2850.1   660.9
  2985.7   656.5  3005.1   657.6  3053.5  681.43  3159.3  714.11  3283.4  724.47
#Mann= 3 , 0 , 0
       0     .08       0  2850.1    .045       0  3005.1      .1       0
Bank Sta=2850.1,3005.1
XS Rating Curve= 0 ,0
Exp/Cntr=0.3,0.1

Type RM Length L Ch R = 1 ,90951.3 ,486.4,481.6,475.8
XS GIS Cut Line= 6
     1561133.988      361851.658     1563033.554      362632.785
     1563283.554      362674.452     1563598.658      362697.889
     1564015.325      362856.743     1564181.991       362898.41
#Sta/Elev= 30
       0   835.5    98.3  828.24   324.3  819.34   432.4   805.3   471.7  793.58
   501.2  789.82   668.2  739.81   687.9  731.86   727.2  709.03     737  706.65
   923.8  697.94   972.9  690.46  1031.9   690.2  1179.3  700.04  1523.2   695.7
    1710  689.42  1827.9  691.43  1926.2  683.75  2014.6   686.4  2053.9  678.19
  2122.1  674.45  2623.6  682.13  2672.2  678.72  2767.4  659.97  2895.3   656.5
  2924.3  657.67  2982.4   685.5  3040.6   699.7  3117.3   706.5  3241.4  705.68
#Mann= 3 , 0 , 0
       0     .09       0  2767.4    .045       0  2924.3      .1       0
#XS Ineff= 2 , 0
         2012.33  696.82
Permanent Ineff=
       F       F
Bank Sta=2767.4,2924.3
XS Rating Curve= 0 ,0
Exp/Cntr=0.3,0.1

Type RM Length L Ch R = 1 ,90469.6 ,1184.6,1165.3,1148.7
XS GIS Cut Line= 5
     1560624.005       362198.88     1561894.641      363232.245
     1562813.502      362834.248     1563808.293      363089.456
     1563896.835      363026.956
#Sta/Elev= 30
       0  841.06    58.8  841.28   235.4  832.46   343.2  834.92   490.4  792.63
   568.8  763.51   598.2   755.5   637.5   752.6   666.9  746.19   931.7  712.64
  1078.8   715.3  1461.3  744.16  1559.3  739.85  1637.8  740.54  1745.8  723.88
    1844  740.19  1971.6  749.18  2236.6  737.78  2393.7  725.78  2570.4  703.61
  2639.1  691.25    2688   678.3  2795.6  665.48  3079.3  671.72  3136.2   658.4
  3284.7   656.5  3353.2  657.15  3441.2  680.26  3470.5  685.13  3774.5  698.52
#Mann= 3 , 0 , 0
       0      .1       0  3136.2    .045       0  3353.2     .08       0
Bank Sta=3136.2,3353.2
XS Rating Curve= 0 ,0
Exp/Cntr=0.3,0.1

Type RM Length L Ch R = 1 ,89304.4 ,738.6,722.7,706.7
XS GIS Cut Line= 2
     1562888.762      364180.875     1563829.734      363160.042
#Sta/Elev= 30
       0  789.25    19.6  790.94    29.3  790.78   156.4   783.9     176  780.88
   195.5  776.11   224.9  769.86   234.6  765.56   244.4  759.61   293.3  728.51
   361.8  687.06   391.1  668.82   400.9  663.09   410.6   659.3   420.4  658.05
   430.2  657.69   498.6   656.4   508.4  656.46   517.8  657.66     528  660.61
   576.8  678.32   586.6  680.58   596.4  681.14   694.2  682.04   850.6  686.14
   948.4   687.6  1075.5  688.49  1192.8  687.76  1241.7  689.44  1388.4  695.95
#Mann= 3 , 0 , 0
       0      .1       0   410.6    .045       0   517.8     .08       0
Bank Sta=410.6,517.8
XS Rating Curve= 0 ,0
Exp/Cntr=0.3,0.1

Type RM Length L Ch R = 1 ,88581.7 ,943.6,924.7,905.9
XS GIS Cut Line= 3
      1563755.45      364578.077     1563807.534      363213.494
     1563890.867      363137.105
#Sta/Elev= 30
       0  693.23    39.3  691.23    78.6   691.7    98.2  690.44   127.7     687
   157.2  681.36   206.3  670.08   245.6  659.85   255.4  658.46   363.5  656.33
   383.2   656.4     393  657.31   402.8  659.65   461.7  678.96   471.6  681.04
   481.4     682   618.9  684.22   648.4  683.25   687.7  680.41   717.2  679.87
   785.9  681.53  1011.9  681.34    1061  681.77  1139.6   683.8  1257.5  684.08
  1277.2  685.33  1326.3  691.25  1345.9  692.81  1440.9  695.88  1478.6  697.77
#Mann= 3 , 0 , 0
       0      .1       0   255.4    .045       0     393     .08       0
Bank Sta=255.4,393
XS Rating Curve= 0 ,0
Exp/Cntr=0.3,0.1

Type RM Length L Ch R = 1 ,87656.9 ,457.3,475,492.2
XS GIS Cut Line= 4
     1564380.863       364264.72     1564359.617      363668.355
     1563890.867      363210.022     1563923.998      363056.521
#Sta/Elev= 30
       0  736.62   107.6  734.88   244.6  730.88   322.8  724.33   391.3  719.67
   440.2  714.71   498.9  707.76   606.5   692.7   616.3  690.27   626.1  686.65
     675  666.67   684.8  662.92   696.3   659.5   714.2  657.76   831.6  655.07
   841.4  655.28   851.2  656.86   860.9  660.45   890.3  674.17   900.1  678.02
   909.9   679.9   919.6  680.34    1086  678.11  1134.9  678.74    1174  680.18
    1223  683.46  1262.2     687  1311.2  694.63  1360.3  700.78  1409.4  701.79
#Mann= 3 , 0 , 0
       0      .1       0   696.3    .045       0   851.2     .07       0
Bank Sta=696.3,851.2
XS Rating Curve= 0 ,0
Exp/Cntr=0.3,0.1