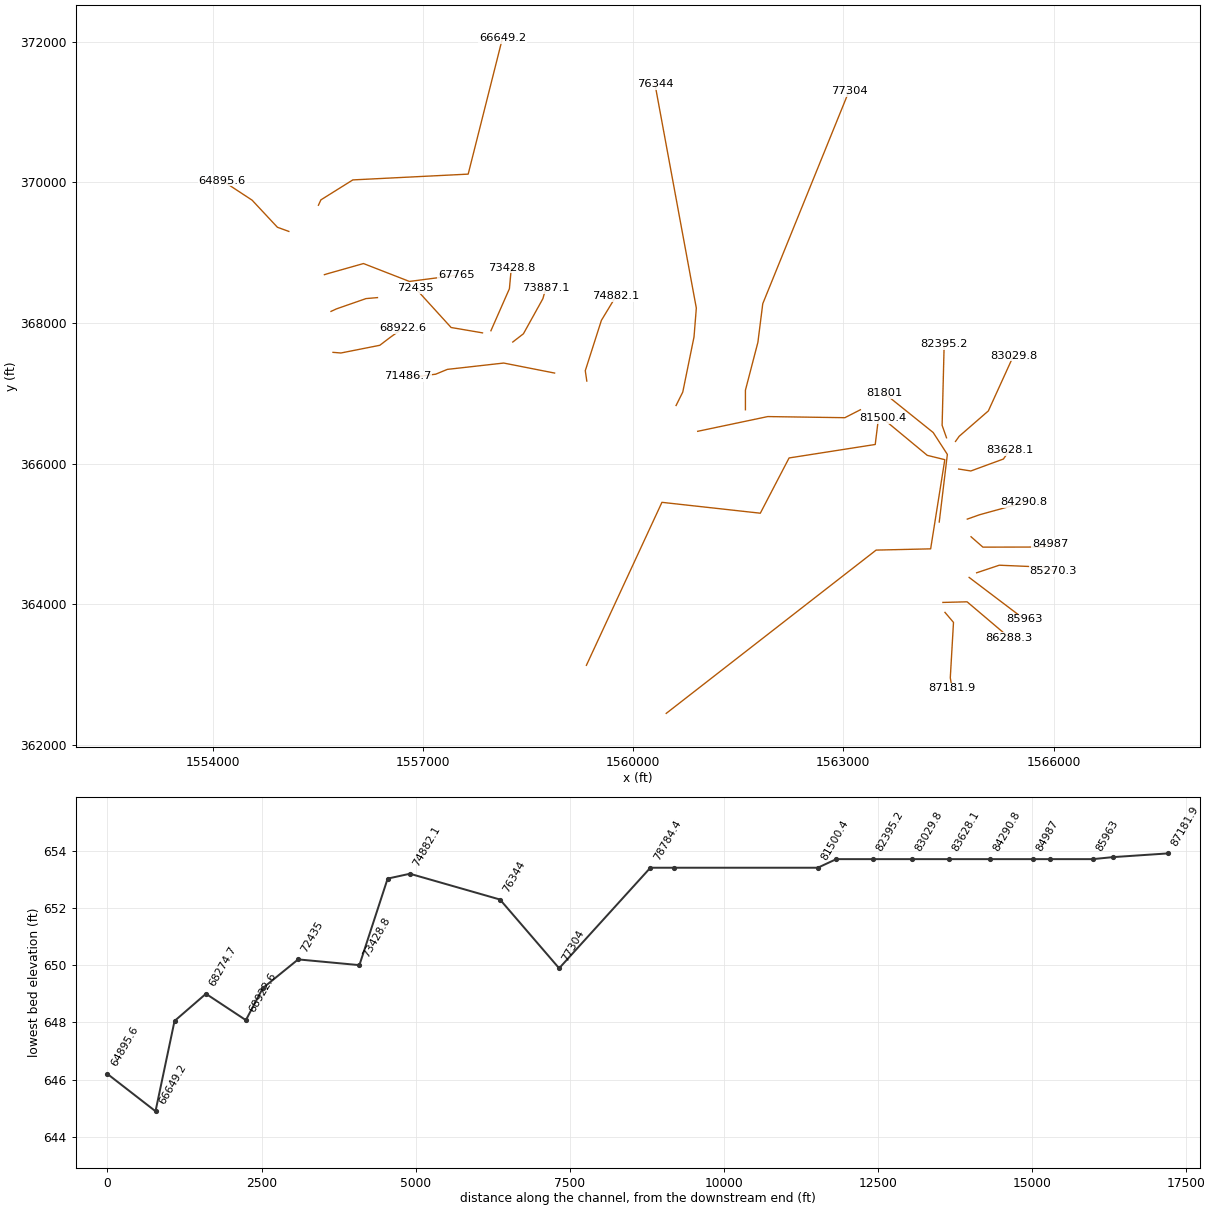
HEC-RAS study MDISLCRK1.prj: MDISLCRK1

--- MDISLCRK1.g02 (geometry) --- (continued)

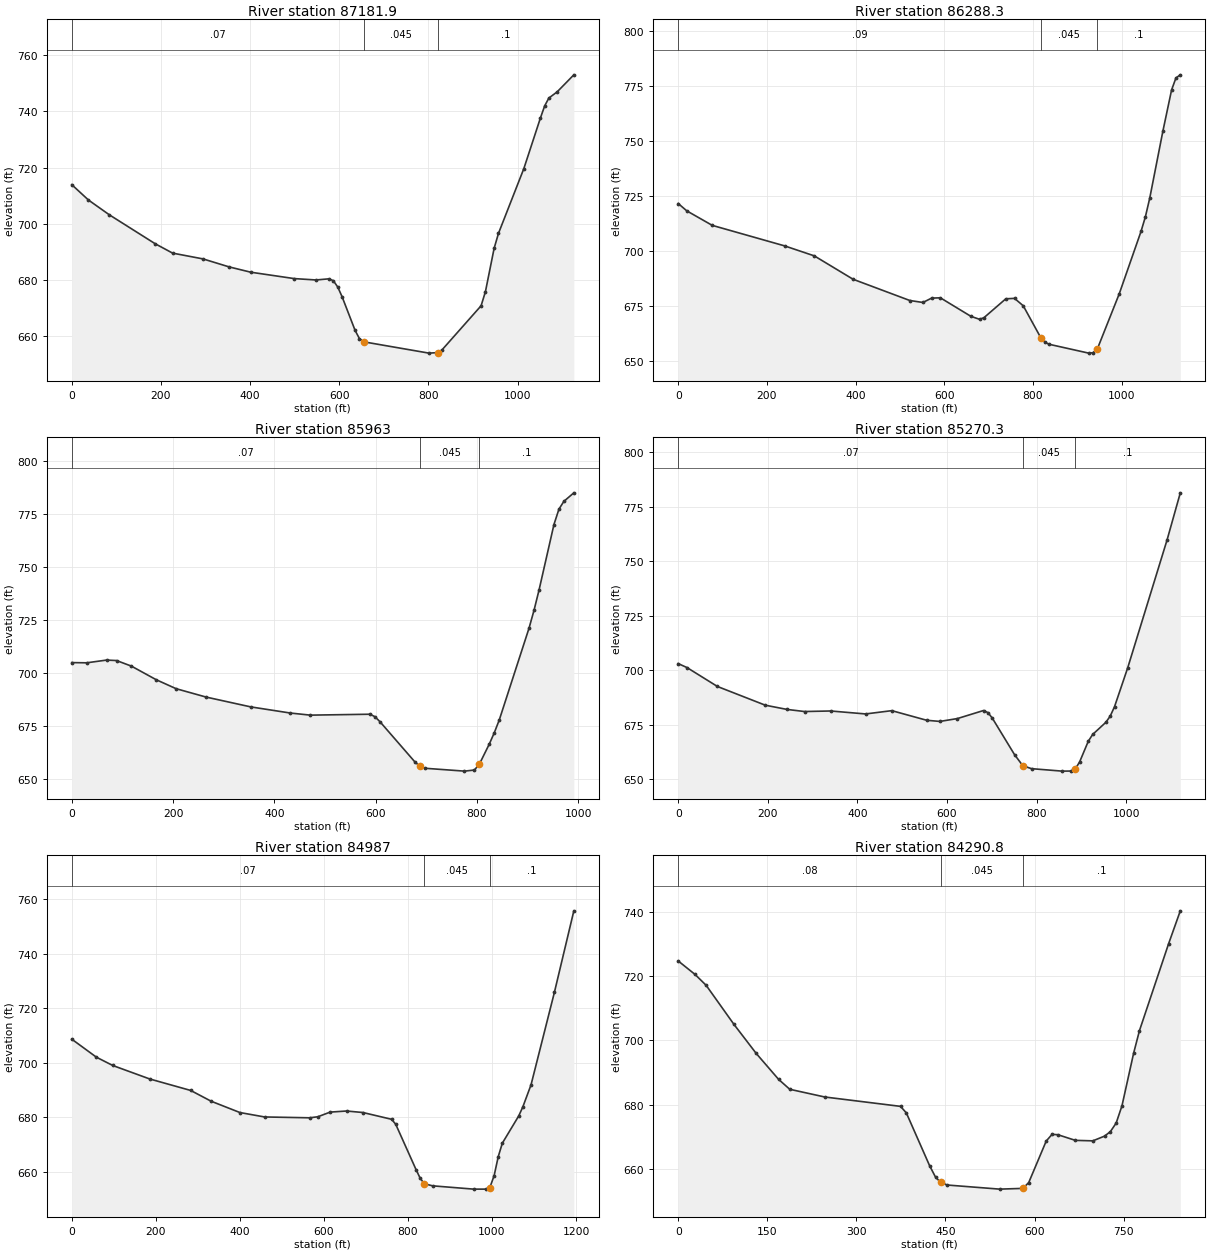
Type RM Length L Ch R = 1 ,87181.9 ,873.6,893.7,913.8
XS GIS Cut Line= 4
     1564450.394      363884.868     1564571.922      363742.507
     1564526.282      362954.457     1564551.168      362806.955
#Sta/Elev= 30
       0  713.89    37.4  708.42    84.2  703.16   187.2  692.84   226.2  689.51
   294.4  687.45   352.8  684.61   401.6  682.71     499  680.44   547.8  679.95
     577  680.36   586.7  679.68   596.5  677.46   606.2  674.02   635.5  661.98
   645.2  659.07     655  657.92   801.1   653.9   820.6  654.08   830.4  655.05
   918.1  670.77   927.8  675.79   947.3  691.22   957.1  696.56    1014  719.63
  1051.3  737.71  1060.7  741.94    1070  744.72  1088.7  746.94  1126.1     753
#Mann= 3 , 0 , 0
       0     .07       0     655    .045       0   820.6      .1       0
Bank Sta=655,820.6
XS Rating Curve= 0 ,0
Exp/Cntr=0.3,0.1

Type RM Length L Ch R = 1 ,86288.3 ,324,325.3,326.5
XS GIS Cut Line= 3
      1564420.96      364026.573     1564766.012      364035.253
      1565367.14      363527.441
#Sta/Elev= 30
       0  721.61    19.2  718.29    76.7   711.7   239.7  702.41   306.8  697.87
   394.3  687.26   522.2  677.63   551.7  676.74   571.4  678.72   591.1  678.85
   659.9  670.46   679.6  669.09   689.4  669.85   738.6   678.4   758.3   678.6
     778  675.22   817.6  660.72   827.1  658.65     837  657.75   925.5  653.77
   935.3  653.95   945.2  655.76   994.4  680.66  1043.5  708.95  1053.4  715.61
  1063.2  724.08  1092.7  754.32  1112.4  773.09  1122.2  778.53  1132.1  779.96
#Mann= 3 , 0 , 0
       0     .09       0   817.6    .045       0   945.2      .1       0
Bank Sta=817.6,945.2
XS Rating Curve= 0 ,0
Exp/Cntr=0.3,0.1

Type RM Length L Ch R = 1 ,85963   ,679.1,692.7,706.3
XS GIS Cut Line= 2
     1564795.012      364382.264     1565586.679      363785.042
#Sta/Elev= 30
       0  704.91    29.5  704.81    68.7   706.1    88.4  705.88   117.8  703.25
   166.9  696.82   206.2  692.59   265.1  688.66   353.5  684.01     432   681.1
   471.3  680.12   589.1  680.55   598.9  679.37   608.8  677.01   677.5  658.11
   687.3  656.05   697.1  655.06   775.7   653.7   795.3  654.22   805.1  656.99
   824.8  666.52   834.6  671.83   844.4  677.85   903.3  721.24   913.1  729.64
   922.9   739.1   952.4  770.06   962.2  777.29     972     781   991.7  785.02
#Mann= 3 , 0 , 0
       0     .07       0   687.3    .045       0   805.1      .1       0
Bank Sta=687.3,805.1
XS Rating Curve= 0 ,0
Exp/Cntr=0.3,0.1

Type RM Length L Ch R = 1 ,85270.3 ,282.6,283.3,283.9
XS GIS Cut Line= 4
     1564902.651      364448.236     1565225.568      364555.875
     1565878.345      364528.098     1565992.929      364472.542
#Sta/Elev= 30
       0  703.06    19.4  701.26    87.5  692.56   194.5  683.96   243.1  682.02
     282  681.06   340.4  681.31   418.4  679.95   476.9  681.46   554.9  677.04
   584.2  676.52   623.2  677.82   681.7  681.53   691.4  680.58   701.2  678.07
   750.9  661.28   769.5  656.16     789  654.83   857.2   653.7   876.7  653.74
   886.5  654.69   896.2  657.89   915.7  667.45   925.5  670.56   954.8   676.1
   964.5  678.92   974.2  683.27  1003.6   701.1  1091.7  759.95  1121.1  781.46
#Mann= 3 , 0 , 0
       0     .07       0   769.5    .045       0   886.5      .1       0
Bank Sta=769.5,886.5
XS Rating Curve= 0 ,0
Exp/Cntr=0.3,0.1

Type RM Length L Ch R = 1 ,84987   ,689.9,696.2,702
XS GIS Cut Line= 4
     1564822.435      364960.456     1564991.706      364812.886
     1565860.123      364814.514     1565951.269      364860.087
#Sta/Elev= 30
       0  708.72    58.6  702.11    97.6  699.06   185.5  694.12   283.1   689.9
   331.9  685.94   400.2   681.8   458.8  680.18   566.1  679.87   585.6  680.25
   614.9  681.96   653.9  682.36   692.9  681.81   761.2  679.32     771   677.5
   819.8  660.71   829.5  657.61   839.3  655.67   858.8  654.91   956.4   653.7
   985.6   653.7   994.8  654.19  1005.2  658.65  1014.9  665.57  1024.7  670.56
  1063.7  680.55  1073.5  683.87    1093  691.96  1148.6  725.88  1194.9  755.81
#Mann= 3 , 0 , 0
       0     .07       0   839.3    .045       0   994.8      .1       0
Bank Sta=839.3,994.8
XS Rating Curve= 0 ,0
Exp/Cntr=0.3,0.1

Type RM Length L Ch R = 1 ,84290.8 ,660.7,662.7,665
XS GIS Cut Line= 3
       1564768.6      365211.497     1564945.683      365273.997
     1565579.734      365448.236
#Sta/Elev= 30
       0  724.77    28.2  720.59      47  717.19    93.9     705   131.4  695.95
     169  687.89   187.8   684.8   246.7   682.4   374.3  679.48   384.1  677.44
   423.3  660.98   433.2  657.45   441.8   655.8   452.8  654.98   541.1   653.7
   580.4  653.93   590.2  655.76   619.6  668.67   629.4  670.76   639.2  670.65
   668.7  668.89   698.1  668.74   717.8  670.21   727.6   671.6   737.4  674.28
   747.2  679.68   766.8  696.05   776.6  703.07   825.7  730.15   845.4  740.39
#Mann= 3 , 0 , 0
       0     .08       0   441.8    .045       0   580.4      .1       0
Bank Sta=441.8,580.4
XS Rating Curve= 0 ,0
Exp/Cntr=0.3,0.1

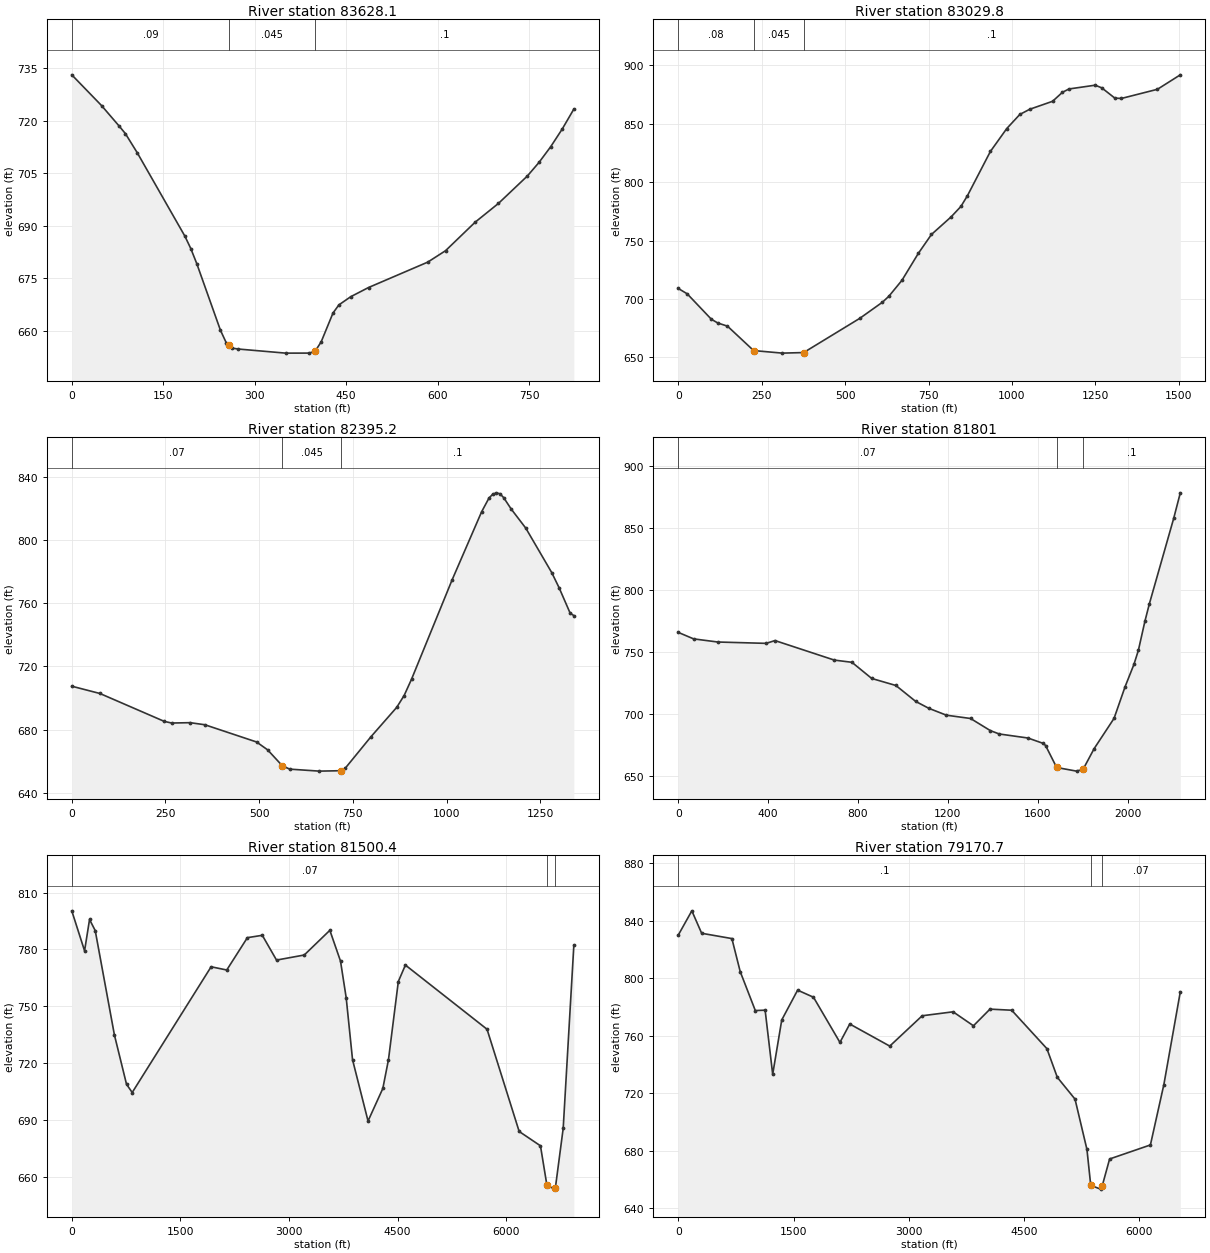
Type RM Length L Ch R = 1 ,83628.1 ,589.8,598.4,606.9
XS GIS Cut Line= 4
     1564645.706      365923.931     1564819.318      365896.153
     1565284.595      366066.292     1565371.401      366191.292
#Sta/Elev= 30
       0  733.06    48.8   724.3    78.1  718.37    87.9  716.31   107.4  710.84
   185.5  687.06   195.2  683.52     205  679.22   243.8  660.24   253.5  656.59
   258.1  655.89   263.2  655.12     273  654.87   350.7   653.7   389.5  653.71
   399.2  654.26     409  656.91   428.4  665.13   438.1  667.46   457.5  669.79
   486.7  672.41   583.8  679.65     613  682.91   661.5  691.03   699.8   696.4
   747.3  704.23   766.3  708.09   785.4  712.55   804.4  717.62   823.4  723.29
#Mann= 3 , 0 , 0
       0     .09       0   258.1    .045       0   399.2      .1       0
Bank Sta=258.1,399.2
XS Rating Curve= 0 ,0
Exp/Cntr=0.3,0.1

Type RM Length L Ch R = 1 ,83029.8 ,616,634.6,652.8
XS GIS Cut Line= 4
     1564600.568      366316.292     1564652.651      366389.209
     1565069.318       366750.32     1565428.266      367535.868
#Sta/Elev= 30
       0  709.07    26.9  704.45    99.3  682.69   118.6  679.48   147.6  676.78
   225.9  655.89   312.1   653.7   375.9  654.19   544.2   683.5     612  697.29
   631.3   702.4   670.4  716.01   719.5  739.08   758.8  755.25   817.6  770.27
   847.1  779.24   866.7  788.46   935.4  826.29   984.5  845.91  1023.7     858
  1053.2  862.41  1121.9  869.26  1151.3  876.94    1171   879.8  1249.5  883.03
  1269.1  880.77  1308.4  871.98    1328  871.67    1436  879.52  1504.6   891.9
#Mann= 3 , 0 , 0
       0     .08       0   225.9    .045       0   375.9      .1       0
Bank Sta=225.9,375.9
XS Rating Curve= 0 ,0
Exp/Cntr=0.3,0.1

Type RM Length L Ch R = 1 ,82395.2 ,573.4,594.2,614.9
XS GIS Cut Line= 3
     1564472.095      366368.375     1564409.595      366545.459
     1564438.682      367696.458
#Sta/Elev= 30
       0   707.4    75.1  702.79   246.8  685.15   266.5  684.11   315.7  684.34
   355.1  683.02   492.8  672.14   522.4  667.16   561.7  657.06   581.4  654.96
   660.1   653.7   719.2  653.97     729   655.4   797.9  675.41   866.8  694.04
   886.5   701.5   906.2  711.78  1014.4  774.59  1093.1  817.64  1112.8  826.36
  1122.7  828.75  1132.5  829.68  1142.3  829.06  1152.2  826.59  1171.9  819.49
  1211.2  807.28  1280.1  779.29  1299.8   769.7  1329.3  753.62  1339.2  752.04
#Mann= 3 , 0 , 0
       0     .07       0   561.7    .045       0   719.2      .1       0
Bank Sta=561.7,719.2
XS Rating Curve= 0 ,0
Exp/Cntr=0.3,0.1

Type RM Length L Ch R = 1 ,81801   ,300.9,300.6,300.3
XS GIS Cut Line= 4
     1564368.369      365169.816     1564484.303       366131.65
     1564282.094      366443.257     1563583.648      367002.014
#Sta/Elev= 30
       0  765.82    68.5  760.56   176.1  758.03   391.4  756.94   430.6   759.2
   694.8  743.42   773.1  741.64   861.2  728.58   968.8   722.9  1056.8  710.04
  1115.4  704.45  1193.6   698.9  1301.2  696.23  1389.4  686.42  1428.7  683.72
  1556.5  680.46  1625.3  676.06  1635.1  674.36  1684.3  656.64  1772.7   653.7
  1802.2  655.24  1851.4  671.95  1939.8  696.33    1989  721.96  2028.3  739.94
    2048  751.27  2077.4  775.02  2097.1  788.99  2205.2  857.92  2234.7  878.58
#Mann= 3 , 0 , 0
       0     .07       0  1684.3    .045       0  1802.2      .1       0
Bank Sta=1684.3,1802.2
XS Rating Curve= 0 ,0
Exp/Cntr=0.3,0.1

Type RM Length L Ch R = 1 ,81500.4 ,2384.8,2329.7,2274.1
XS GIS Cut Line= 6
     1560472.095      362448.446     1563467.671      364770.766
     1564245.836      364788.512     1564447.858      366056.998
      1564197.79      366118.375     1563562.373      366642.681
#Sta/Elev= 30
       0  800.42   176.8  779.29   245.5  795.85     324  789.97   589.2  734.81
   756.1  708.82   834.7  704.44  1924.6  770.86  2140.7  769.16  2425.4  786.24
  2631.6  787.49    2828   774.4    3211  777.08  3564.5  790.12  3711.8  773.85
  3790.3  754.48  3877.9  721.76    4092  689.38  4296.3  706.58  4374.1  721.76
  4510.3  763.08  4607.9  771.77  5735.5  737.86  6179.3  683.86  6473.5  676.28
  6561.8  655.61  6659.9   653.4  6679.5  654.08  6787.4  685.48  6934.5  782.21
#Mann= 3 , 0 , 0
       0     .07       0  6561.8    .045       0  6679.5      .1       0
Bank Sta=6561.8,6679.5
XS Rating Curve= 0 ,0
Exp/Cntr=0.3,0.1

Type RM Length L Ch R = 1 ,79170.7 ,386.7,386.3,386
XS GIS Cut Line= 6
     1559332.772       363132.04     1560410.695      365450.113
     1561814.804      365295.532     1562225.272      366081.305
     1563455.015      366273.043     1563503.626      366668.876
#Sta/Elev= 30
       0  829.96     177  846.87   304.8  831.26   698.1  827.58   806.3  804.64
  1002.9  777.54  1130.7   777.8  1229.1  733.22    1347  771.02  1553.5  791.73
    1760   786.8  2104.2  755.39    2232  768.19  2752.6  752.83  3174.4  773.92
  3576.6  776.67  3841.5  766.96  4056.7  778.53  4339.2  777.77  4797.1  751.07
  4932.5  731.15  5163.2  715.97  5318.5  680.95  5367.7  656.04  5495.5   653.4
  5515.1  655.26  5613.4  674.36  6144.2  684.11  6319.3  726.09  6533.3  790.61
#Mann= 3 , 0 , 0
       0      .1       0  5367.7    .045       0  5515.1     .07       0
Bank Sta=5367.7,5515.1
XS Rating Curve= 0 ,0
Exp/Cntr=0.3,0.1

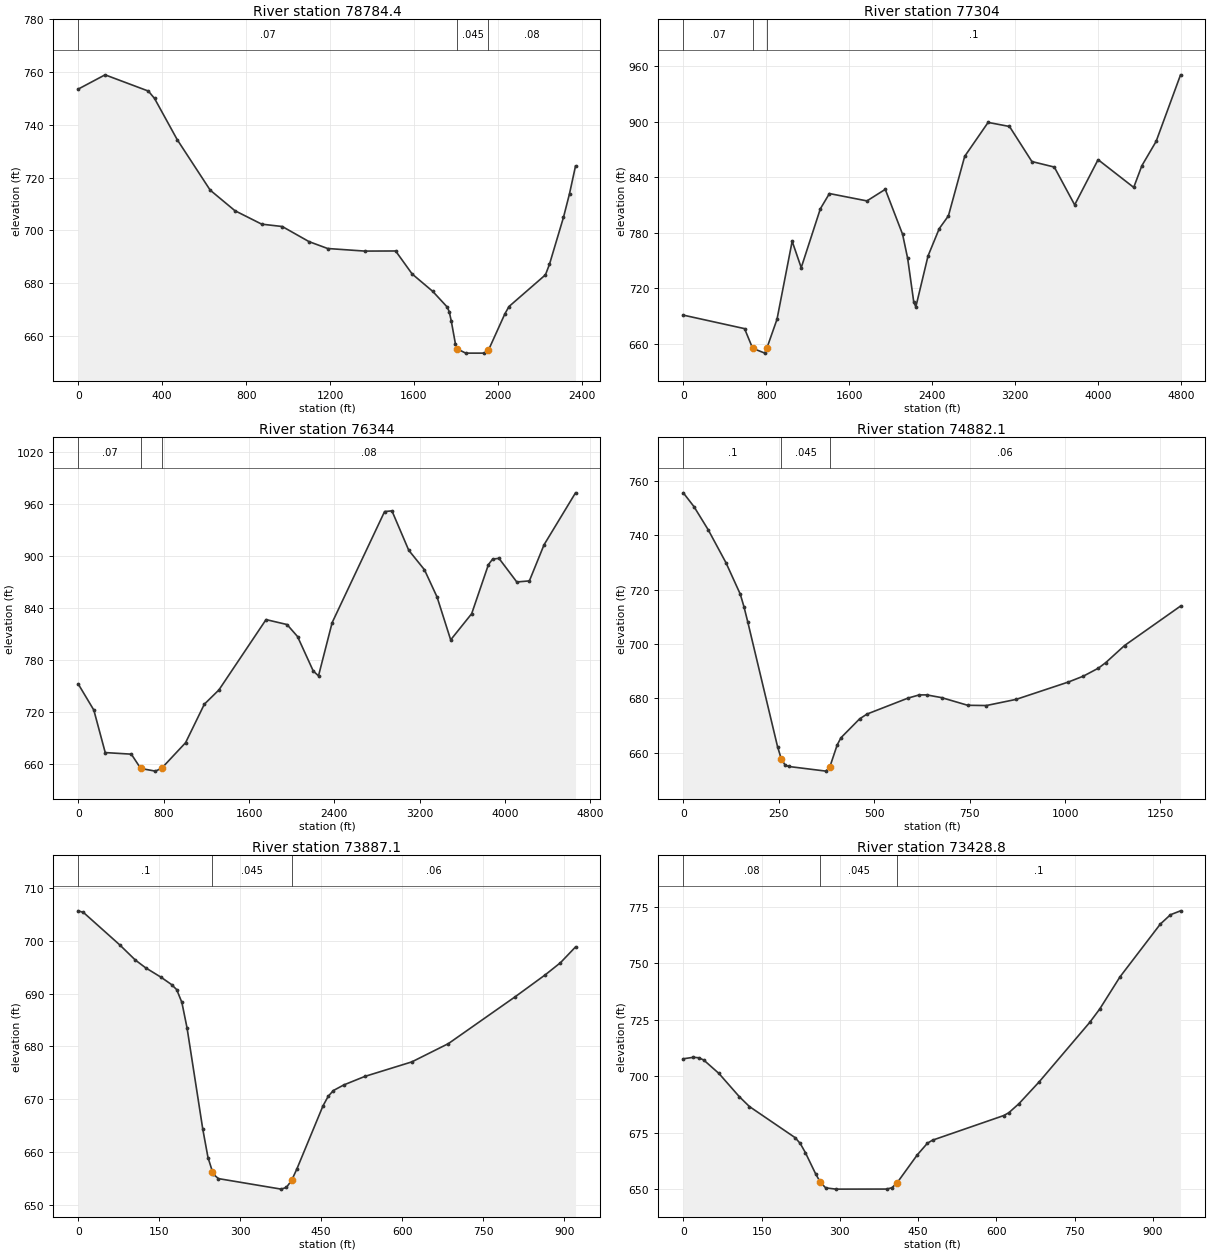
Type RM Length L Ch R = 1 ,78784.4 ,1450.4,1480.4,1510.4
XS GIS Cut Line= 4
     1560921.321      366460.347     1561921.339      366669.911
     1563021.575      366653.966     1563242.929      366766.813
#Sta/Elev= 30
       0   753.6   127.7     759     334  752.84   363.5  750.05   471.6  734.41
   628.8  715.25   746.7  707.45   874.4  702.34   972.6  701.44  1100.3   695.7
  1188.8   693.1  1365.6  692.12    1513  692.16  1591.6  683.44  1689.8  676.84
  1758.6  670.91  1768.4  669.15  1778.2   665.6  1797.9  656.96  1807.7  654.96
    1847   653.4  1935.4   653.4  1955.1  654.46  2033.7  668.29  2053.3  671.08
  2227.2  683.11  2246.3  687.09  2313.2  704.93  2341.9   713.9  2370.6  724.42
#Mann= 3 , 0 , 0
       0     .07       0  1807.7    .045       0  1955.1     .08       0
Bank Sta=1807.7,1955.1
XS Rating Curve= 0 ,0
Exp/Cntr=0.3,0.1

Type RM Length L Ch R = 1 ,77304   ,959.3,960,960.6
XS GIS Cut Line= 5
     1561602.304      366766.813     1561602.304      367044.591
     1561780.255      367726.014     1561849.752      368275.374
     1563079.344      371295.547
#Sta/Elev= 30
       0  690.96   590.8  676.36     669   655.1   786.4  649.89     806  655.28
   903.8  686.41  1050.1   770.8  1137.5  742.24  1322.1   805.9  1409.5  822.34
  1771.5  814.39  1948.3  826.89  2115.3  778.31  2164.4   752.2  2223.3  704.96
    2243  699.85  2360.8  754.92  2468.9  784.45  2557.3  798.21  2714.4  862.56
  2940.3  899.22  3146.6  894.82  3362.7  856.93  3578.8  850.97  3775.2  810.11
  4001.1  858.95  4344.9  828.98  4423.4  852.42    4561   878.7  4796.7  950.64
#Mann= 3 , 0 , 0
       0     .07       0     669    .045       0     806      .1       0
Bank Sta=669,806
XS Rating Curve= 0 ,0
Exp/Cntr=0.3,0.1

Type RM Length L Ch R = 1 ,76344   ,1463.7,1461.9,1459.9
XS GIS Cut Line= 5
      1560612.72      366827.577     1560708.206      367018.549
     1560868.797      367804.139     1560901.637      368212.814
     1560312.417      371393.203
#Sta/Elev= 30
       0   752.6   145.6  722.65   252.6  673.67   497.1  671.83   585.1  655.38
     722  652.29   780.7  655.51  1005.6  685.05  1181.3   729.4    1318  745.85
  1759.6  826.88  1956.2  821.19  2054.6  807.38    2202  767.66  2251.2  762.05
    2379  823.38  2870.6  951.38  2939.4  952.16  3096.7  906.81  3244.1   884.3
  3362.1  852.92  3489.9  803.53  3686.6  833.68  3843.8  890.33  3883.2   896.6
  3942.2  897.48  4109.3  870.24  4227.3  871.47  4364.9   913.1  4659.8  972.94
#Mann= 3 , 0 , 0
       0     .07       0   585.1    .045       0   780.7     .08       0
Bank Sta=585.1,780.7
XS Rating Curve= 0 ,0
Exp/Cntr=0.3,0.1

Type RM Length L Ch R = 1 ,74882.1 ,362.6,361.1,359.7
XS GIS Cut Line= 4
     1559338.415      367174.799     1559316.713      367322.368
     1559546.748      368038.514     1559755.081      368381.396
#Sta/Elev= 30
       0  755.69      28   750.6    65.3  742.06   111.9  729.91   149.2  718.38
   158.9  713.74   168.7  708.24   246.8  662.25   256.6  657.71   266.4  655.49
   276.2   654.9   373.8  653.19   383.6  654.64   403.1  662.83   412.9  665.47
   461.8  672.43   481.3  674.21   588.7  680.09     618  681.26   637.6  681.27
   676.7  680.26     745  677.44   793.9  677.35     872  679.62    1009  686.02
  1048.1  688.18  1087.3  691.11  1106.8  693.17  1155.8  699.44  1302.6  713.99
#Mann= 3 , 0 , 0
       0      .1       0   256.6    .045       0   383.6     .06       0
Bank Sta=256.6,383.6
XS Rating Curve= 0 ,0
Exp/Cntr=0.3,0.1

Type RM Length L Ch R = 1 ,73887.1 ,456.2,458.3,460.4
XS GIS Cut Line= 4
     1558281.991      367730.355     1558433.901      367847.542
     1558711.679      368346.674     1558755.081      368498.584
#Sta/Elev= 30
       0  705.65     9.6  705.34    76.7  699.22   105.5  696.36   124.7  694.88
   153.5  693.08   172.7  691.71   182.3  690.75   191.9  688.33   201.5   683.5
   230.6  664.38   240.3  658.99   248.6  656.31     250  655.86   259.6  655.01
   375.8  653.02   385.5  653.34   395.2  654.67   404.9  656.83   453.3  668.77
     463  670.58   472.6  671.67     492  672.73   530.7  674.33   617.8  677.08
   685.6  680.54   809.6  689.42   865.3  693.57   893.2  695.84   921.1  698.82
#Mann= 3 , 0 , 0
       0      .1       0   248.6    .045       0   395.2     .06       0
Bank Sta=248.6,395.2
XS Rating Curve= 0 ,0
Exp/Cntr=0.3,0.1

Type RM Length L Ch R = 1 ,73428.8 ,967.8,993.8,1019.9
XS GIS Cut Line= 3
     1557969.932      367890.903     1558233.821      368488.125
     1558261.599      368786.736
#Sta/Elev= 30
       0  707.73    19.5  708.39    29.2  708.19      39  707.21    68.2  701.25
   107.2  690.98   126.7  686.58   214.4  672.78   224.1  670.21   233.9  666.18
   253.4  656.85   262.7  653.01   272.9  650.55   292.4     650   389.8  650.03
   399.6  650.61   409.3  652.69   448.3  665.16   467.8  670.35   477.5  671.68
   613.9  682.58   623.7  683.83   643.2  687.86     682  697.54   778.7  723.83
     798   729.8   836.7     744   914.1  767.41   933.5  771.53   952.8  773.26
#Mann= 3 , 0 , 0
       0     .08       0   262.7    .045       0   409.3      .1       0
Bank Sta=262.7,409.3
XS Rating Curve= 0 ,0
Exp/Cntr=0.3,0.1

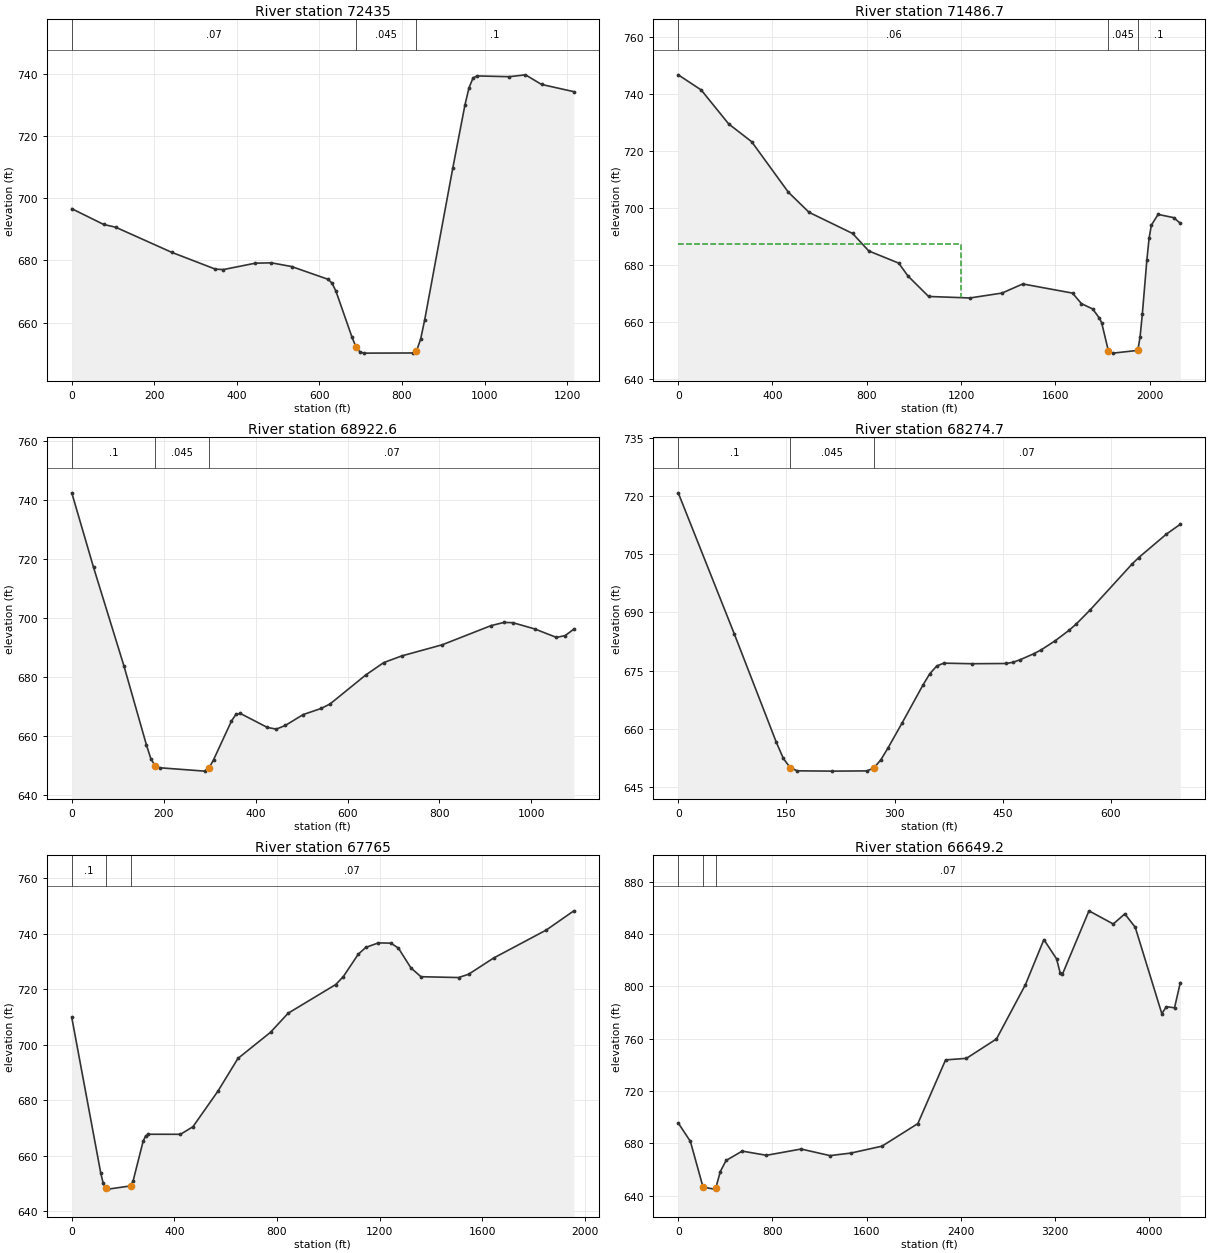
Type RM Length L Ch R = 1 ,72435   ,550.6,572.8,595
XS GIS Cut Line= 3
       1557849.7      367860.563     1557401.783      367936.952
     1556887.894      368499.452
#Sta/Elev= 30
       0   696.6    77.3  691.54   106.4  690.65   241.7  682.61     348  677.18
   367.4  677.05   444.7   679.1   483.7  679.21   532.5  678.02   620.4  673.94
   630.2  672.73     640   670.1     679  655.27   688.8  652.11   698.6  650.53
   708.4   650.2   825.6  650.25     834  650.87   835.3  650.97   845.1  654.67
   854.9  660.84   923.2  709.76   952.6     730   962.3  735.43   972.1  738.61
   981.8  739.26    1060  739.01  1099.1  739.61  1138.1  736.52  1216.3   734.2
#Mann= 3 , 0 , 0
       0     .07       0   688.8    .045       0     834      .1       0
Bank Sta=688.8,834
XS Rating Curve= 0 ,0
Exp/Cntr=0.3,0.1

Type RM Length L Ch R = 1 ,71486.7 ,270.2,275.6,281.1
XS GIS Cut Line= 6
     1558878.678      367288.838     1558152.444      367431.229
     1557348.405      367341.134     1557181.644      367272.716
     1556877.825      367232.785     1556784.075      367241.466
#Sta/Elev= 30
       0  746.66    97.4  741.36   214.2  729.46   311.6  723.24   467.4  705.55
     555  698.52   740.1   691.1   808.6  684.98   935.7  680.72   974.9  676.21
  1062.6  669.04    1238  668.52  1374.4  670.24  1462.1  673.43  1673.2  670.22
  1711.1  666.54  1758.8  664.66  1787.6  661.42  1797.1  659.79  1825.9  649.82
    1845   649.2  1950.4  650.16  1959.9  654.83  1969.5  662.85  1988.7  681.76
  1998.2   689.4  2007.8  694.01  2036.5  697.78  2102.4  696.65  2130.7  694.69
#Mann= 3 , 0 , 0
       0     .06       0  1825.9    .045       0  1950.4      .1       0
#XS Ineff= 2 , 0
         1199.63   687.4
Permanent Ineff=
       F       F
Bank Sta=1825.9,1950.4
XS Rating Curve= 0 ,0
Exp/Cntr=0.3,0.1

Type RM Length L Ch R = 1 ,68922.6 ,644.7,647.9,651.1
XS GIS Cut Line= 5
     1555716.193      367583.393     1555829.387      367574.365
     1556384.075       367683.74       1556524.7      367790.511
     1556717.408      367928.532
#Sta/Elev= 30
       0  742.48    47.3  717.23   113.6  683.73   162.3  657.05     172  652.33
   181.8  649.79   191.5  649.22     289  648.08   298.8  649.18   308.5  651.93
   347.5  665.08   357.2  667.33     367  667.63   425.5  662.91     445  662.33
   464.5  663.56   503.5  667.26   542.4  669.33     562  670.86   639.9  680.72
   678.9   684.9   718.2  687.17   806.4  690.95   912.4  697.44   940.8  698.53
   959.8  698.43  1007.2  696.32  1054.6  693.44  1073.6  694.05  1092.5  696.24
#Mann= 3 , 0 , 0
       0      .1       0   181.8    .045       0   298.8     .07       0
Bank Sta=181.8,298.8
XS Rating Curve= 0 ,0
Exp/Cntr=0.3,0.1

Type RM Length L Ch R = 1 ,68274.7 ,511.1,509.7,508.4
XS GIS Cut Line= 4
     1555687.547      368165.858     1555767.408      368202.316
     1556187.547       368348.15     1556350.741      368362.039
#Sta/Elev= 30
       0  720.93      78  684.35   136.1  656.42   145.8  652.27   155.5  649.84
   165.1  649.08   213.5     649   261.8  649.06   271.5  649.85   281.2  651.99
   290.8  654.95   310.2  661.36   339.2  671.19   348.8  674.16   358.5  676.17
   368.2  676.91   406.8  676.76   455.2  676.82   464.8  677.16   474.5  677.82
   493.8   679.4   503.5  680.36   522.8   682.7   542.2  685.43   551.8     687
   571.1  690.63   628.9  702.43   638.5  704.18     677  710.26   696.3  712.81
#Mann= 3 , 0 , 0
       0      .1       0   155.5    .045       0   271.5     .07       0
Bank Sta=155.5,271.5
XS Rating Curve= 0 ,0
Exp/Cntr=0.3,0.1

Type RM Length L Ch R = 1 ,67765   ,308,308.5,308.8
XS GIS Cut Line= 5
     1555593.797      368688.427      1555645.88      368704.052
     1556151.088      368846.414     1556806.738      368592.002
     1557475.141      368678.808
#Sta/Elev= 30
       0  709.89   112.7  653.96   122.4  650.17   132.1  648.36   141.9  648.05
   229.3  649.21   239.1  651.04   277.9  665.22   287.7  667.21   297.4  667.82
   423.7   667.8   472.3  670.54   569.5  683.33   647.6  695.13   774.6  704.55
     843   711.4  1028.6  721.74  1057.9  724.56  1116.5  732.67  1145.8  735.11
  1194.6  736.74  1243.5  736.65  1272.8  734.88  1321.6  727.75  1360.7  724.56
  1507.2  724.26  1546.3  725.44    1644  731.29  1849.1  741.37  1956.6  748.29
#Mann= 3 , 0 , 0
       0      .1       0   132.1    .045       0   229.3     .07       0
Bank Sta=132.1,229.3
XS Rating Curve= 0 ,0
Exp/Cntr=0.3,0.1

Type RM Length L Ch R = 1 ,66649.2 ,751.4,779.5,807.6
XS GIS Cut Line= 5
     1555508.293      369675.841     1555543.016      369751.796
     1555999.179      370036.084      1557645.49      370118.402
      1558134.32      372049.688
#Sta/Elev= 30
       0  695.49   103.1   681.4   210.6   646.4   308.3   644.9   318.1  645.54
   357.2  658.35     406  666.79   542.8  673.97   748.6  670.76  1042.9  675.55
  1288.2  670.52  1464.8  672.46  1729.7  677.75  2033.9  695.02  2269.4   743.7
    2446  744.87  2701.2  759.71  2946.5  801.12  3103.6  835.65  3211.5  820.89
  3240.9  810.44  3260.6   809.1  3486.3  857.65  3692.4  847.59  3790.5  855.32
  3878.8  845.12  4104.6  779.07  4143.8  784.39  4212.5  783.52  4261.6  802.78
#Mann= 3 , 0 , 0
       0      .1       0   210.6    .045       0   318.1     .07       0
Bank Sta=210.6,318.1
XS Rating Curve= 0 ,0
Exp/Cntr=0.3,0.1

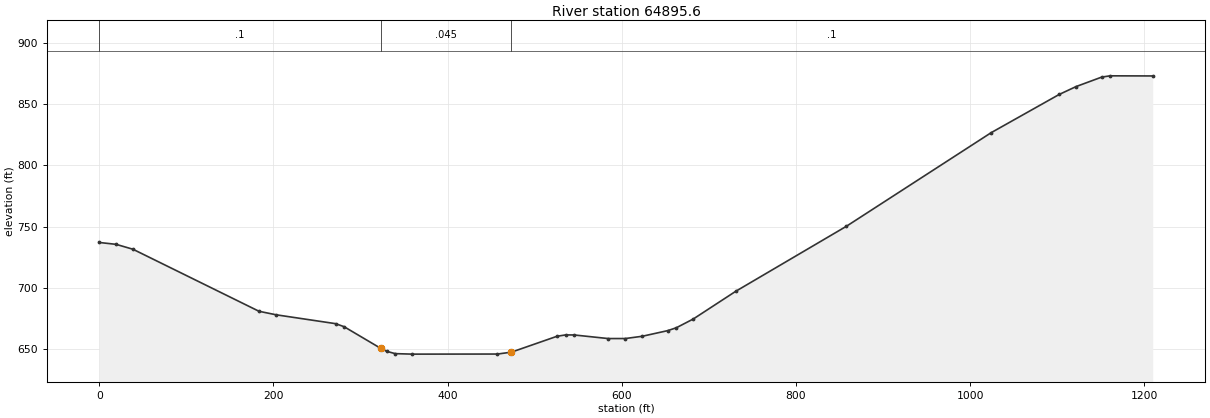
Type RM Length L Ch R = 1 ,64895.6 ,528.4,529.1,529.8
XS GIS Cut Line= 4
     1555085.984      369303.445      1554922.79      369362.473
     1554561.679      369747.889     1554136.599       370026.03
#Sta/Elev= 30
       0  737.22    19.3   735.7    38.6  731.71   183.3  681.15   202.9  678.28
   271.4  671.03   281.1  668.55   323.2  650.89     330  648.48   339.8   646.6
   359.4   646.2   457.2  646.27   473.2   647.8   525.6  660.76   535.4  661.86
   545.2  661.83   584.3   658.9   603.9  658.91   623.4  660.75   652.8  665.37
   662.6   667.7   682.1  674.86     731   697.5     858  750.47  1024.1  826.72
  1102.2  857.88  1121.8  864.37  1151.1  872.06  1160.8  873.09  1209.7  872.99
#Mann= 3 , 0 , 0
       0      .1       0   323.2    .045       0   473.2      .1       0
Bank Sta=323.2,473.2
XS Rating Curve= 0 ,0
Exp/Cntr=0.3,0.1