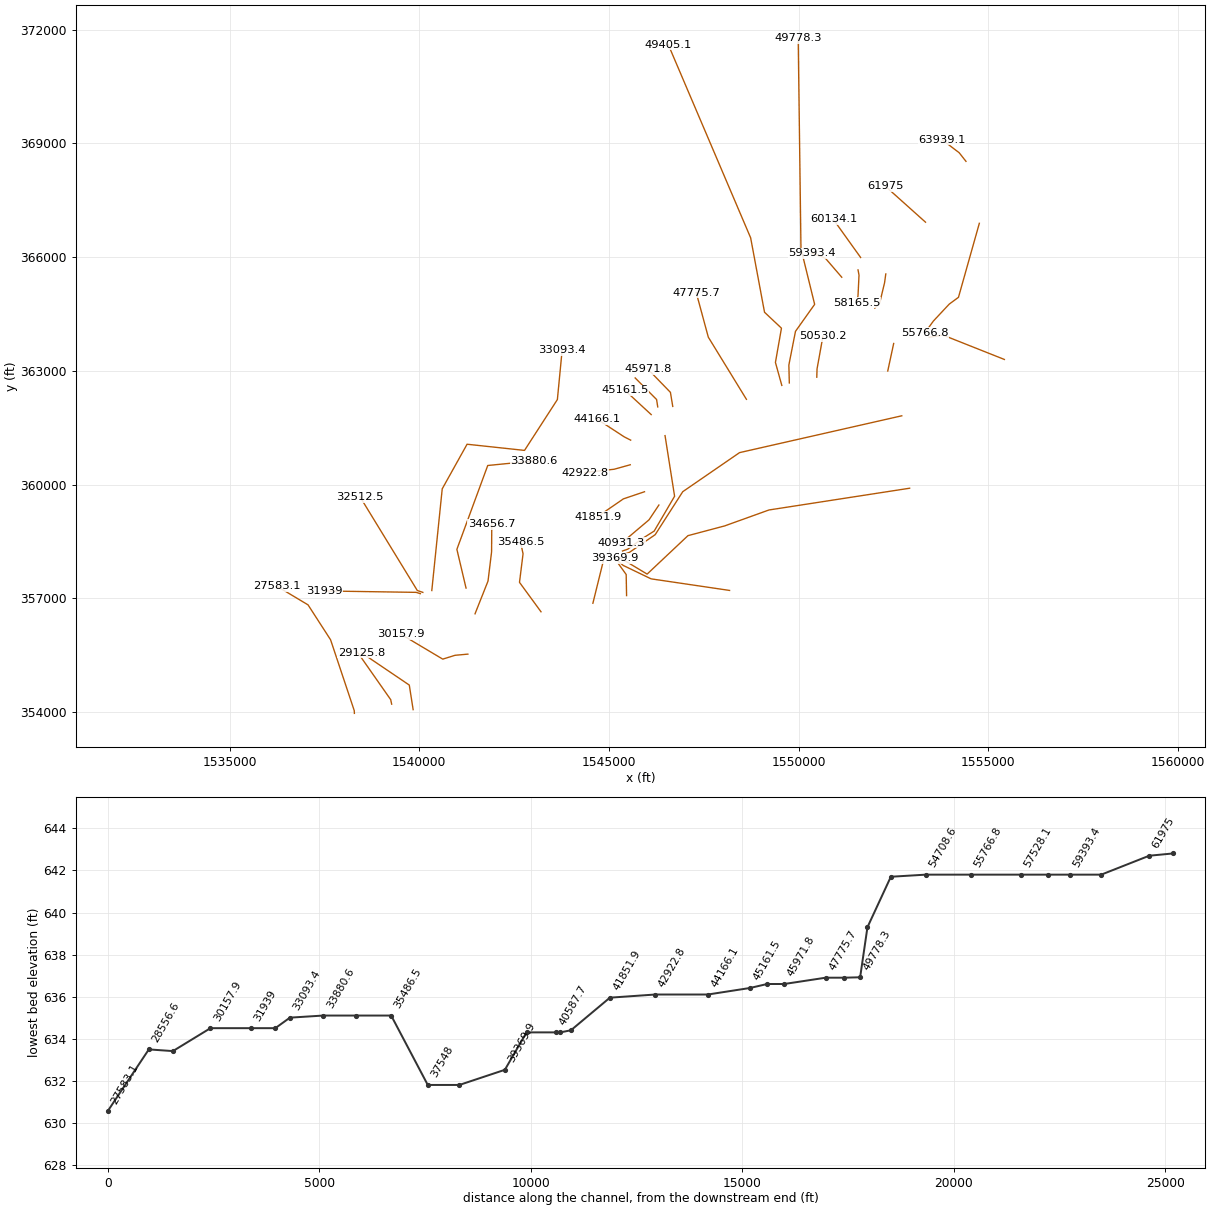
HEC-RAS study MDISLCRK1.prj: MDISLCRK1

--- MDISLCRK1.g02 (geometry) --- (continued)

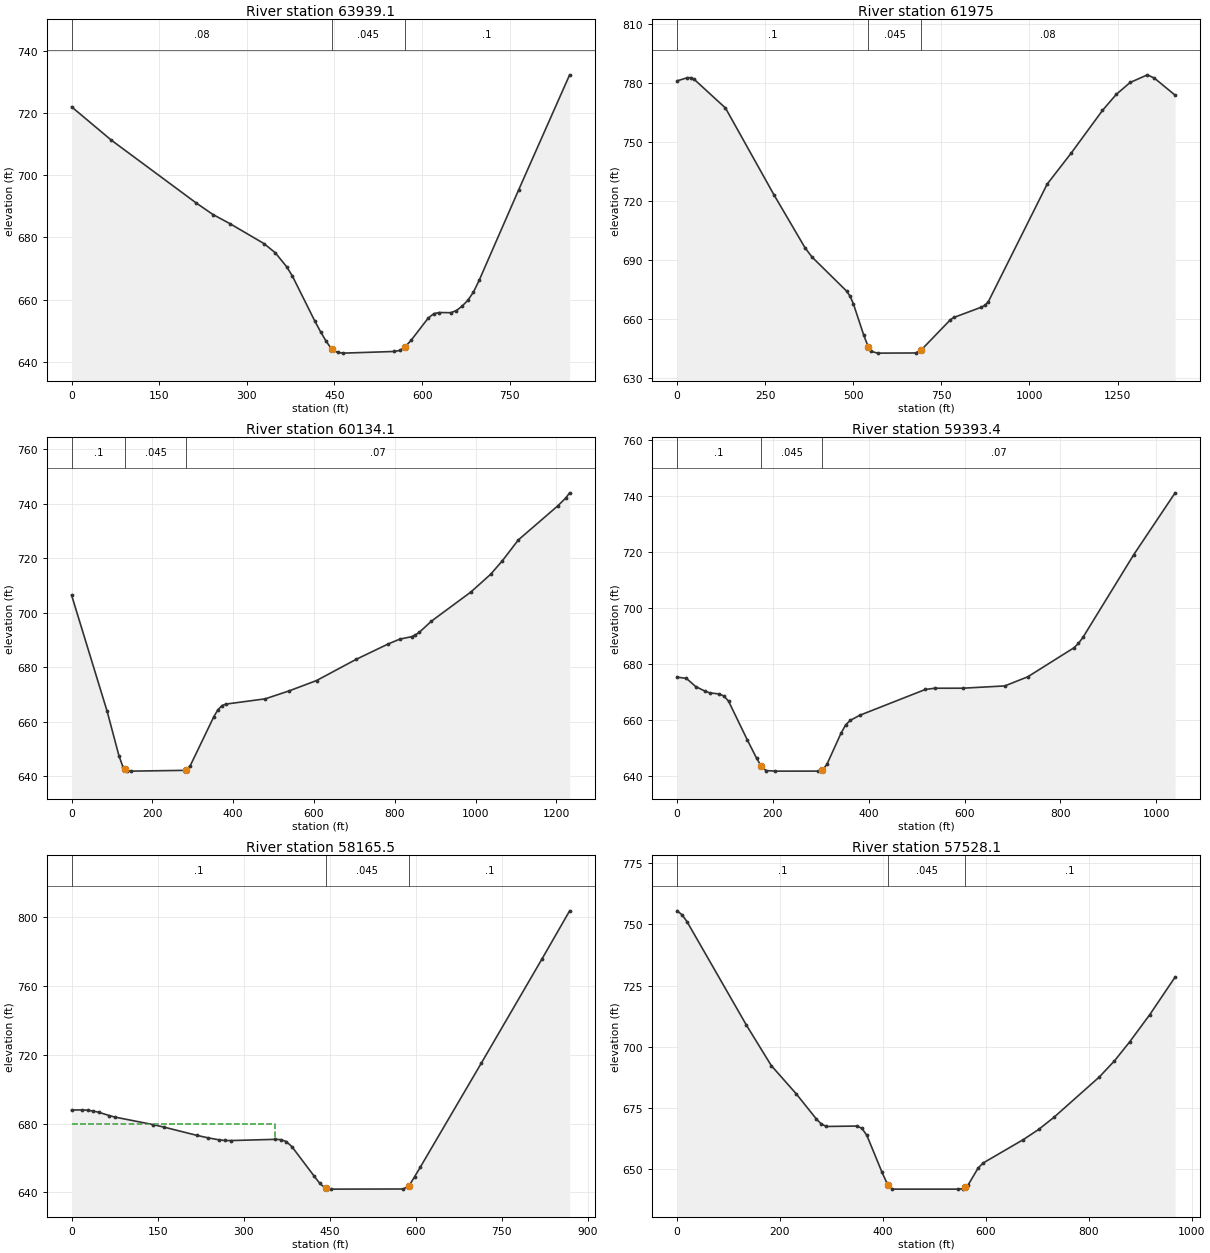
Type RM Length L Ch R = 1 ,63939.1 ,573.5,571.8,570.2
XS GIS Cut Line= 3
     1554416.279      368525.667     1554236.158      368753.532
     1553789.109      369094.243
#Sta/Elev= 30
       0  721.99    67.8  711.31     213  691.12     242  687.37   271.1  684.43
   329.2  678.04   348.6  675.09     368  670.62   377.7  667.68   416.4  653.11
   426.1  649.71   435.8  646.61   445.5  644.03   455.2  643.04   464.9  642.81
   552.1  643.34   561.8  643.68   570.3  644.71   581.2  646.95   610.3  654.04
     620  655.51   629.6  655.86     649  655.81   658.7  656.49   668.4  657.92
   678.1  659.75   687.8   662.4   697.5  666.16   765.3  695.31   852.5  732.27
#Mann= 3 , 0 , 0
       0     .08       0   445.5    .045       0   570.3      .1       0
Bank Sta=445.5,570.3
XS Rating Curve= 0 ,0
Exp/Cntr=0.3,0.1

Type RM Length L Ch R = 1 ,61975   ,1140.5,1134.9,1129.1
XS GIS Cut Line= 2
     1553349.164       366921.65     1552296.321      367864.572
#Sta/Elev= 30
       0  781.12    29.4  782.74    39.3  782.74    49.1  781.82   137.4  767.32
   274.8  723.26   363.2  696.25   382.8  691.59   480.9  674.29   490.8   671.7
   500.6  667.65     530  651.72   542.6  645.93   549.6  643.64   569.3   642.7
   677.2  642.78   692.6  644.24   775.4  659.63   785.2  660.82   863.7  666.07
   873.5  667.01   883.4  668.87  1050.2  728.62  1118.9   744.5  1207.2  766.09
  1246.5  774.27  1285.8   780.3  1334.8  784.19  1354.5  782.53  1413.4  773.84
#Mann= 3 , 0 , 0
       0      .1       0   542.6    .045       0   692.6     .08       0
Bank Sta=542.6,692.6
XS Rating Curve= 0 ,0
Exp/Cntr=0.3,0.1

Type RM Length L Ch R = 1 ,60134.1 ,738.7,740.7,742.7
XS GIS Cut Line= 2
     1551638.176      365990.728     1550920.453      366993.044
#Sta/Elev= 30
       0  706.42    88.1  663.73   117.4  647.39   127.2  643.33   132.6  642.54
     137   641.9   146.8   641.8   282.6  642.09   293.5  643.72   352.2  661.81
     362  664.27   371.8   665.8   381.6   666.4   479.4  668.34   538.1  671.24
   606.6  675.07   704.4  682.84   782.7  688.41   812.1  690.25   841.4  691.15
   851.2  691.82     861  692.79   890.4  696.83   988.2  707.54  1037.1  714.04
  1066.5  719.07  1105.6  726.65  1203.4  739.18    1223  742.04  1232.8  743.97
#Mann= 3 , 0 , 0
       0      .1       0   132.6    .045       0   282.6     .07       0
Bank Sta=132.6,282.6
XS Rating Curve= 0 ,0
Exp/Cntr=0.3,0.1

Type RM Length L Ch R = 1 ,59393.4 ,479.6,516.2,552.7
XS GIS Cut Line= 3
     1551140.547      365470.207      1550706.52      365973.679
     1550354.957      366103.888
#Sta/Elev= 30
       0  675.32    19.6  674.84    39.1  671.91    58.6   670.3    68.4   669.7
      88   669.3    97.8  668.59   107.5  666.73   146.6  652.94   166.2  646.35
     176  643.52   185.7     642   205.3   641.8   293.3  641.81     303  642.07
   312.8  644.23   342.1  655.26   351.9   658.3   361.7  659.91   381.2   661.7
   518.1   670.9   537.6  671.35   596.3  671.36     684  672.17     732  675.42
   828.2  685.74   837.8  687.31   847.4  689.53   953.1  718.92  1039.6     741
#Mann= 3 , 0 , 0
       0      .1       0     176    .045       0     303     .07       0
Bank Sta=176,303
XS Rating Curve= 0 ,0
Exp/Cntr=0.3,0.1

Type RM Length L Ch R = 1 ,58165.5 ,641.6,637.3,633.1
XS GIS Cut Line= 4
       1551569.6      365663.905     1551595.641      365525.016
       1551569.6      364991.162     1551543.558       364800.19
#Sta/Elev= 30
       0  687.87    18.8  687.92    28.3  687.72    37.7  687.26    47.1   686.6
    65.9  684.62    75.4  683.76   141.3  679.43   160.8  677.94     219  673.07
   238.5  671.64   257.9  670.45   267.6  670.14   277.4  670.08   355.1  670.79
   364.8  670.62   374.5   669.5   384.3   666.5   423.1  649.33   432.8  645.16
   442.6  642.29   443.5  642.24   452.3   641.8   578.6  641.88   588.3   643.7
     598  648.92   607.8  654.42   714.4  715.13   820.4  775.91   868.5  803.86
#Mann= 3 , 0 , 0
       0      .1       0   443.5    .045       0   588.3      .1       0
#XS Ineff= 2 , 0
          354.11  679.45
Permanent Ineff=
       F       F
Bank Sta=443.5,588.3
XS Rating Curve= 0 ,0
Exp/Cntr=0.3,0.1

Type RM Length L Ch R = 1 ,57528.1 ,1194.5,1194.7,1194.8
XS GIS Cut Line= 4
     1552301.371      365556.266     1552270.121      365327.099
     1552141.648      364792.377     1552013.176       364656.96
#Sta/Elev= 30
       0  755.59     9.6  754.02    19.3  751.18   134.9  708.82   183.1  692.32
   231.3  680.85   270.6  670.51   280.4  668.43   290.2  667.42   349.1  667.59
     359   666.7   368.8  663.81   398.2  648.74     408   644.2   410.1  643.69
   417.9   641.8   545.5   641.8   555.4  641.97   560.1  642.64   565.2  643.36
   584.8  650.33   594.6  652.46   673.2  662.09   702.7  666.21   732.1  671.11
   820.5  687.64     850  694.24   879.5     702   918.8  713.19   967.9  728.53
#Mann= 3 , 0 , 0
       0      .1       0   410.1    .045       0   560.1      .1       0
Bank Sta=410.1,560.1
XS Rating Curve= 0 ,0
Exp/Cntr=0.3,0.1

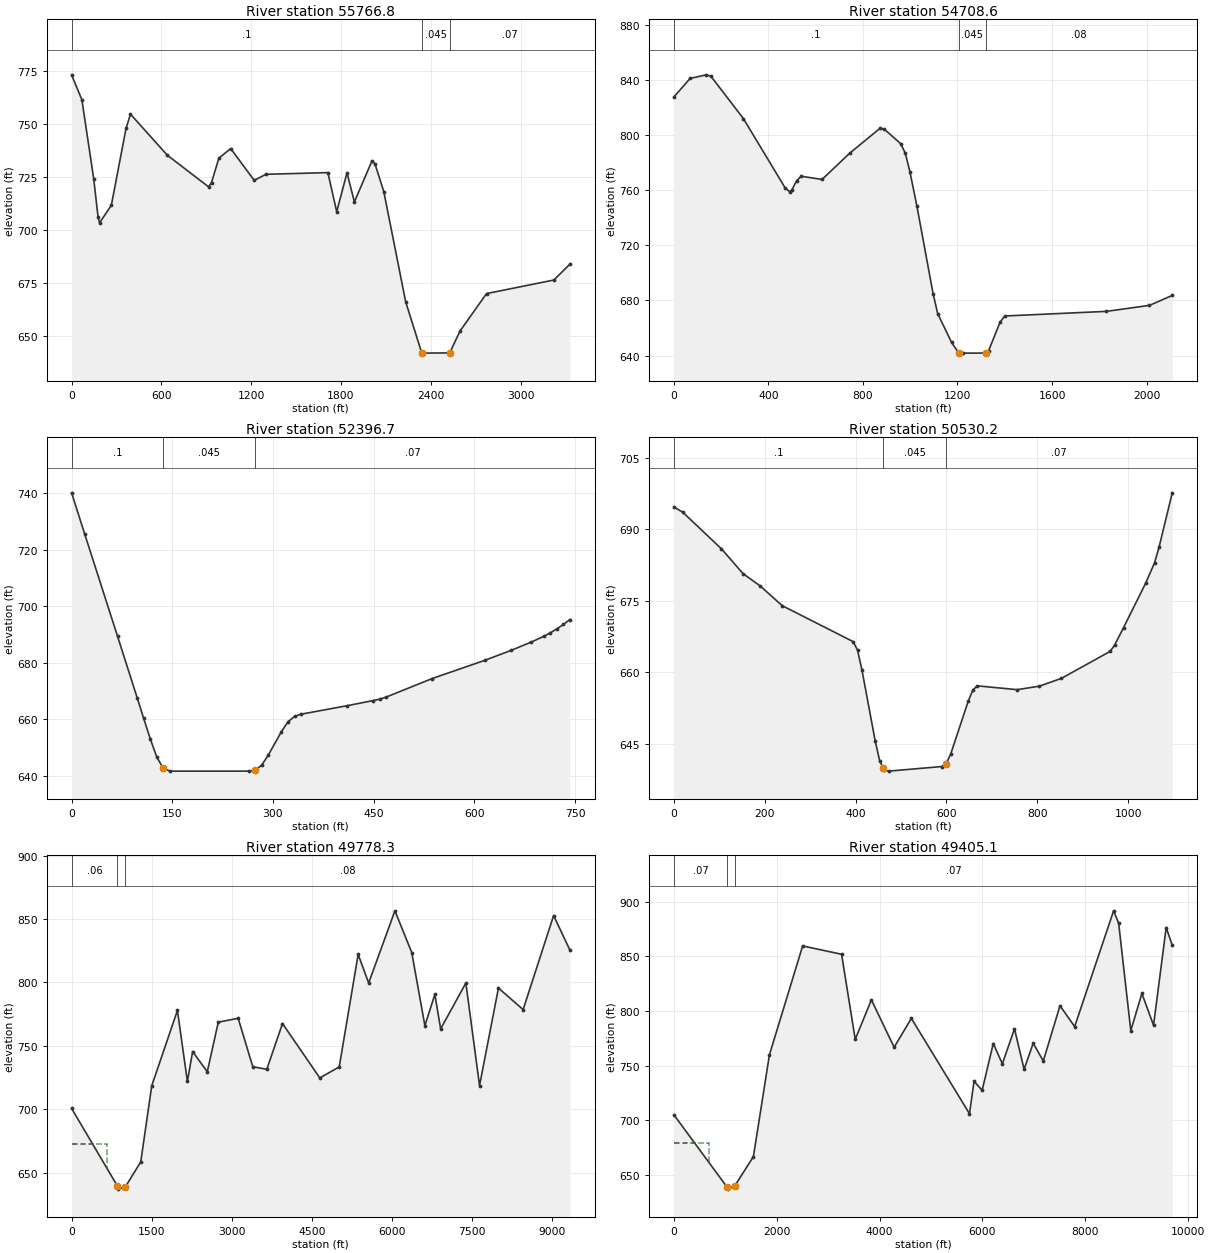
Type RM Length L Ch R = 1 ,55766.8 ,1085.2,1058.2,1031.2
XS GIS Cut Line= 5
     1554768.544       366892.35      1554218.47      364941.097
     1553974.982      364761.127     1553558.315      364316.683
     1553329.148       364000.71
#Sta/Elev= 30
       0  773.42    68.9  761.61   147.6  724.37   177.1  706.08     187  703.41
   265.7  711.74   364.1  748.14   393.6  754.83   639.7   735.4   915.2  720.46
   934.9  722.46   984.1  733.98  1062.9  738.56  1220.3  723.52    1299  726.38
  1712.4  727.17  1771.4  708.68  1840.3   727.1  1889.5   713.3  2007.6  732.82
  2027.3  731.27  2085.9  718.24  2232.4  666.04  2339.9  641.83  2349.7   641.8
  2526.6  641.92  2595.4  652.24  2772.3  669.95  3222.3  676.37  3329.6  683.87
#Mann= 3 , 0 , 0
       0      .1       0  2339.9    .045       0  2526.6     .07       0
Bank Sta=2339.9,2526.6
XS Rating Curve= 0 ,0
Exp/Cntr=0.3,0.1

Type RM Length L Ch R = 1 ,54708.6 ,840.5,825.2,809.8
XS GIS Cut Line= 3
     1555428.266      363302.072     1553808.315      363945.155
     1553447.204      363886.127
#Sta/Elev= 30
       0  827.77    68.5  841.16   137.1  843.78   156.7  842.71   293.8  812.05
     470  761.93   489.6  758.91   499.4  760.28     519   766.9   538.6  770.17
   626.7  767.85   744.2  786.96   871.5  804.84     891   804.2   959.6  793.82
   979.2   786.9   998.8  773.26  1028.1  748.63  1096.7  684.98  1116.3  670.43
    1175  649.54  1204.4  642.06    1224   641.8  1321.9  641.84  1331.7  643.59
  1380.6  664.41  1400.2  668.75  1829.6   672.1  2012.5  676.46  2108.8  683.67
#Mann= 3 , 0 , 0
       0      .1       0  1204.4    .045       0  1321.9     .08       0
Bank Sta=1204.4,1321.9
XS Rating Curve= 0 ,0
Exp/Cntr=0.3,0.1

Type RM Length L Ch R = 1 ,52396.7 ,553.1,552.9,552.5
XS GIS Cut Line= 2
     1552353.454      362997.238     1552509.704      363722.933
#Sta/Elev= 30
       0  740.09    19.5  725.55    68.4  689.41    97.7  667.64   107.4  660.33
   117.2  653.11     127  646.62   136.7  642.68   146.5   641.7   263.7   641.7
   273.5  642.02   283.3  643.86   292.9  647.33   312.6  655.66   322.3  659.11
   332.1  661.04   341.9  661.83   410.2  664.82   449.3  666.65   459.1  667.14
   468.8   667.9   537.2  674.44   615.4  680.86   654.4  684.36   683.7  687.22
   703.3  689.33     713  690.57   722.8  691.98   732.6  693.55   742.3   695.3
#Mann= 3 , 0 , 0
       0      .1       0   136.7    .045       0   273.5     .07       0
Bank Sta=136.7,273.5
XS Rating Curve= 0 ,0
Exp/Cntr=0.3,0.1

Type RM Length L Ch R = 1 ,50530.2 ,173.1,172.9,172.7
XS GIS Cut Line= 3
     1550481.926      362834.044     1550488.871      363052.794
     1550645.121      363917.377
#Sta/Elev= 30
       0  694.68      19  693.65   104.7  685.93   152.2  680.73   190.3  678.12
   238.4  674.01   394.6  666.47   404.3  664.69   414.1  660.49   443.4  645.55
   453.2  641.43   460.8     640   462.9   639.6   472.7   639.3   589.8  640.26
   599.6  640.88   609.3  642.82   648.4  654.06   658.2  656.29   667.9  657.19
   755.8  656.39   804.6  657.12   853.4  658.76   960.8  664.43   970.5  665.76
   990.1  669.39  1038.9  678.74  1058.4     683  1068.2  686.23  1097.4  697.68
#Mann= 3 , 0 , 0
       0      .1       0   460.8    .045       0   599.6     .07       0
Bank Sta=460.8,599.6
XS Rating Curve= 0 ,0
Exp/Cntr=0.3,0.1

Type RM Length L Ch R = 1 ,49778.3 ,373,373.2,373.7
XS GIS Cut Line= 6
     1549757.621        362682.8     1549745.815      363155.224
     1549920.294      364043.245     1550425.688      364754.843
     1550065.185      366222.198     1549991.959       371769.74
#Sta/Elev= 30
       0  700.62   854.5   639.6     872  636.92  1004.5  638.56  1294.9  658.44
  1501.2  718.52  1981.7  777.89    2168  721.87  2266.1  745.46  2540.4  729.51
  2746.2  768.62  3118.4  771.69    3392  733.49  3654.6  731.45  3948.3  767.54
  4646.7  724.65  5010.7  733.35  5364.8   822.1  5561.6  799.53  6053.4  856.47
  6368.2  823.58  6614.1  765.86    6801  790.57  6909.2  763.33  7381.4  799.51
  7637.2  718.63  7991.3  795.51  8453.6  778.58  9024.2  852.74  9329.1   825.5
#Mann= 3 , 0 , 0
       0     .06       0   854.5    .045       0  1004.5     .08       0
#XS Ineff= 2 , 0
          665.48  672.91
Permanent Ineff=
       F       F
Bank Sta=854.5,1004.5
XS Rating Curve= 0 ,0
Exp/Cntr=0.3,0.1

Type RM Length L Ch R = 1 ,49405.1 ,432,440.3,448.2
XS GIS Cut Line= 6
     1549559.704      362617.695     1549391.648      363222.933
     1549550.502      364126.578     1549103.929      364546.874
     1548738.262      366508.635      1546567.48       371600.47
#Sta/Elev= 30
       0  704.95  1028.3  639.06  1047.8   636.9  1185.5  640.01  1545.6  666.71
  1857.1  759.94    2503  859.66  3259.9  852.04  3525.3  774.12  3839.9  810.27
  4282.2  766.81  4616.5  793.32  5747.2  705.95  5835.7  735.73    5993  727.42
  6209.3  770.29  6386.2  751.71  6622.2  783.74    6809  746.63    6986  770.53
  7182.6  754.31    7507   804.9  7792.2  785.79  8549.2  891.82  8647.5  880.44
  8883.5  782.13  9099.8   816.1  9325.9  786.96  9571.7  876.54  9689.7  860.26
#Mann= 3 , 0 , 0
       0     .07       0  1028.3    .045       0  1185.5     .07       0
#XS Ineff= 2 , 0
          681.85  679.05
Permanent Ineff=
       F       F
Bank Sta=1028.3,1185.5
XS Rating Curve= 0 ,0
Exp/Cntr=0.3,0.1

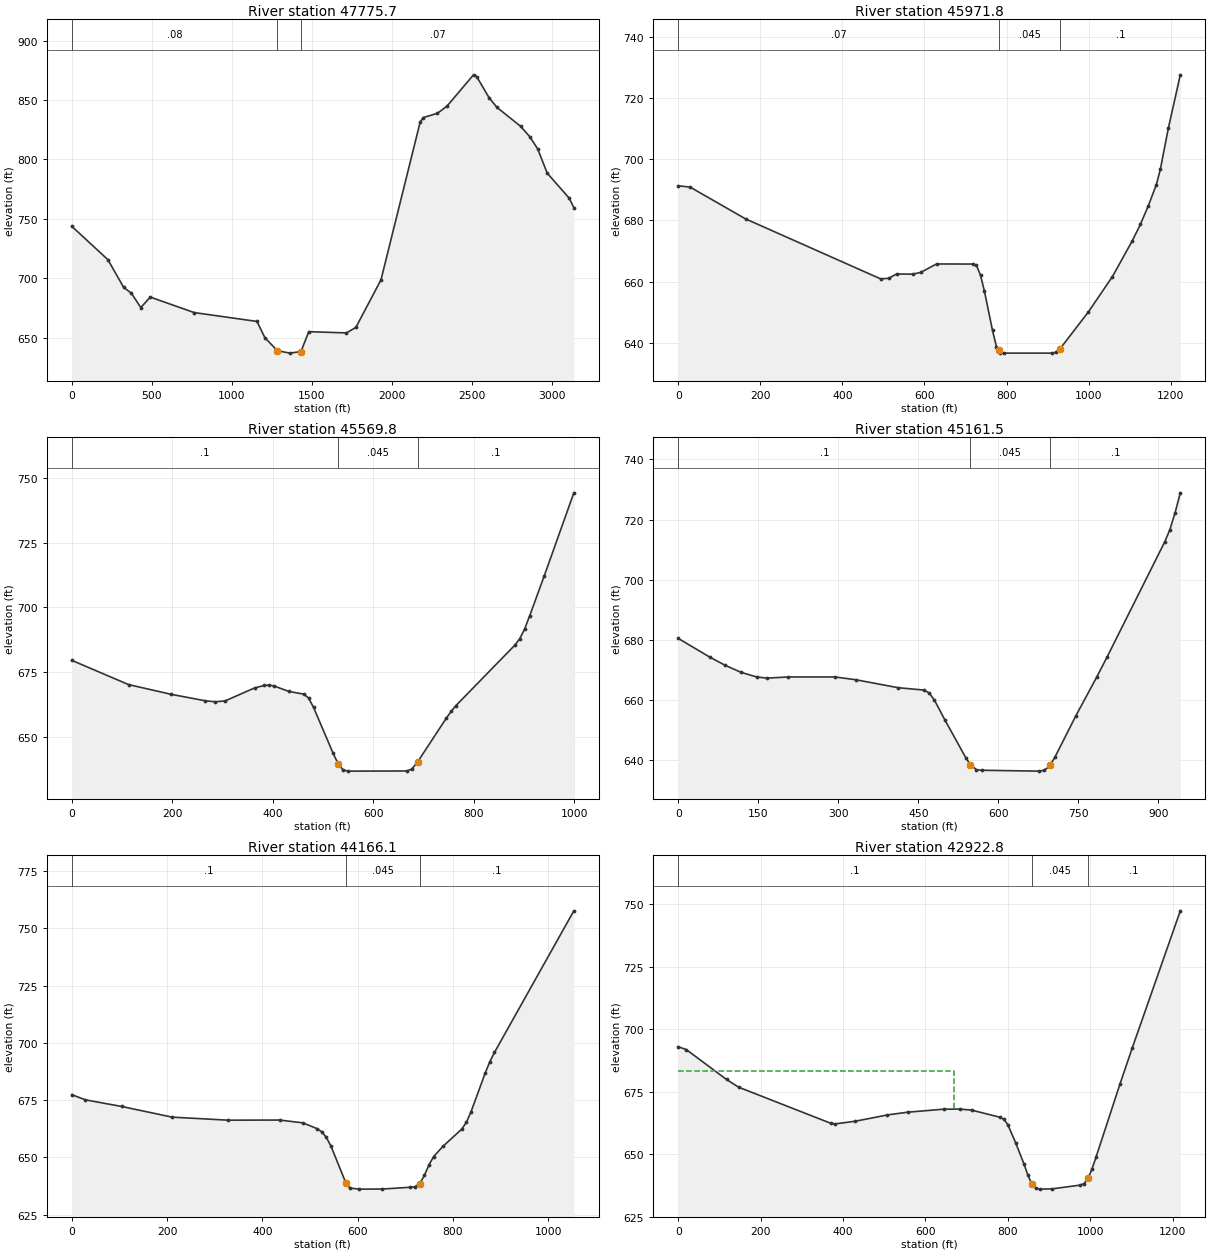
Type RM Length L Ch R = 1 ,47775.7 ,977.2,981.4,985.7
XS GIS Cut Line= 3
     1548626.544      362251.087     1547621.264      363890.619
     1547303.627      365063.587
#Sta/Elev= 30
       0  743.74   225.7  715.62   323.8  692.41   372.9  687.29   431.7  675.29
   490.6   684.1   765.4  671.05  1157.8  663.59  1206.9  649.93  1285.4  638.93
  1363.9   636.9  1432.6  638.25  1481.6  654.96  1717.1  653.93    1776  658.59
    1933  698.69    2178  831.64  2197.6  835.28  2285.8   838.9  2344.6  844.78
  2511.2  871.28  2530.8  869.84  2609.2  851.86  2658.2  843.79  2805.2  827.99
    2864  819.01    2913  808.75  2971.8  788.51    3109  767.48  3138.4  759.44
#Mann= 3 , 0 , 0
       0     .08       0  1285.4    .045       0  1432.6     .07       0
Bank Sta=1285.4,1432.6
XS Rating Curve= 0 ,0
Exp/Cntr=0.3,0.1

Type RM Length L Ch R = 1 ,45971.8 ,401.8,402,402.2
XS GIS Cut Line= 3
     1546683.836      362063.587     1546622.551      362434.738
     1546032.273      363042.377
#Sta/Elev= 30
       0   691.3    28.9  690.88     164  680.49     493  660.88   512.5  661.06
     532  662.46   570.9  662.43   590.4  662.96   629.4  665.75     717  665.72
   726.7  665.25   736.5  662.05   746.2  656.75   765.7  644.02   775.4   638.7
   780.8  637.61   785.1  636.75   794.9   636.6   911.7   636.6   921.5  636.95
   930.8   638.1   999.4  650.09  1057.8   661.6  1106.5  673.37    1126  678.67
  1145.4  684.79  1164.9  691.67  1174.6  696.65  1194.1  710.09  1223.3  727.58
#Mann= 3 , 0 , 0
       0     .07       0   780.8    .045       0   930.8      .1       0
Bank Sta=780.8,930.8
XS Rating Curve= 0 ,0
Exp/Cntr=0.3,0.1

Type RM Length L Ch R = 1 ,45569.8 ,407.4,408.3,409.3
XS GIS Cut Line= 3
     1546288.117      362050.068     1546257.735      362245.381
     1545693.499      362813.957
#Sta/Elev= 30
       0  679.52     113  670.12   197.7  666.36     266  663.83   285.6  663.47
   305.1   663.8   363.7  668.84   383.3  669.79     393  669.89   402.8  669.55
   432.1  667.46   461.4  666.42   471.2   664.9     481  661.25     520  643.45
   529.8  639.47   539.6  637.08   549.3   636.6   666.6  636.66   676.3  637.39
   688.4   640.3   744.7  657.02   754.5   659.7   764.2  661.99   881.5  685.43
   891.2  687.95     901  691.76   910.8  696.75   940.1  712.38   998.7  744.41
#Mann= 3 , 0 , 0
       0      .1       0   529.8    .045       0   688.4      .1       0
Bank Sta=529.8,688.4
XS Rating Curve= 0 ,0
Exp/Cntr=0.3,0.1

Type RM Length L Ch R = 1 ,45161.5 ,991.6,995.4,999.1
XS GIS Cut Line= 2
     1546115.607      361847.933     1545424.634      362486.822
#Sta/Elev= 30
       0  680.52    58.8  674.33    88.2  671.56   117.6  669.26     147   667.7
   166.6  667.32   205.9   667.7   294.1   667.7   333.3  666.77   411.7  664.15
   460.7  663.34   470.5  662.36   480.3  659.98     500  653.37   539.2   640.8
   547.5  638.58   558.8  636.89   568.6   636.7   676.4  636.41   686.2  636.68
     696  638.11   697.5  638.55   705.8  640.96     745  654.69   784.2   667.6
   803.8  674.32   911.7  712.53   921.5  716.63   931.3  722.28   941.1   728.9
#Mann= 3 , 0 , 0
       0      .1       0   547.5    .045       0   697.5      .1       0
Bank Sta=547.5,697.5
XS Rating Curve= 0 ,0
Exp/Cntr=0.3,0.1

Type RM Length L Ch R = 1 ,44166.1 ,1227.7,1243.3,1258.8
XS GIS Cut Line= 3
      1545573.94      361174.322     1545403.801      361261.127
     1544681.579      361733.349
#Sta/Elev= 30
       0  677.37    28.6  675.11     105   672.2   210.6  667.55   328.3  666.22
   436.2  666.28   485.2  665.05   514.6  662.55   524.4   661.2   534.2  658.77
     544  654.92   573.4   639.8   576.5  638.79   583.2  636.61   602.8   636.1
   651.9  636.14   710.7  636.91   720.5  637.14   730.3  638.48   740.1  642.06
   749.9  646.75   759.7  650.35   779.4  654.84   818.6  662.32   828.4  665.33
   838.2  669.96   867.6  686.67   877.4  691.68   887.2   695.8  1053.9  757.68
#Mann= 3 , 0 , 0
       0      .1       0   576.5    .045       0   730.3      .1       0
Bank Sta=576.5,730.3
XS Rating Curve= 0 ,0
Exp/Cntr=0.3,0.1

Type RM Length L Ch R = 1 ,42922.8 ,1059.8,1070.9,1081.9
XS GIS Cut Line= 3
     1545563.523      360525.016     1545139.912       360406.96
     1544365.607      360320.155
#Sta/Elev= 30
       0  693.01    19.5  691.89   117.3  679.93   146.6  676.86   371.4  662.35
   381.1  662.18     430  663.25   507.9  665.76   556.6  666.85   644.3  668.06
   683.2   668.1   712.5  667.68   780.6  664.85   790.4  664.04   800.1  661.88
   819.6  654.45   839.1  646.27   848.7  641.82   858.6  638.05   868.3  636.37
     878   636.1   907.2   636.2   975.4   637.7   985.2  638.32   994.9  640.38
  1004.6   644.2  1014.4  648.95  1072.8   678.3    1102  692.43  1218.9  747.36
#Mann= 3 , 0 , 0
       0      .1       0   858.6    .045       0   994.9      .1       0
#XS Ineff= 2 , 0
          669.23  683.43
Permanent Ineff=
       F       F
Bank Sta=858.6,994.9
XS Rating Curve= 0 ,0
Exp/Cntr=0.3,0.1

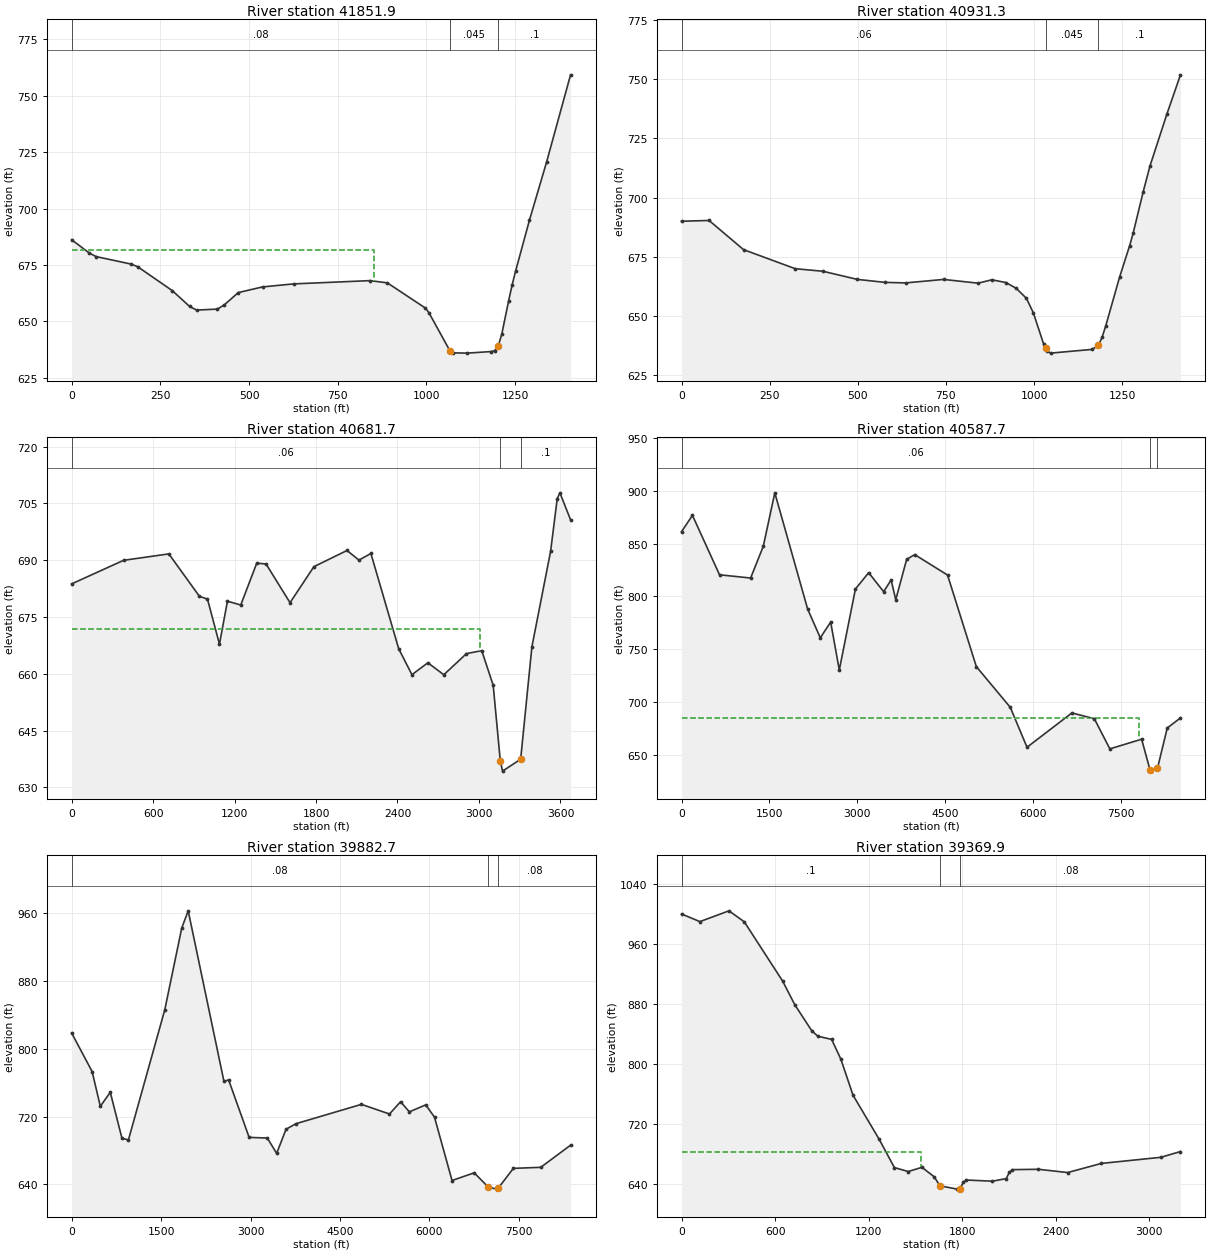
Type RM Length L Ch R = 1 ,41851.9 ,918.2,920.6,922.7
XS GIS Cut Line= 4
     1545939.044      359813.587     1545382.968       359625.71
     1544827.412      359243.766     1544719.773      359146.544
#Sta/Elev= 30
       0  686.22    48.9  680.42    68.5  678.77   166.3  675.47   185.9  674.29
   283.7  663.65   332.6  656.64   352.2  655.03   410.9  655.47   430.4  657.34
   469.6  662.78     538   665.3     626  666.64     841  668.09   889.8   667.1
   997.3   655.9  1007.1  653.85  1065.7   637.1  1075.5  636.07  1114.6  635.95
    1183  636.65  1192.8  637.06  1202.5  639.25  1212.3  644.33  1231.8  659.25
  1241.6  666.23  1251.4  672.39  1290.2  694.81  1338.5  720.58  1406.2  759.32
#Mann= 3 , 0 , 0
       0     .08       0  1065.7    .045       0  1202.5      .1       0
#XS Ineff= 2 , 0
          852.75  681.88
Permanent Ineff=
       F       F
Bank Sta=1065.7,1202.5
XS Rating Curve= 0 ,0
Exp/Cntr=0.3,0.1

Type RM Length L Ch R = 1 ,40931.3 ,251.2,249.6,248.1
XS GIS Cut Line= 4
     1546318.499      359463.263     1546058.082      359072.638
     1545467.804      358573.506     1545327.882      358472.151
#Sta/Elev= 30
       0  690.06    78.2  690.38     176  678.06   322.8  670.02     401  668.95
   498.8  665.51   577.1  664.26   635.8  664.03   743.4   665.5   841.3  663.92
   880.4  665.35   919.6   664.2   948.9  661.81   978.3  657.54   997.9  651.42
  1027.2  638.23  1032.7  636.57    1037  635.27  1046.8   634.4  1164.2  635.97
  1182.7  637.64  1193.6  641.35  1203.4  645.93  1242.5  666.42  1271.3  679.81
  1280.9  684.89  1309.7  702.57  1328.9  713.41  1376.9  735.33  1415.3  751.84
#Mann= 3 , 0 , 0
       0     .06       0  1032.7    .045       0  1182.7      .1       0
Bank Sta=1032.7,1182.7
XS Rating Curve= 0 ,0
Exp/Cntr=0.3,0.1

Type RM Length L Ch R = 1 ,40681.7 ,94.1,94.1,94.1
XS GIS Cut Line= 6
     1546480.711      361293.069     1546732.473      359694.337
     1546194.568      358776.624     1545862.134      358566.683
     1545497.551      358299.322     1545358.662       358250.71
#Sta/Elev= 30
       0  683.75   382.5  689.98     716  691.68   941.6  680.46  1000.5  679.75
  1088.8  667.84  1147.6  679.19  1245.7  678.18  1363.4  689.23  1432.1  689.01
  1608.6  678.79  1784.3   688.3  2028.3  692.58  2116.2  690.04    2204  691.79
  2408.9  666.62  2506.5  659.77  2623.6  662.92  2741.1  659.76    2908  665.34
  3020.5  666.12  3104.8  656.97    3157  637.05  3173.6   634.3    3307  637.44
  3389.9  667.14  3527.5  692.34  3576.5  706.31  3596.1  707.81  3674.6  700.69
#Mann= 3 , 0 , 0
       0     .06       0    3157    .045       0    3307      .1       0
#XS Ineff= 2 , 0
         3007.33  671.77
Permanent Ineff=
       F       F
Bank Sta=3157,3307
XS Rating Curve= 0 ,0
Exp/Cntr=0.3,0.1

Type RM Length L Ch R = 1 ,40587.7 ,702.2,704.9,707.7
XS GIS Cut Line= 6
     1552722.717      361816.181     1548445.649      360845.145
     1546947.181      359814.448     1546220.668      358681.391
      1545542.69      358215.988     1545403.801      358167.377
#Sta/Elev= 30
       0  861.44   186.8  876.91     649  820.54  1180.1  817.47  1396.4  847.56
  1593.1  898.29  2153.6   788.1    2370  760.74    2547  775.71  2694.5  730.23
  2969.8  807.07    3196  822.56  3451.7  804.49  3579.5  815.67  3658.2   796.9
    3845  835.24  3982.7  839.66  4543.2  820.28  5034.8  733.44  5614.8  694.78
  5899.9  656.94  6666.4  689.51  7049.6  684.02  7314.8  655.41  7857.3  664.58
    8000  635.57  8019.6   634.3  8127.7  636.88  8294.8  675.19  8520.6  684.78
#Mann= 3 , 0 , 0
       0     .06       0    8000    .045       0  8127.7     .09       0
#XS Ineff= 2 , 0
         7820.51  684.53
Permanent Ineff=
       F       F
Bank Sta=8000,8127.7
XS Rating Curve= 0 ,0
Exp/Cntr=0.3,0.1

Type RM Length L Ch R = 1 ,39882.7 ,533.2,512.8,492.4
XS GIS Cut Line= 6
     1552931.051      359906.459     1549222.241      359332.907
        1548052.      358912.306     1547084.877        358655.6
     1546008.489      357641.712       1545244.6      358100.045
#Sta/Elev= 30
       0  818.77   343.8  773.19   481.4  732.12   648.4  748.63   844.9  694.16
     953  692.52  1562.1  846.06    1847  942.73    1955     963  2554.3  761.59
  2632.9   763.3  2976.8  695.41  3281.3  694.64  3438.5  676.55  3595.7  705.04
  3762.7   711.6  4859.4  734.42    5330  723.05  5516.4  737.52  5663.5  725.57
  5938.2  733.83  6085.2  719.26    6379  644.48  6751.1  653.58  6986.5   636.7
    7133   634.3  7152.6  635.35  7407.2  658.83  7867.3  660.06  8366.6  686.22
#Mann= 3 , 0 , 0
       0     .08       0  6986.5    .045       0  7152.6     .08       0
Bank Sta=6986.5,7152.6
XS Rating Curve= 0 ,0
Exp/Cntr=0.3,0.1

Type RM Length L Ch R = 1 ,39369.9 ,1107,1075.1,1043.1
XS GIS Cut Line= 4
       1548182.1      357211.156     1546112.655      357516.712
     1545376.544      357870.878     1545154.322      358058.378
#Sta/Elev= 30
       0 1000.45   117.8  990.18   304.4  1004.6   402.7  989.86   648.2  910.75
   726.8   878.9   834.8  844.37   874.1  836.96   962.5   832.7  1021.4   806.5
    1100  757.98  1266.9  699.37  1365.1   661.3  1453.5  656.07  1541.9  661.67
  1620.5  648.95  1656.9  636.98  1767.8  632.52  1787.4  633.26  1806.9  641.81
  1826.7  644.69  1993.7  643.15  2082.1  646.61  2101.7  654.77  2121.4  658.57
  2288.7  659.05  2475.7  654.68  2692.2  666.88  3073.5  675.04  3199.5  682.78
#Mann= 3 , 0 , 0
       0      .1       0  1656.9    .045       0  1787.4     .08       0
#XS Ineff= 2 , 0
         1538.46  682.67
Permanent Ineff=
       F       F
Bank Sta=1656.9,1787.4
XS Rating Curve= 0 ,0
Exp/Cntr=0.3,0.1

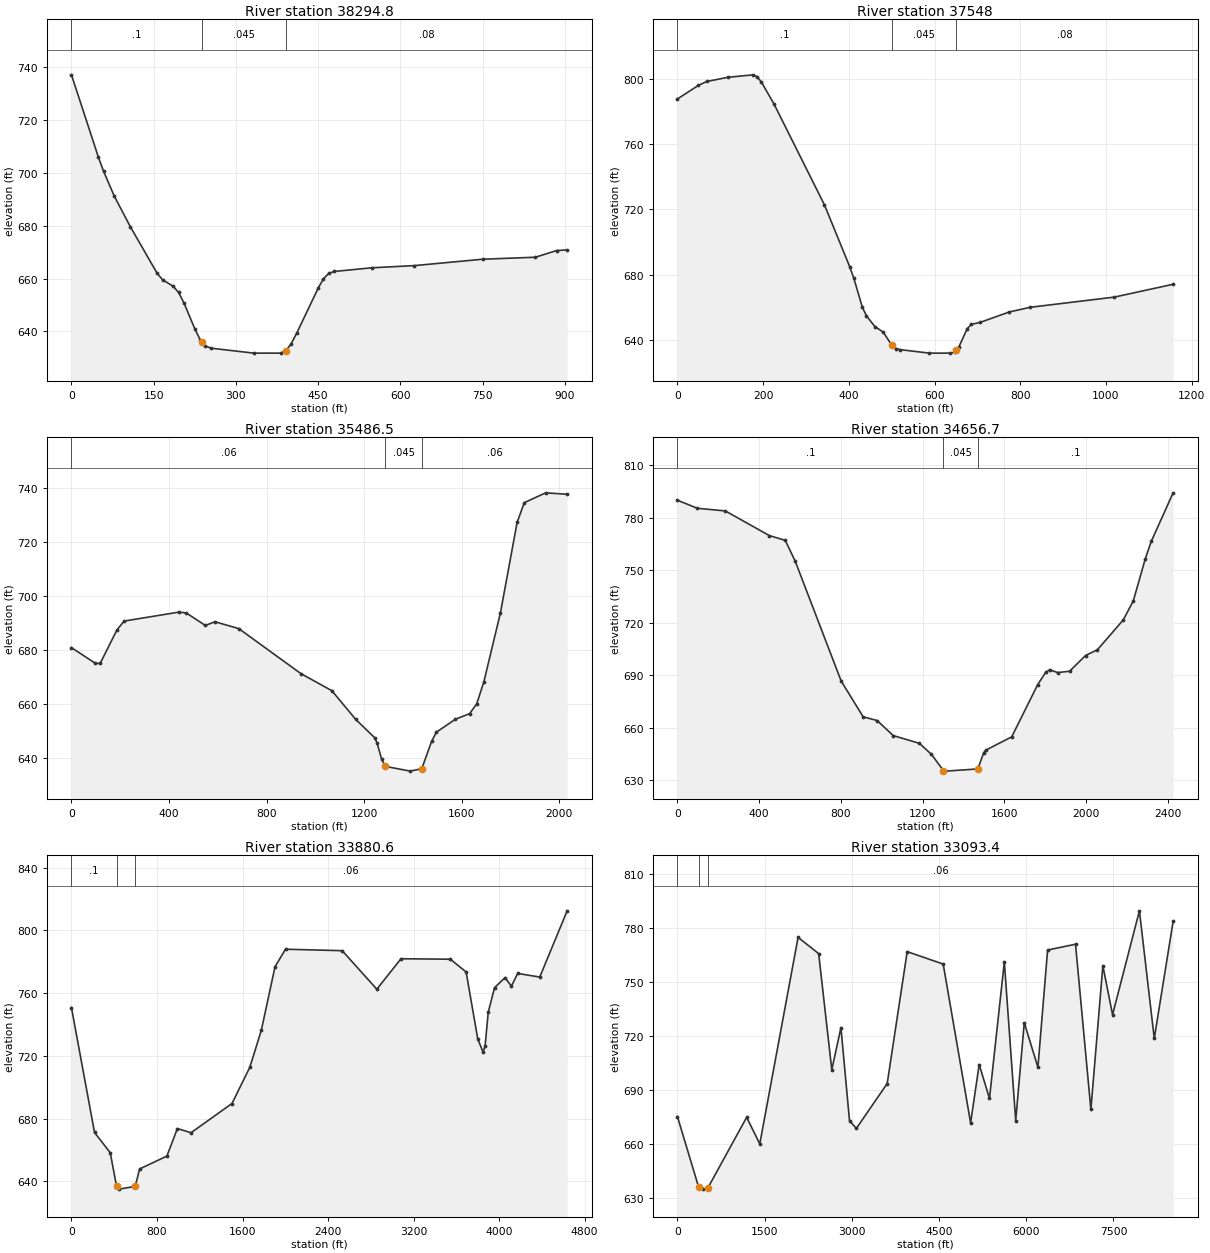
Type RM Length L Ch R = 1 ,38294.8 ,752.6,746.8,740.9
XS GIS Cut Line= 3
     1545466.337      357074.582     1545455.921      357631.874
     1545252.796      357913.124
#Sta/Elev= 30
       0   737.1    48.9   706.1    58.7  700.54    78.2  691.17   107.6  679.56
   156.5  661.94   166.2  659.57   185.8  657.06   195.6  654.74   205.4  650.71
   224.9  641.07   234.7   636.9     239  635.86   244.5  634.53   254.2  633.68
   332.5   631.8   381.4   631.8   391.2  632.67   400.9  635.35   410.7  639.25
   449.8  656.26   459.6  659.91   469.4  661.97   479.2  662.69   547.6  664.09
   624.8   664.9   750.1  667.33   846.5  668.09     885  670.61   904.3  670.86
#Mann= 3 , 0 , 0
       0      .1       0     239    .045       0   391.2     .08       0
Bank Sta=239,391.2
XS Rating Curve= 0 ,0
Exp/Cntr=0.3,0.1

Type RM Length L Ch R = 1 ,37548   ,864.3,865.1,865.8
XS GIS Cut Line= 2
     1544577.933      356872.614      1544855.19      357995.502
#Sta/Elev= 30
       0  787.88      49  796.24    68.6  798.62   117.6  801.16   176.4   802.7
   186.2  801.47     196  798.24   225.4  784.77   343.1   722.8   401.9  684.94
   411.7  677.72   431.3  660.11   441.1  654.66   460.7  648.14   480.3  644.68
   500.3  636.63   509.7  634.61   519.5  633.94   588.1   631.8   637.1  631.81
   646.9  632.38   650.3   633.5   656.7  635.61   676.3  646.86   686.1   649.5
   705.7  650.61   774.3  657.07   823.4  659.96  1019.4   666.2  1156.6  674.08
#Mann= 3 , 0 , 0
       0      .1       0   500.3    .045       0   650.3     .08       0
Bank Sta=500.3,650.3
XS Rating Curve= 0 ,0
Exp/Cntr=0.3,0.1

Type RM Length L Ch R = 1 ,35486.5 ,829.8,829.8,829.9
XS GIS Cut Line= 4
     1543209.992      356648.158      1542642.69      357423.974
      1542736.44      358177.447     1542670.468      358483.002
#Sta/Elev= 30
       0  680.87    98.1  675.07   117.7  675.01   186.3  687.39   215.8  690.72
   441.3  694.05   470.8  693.74   549.2   689.1   588.4  690.47   686.5  687.92
   941.5  671.22  1068.2   664.9  1165.5  654.31  1243.4   647.5  1253.1  645.63
  1272.6  639.43  1286.9  636.88  1389.4   635.1  1436.9     636    1477   646.1
  1496.5  649.52  1574.4  654.32  1632.8   656.4    1662  660.01  1691.2  668.12
  1759.5   693.8  1827.8  727.28  1857.2  734.61  1945.1  738.26    2033  737.73
#Mann= 3 , 0 , 0
       0     .06       0  1286.9    .045       0  1436.9     .06       0
Bank Sta=1286.9,1436.9
XS Rating Curve= 0 ,0
Exp/Cntr=0.3,0.1

Type RM Length L Ch R = 1 ,34656.7 ,768.1,776.1,784.1
XS GIS Cut Line= 4
      1541470.22      356595.526     1541812.829      357458.697
     1541906.579       358229.53     1541911.954       358950.73
#Sta/Elev= 30
       0  790.12    97.8   785.5   234.6  783.99   449.7   769.9   527.9  767.14
   576.8  755.16   801.6  686.63   909.1  666.19   977.8  664.04  1056.5  655.44
  1184.2  651.01  1243.2  644.74  1302.2  635.41    1312   635.1  1470.6  636.35
  1498.8   645.5  1508.6  647.05  1636.4  654.72  1763.7  684.64  1802.6   691.6
  1822.2  693.14  1861.1   691.5  1919.6  692.24  1997.6  701.24  2056.1  704.57
  2182.8  721.68  2231.5   732.5    2290  756.51  2319.2   766.5  2426.4  794.35
#Mann= 3 , 0 , 0
       0      .1       0  1302.2    .045       0  1470.6      .1       0
Bank Sta=1302.2,1470.6
XS Rating Curve= 0 ,0
Exp/Cntr=0.3,0.1

Type RM Length L Ch R = 1 ,33880.6 ,787.7,787.2,786.6
XS GIS Cut Line= 4
     1541232.968      357272.933     1540991.458      358294.396
     1541805.261      360505.667     1543029.219      360627.195
#Sta/Elev= 30
       0  750.74   215.8   671.2     363  658.27   421.8  636.88   441.4   635.1
   596.1   636.8   637.6  647.94   892.7  656.15   990.8  673.68  1118.4  671.04
  1501.2  689.64  1668.2  712.72  1776.1  736.37  1903.8  776.78    2002  787.95
  2532.1  787.02  2856.1  762.47  3081.9  781.88  3543.6  781.58  3691.2  773.46
  3799.5  730.96  3848.7  722.46  3868.4     726  3897.9  747.79  3956.9  763.45
  4055.3  769.86  4114.4  764.39  4173.4  772.52    4380  770.22  4635.9  812.41
#Mann= 3 , 0 , 0
       0      .1       0   421.8    .045       0   596.1     .06       0
Bank Sta=421.8,596.1
XS Rating Curve= 0 ,0
Exp/Cntr=0.3,0.1

Type RM Length L Ch R = 1 ,33093.4 ,338.8,345.4,352.1
XS GIS Cut Line= 6
      1540330.19      357208.697     1540605.228      359890.719
     1541260.368       361066.45     1542774.938      360903.633
     1543641.638      362244.384      1543767.09      363544.945
#Sta/Elev= 30
       0  675.35   364.8   636.1   443.5     635   522.2  635.58  1190.6  674.89
  1416.7  660.14  2075.3   774.9  2429.2  765.88  2655.2  701.32  2812.5  724.77
  2959.8  673.06  3077.7  668.73  3608.2  693.66  3952.1  766.96  4571.2  760.05
  5042.9  671.83  5190.3  704.23  5367.2   685.4  5622.8  761.23  5818.6  673.04
  5965.6  727.45  6200.6  702.68  6367.1  767.84  6847.1  771.09  7111.5  679.25
  7317.5  759.11  7484.5  731.91  7946.2  789.64  8201.7  718.71  8525.8  783.71
#Mann= 3 , 0 , 0
       0      .1       0   364.8    .045       0   522.2     .06       0
Bank Sta=364.8,522.2
XS Rating Curve= 0 ,0
Exp/Cntr=0.3,0.1

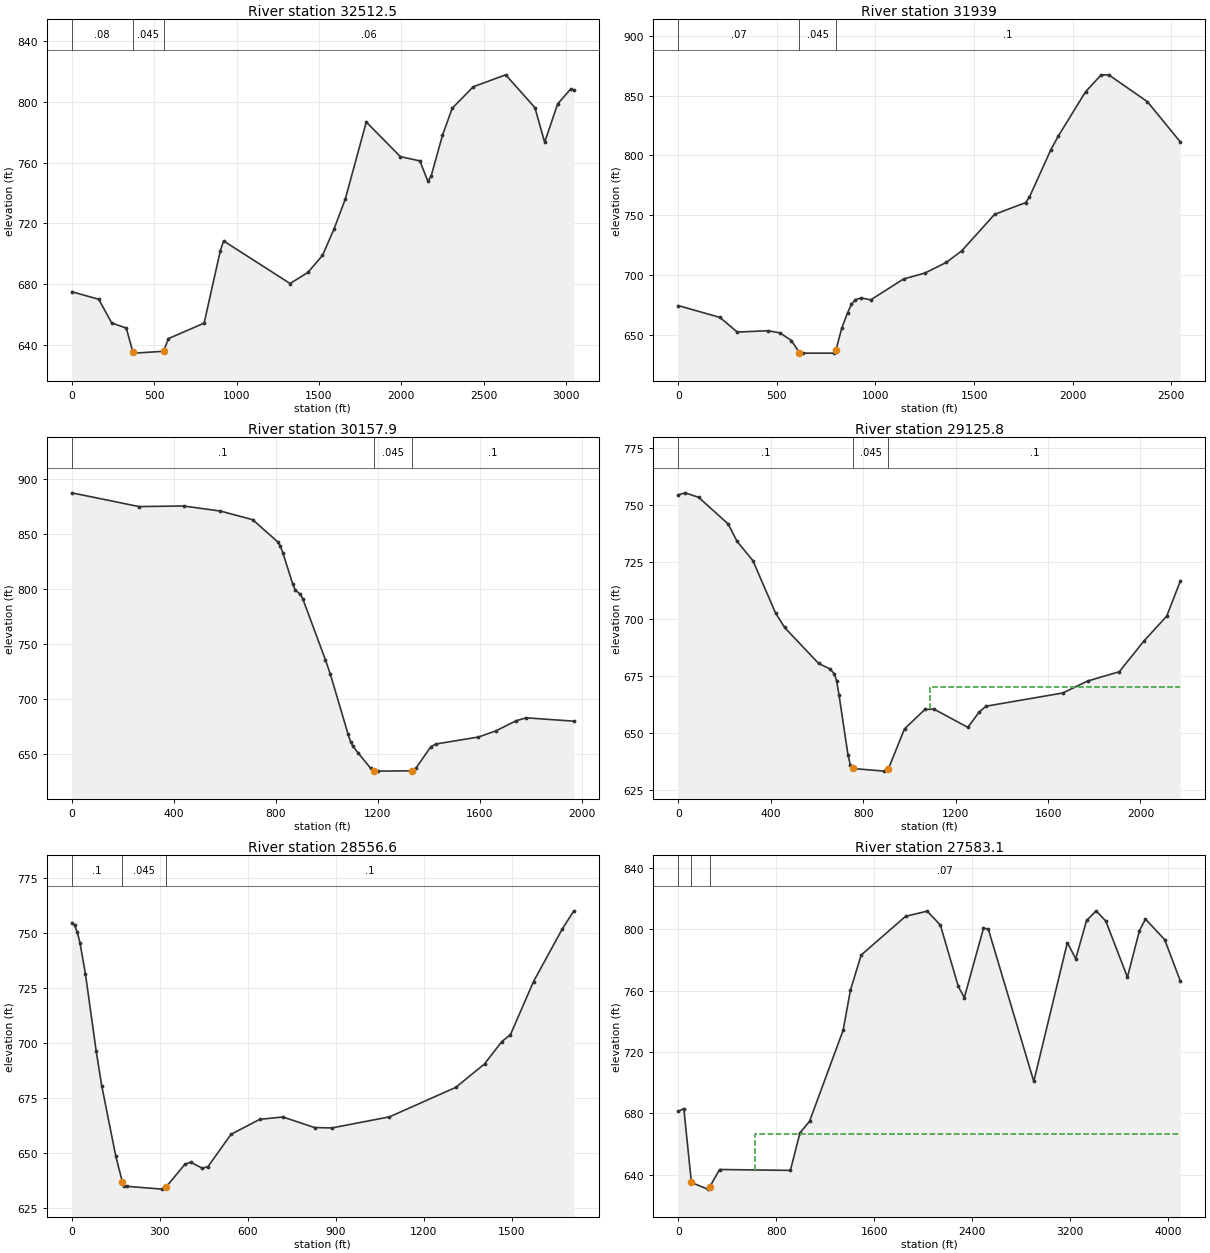
Type RM Length L Ch R = 1 ,32512.5 ,550.7,573.6,596.4
XS GIS Cut Line= 3
     1540094.079      357160.085     1539948.246      357208.697
     1538439.044      359676.434
#Sta/Elev= 30
       0  674.96   163.6  669.99   242.3  654.36   330.8     651   370.2  635.45
     380   634.5   557.1  635.71   586.6  644.08   803.1  654.26   901.5  702.05
   921.2  708.43  1324.6  680.37  1432.8  687.67  1521.3   698.9  1590.2  715.99
  1659.1  735.84    1787  786.81  1993.6  763.97  2111.7  761.17  2160.9  747.73
  2180.5  751.14  2249.4  778.05  2308.4  795.85  2436.4  810.03  2633.1  817.87
  2810.2  796.24  2869.3  773.43    2948  798.66  3026.7  808.48  3046.4   807.8
#Mann= 3 , 0 , 0
       0     .08       0   370.2    .045       0   557.1     .06       0
Bank Sta=370.2,557.1
XS Rating Curve= 0 ,0
Exp/Cntr=0.3,0.1

Type RM Length L Ch R = 1 ,31939   ,936.9,959.1,981.4
XS GIS Cut Line= 3
     1540028.107      357125.363     1539920.468      357160.085
     1537487.655      357197.267
#Sta/Elev= 30
       0  674.28   211.2  664.41   299.5  652.12   456.5  653.24   515.4  651.46
   574.2  645.04   613.5  635.02   633.1   634.5     790   634.5   799.9   637.1
   829.3  655.46   858.7  668.24   878.4  675.36     898   679.2   927.4  680.66
   976.5  679.11  1143.2   696.6  1251.2  701.52  1359.1  710.39  1437.6  720.09
  1604.4  750.65  1761.3  760.43    1781  765.04  1888.9  804.49  1928.1  816.38
  2065.5  853.19    2144  867.23  2183.2  867.41  2379.4  844.92  2546.2  811.24
#Mann= 3 , 0 , 0
       0     .07       0   613.5    .045       0   799.9      .1       0
Bank Sta=613.5,799.9
XS Rating Curve= 0 ,0
Exp/Cntr=0.3,0.1

Type RM Length L Ch R = 1 ,30157.9 ,889.2,887.3,885.4
XS GIS Cut Line= 4
     1541281.875      355531.526     1540941.598      355500.276
     1540618.681      355399.582     1539511.042      356059.304
#Sta/Elev= 30
       0  887.81   263.6   875.3   438.4  875.83   583.3   871.2   709.5  863.36
   807.9  843.16   817.7  839.66   827.6  833.44     867  804.56   876.8  799.26
   896.5  795.48   906.3  791.22   994.9  735.79  1014.6  722.46  1083.5  668.25
  1093.3  661.42  1103.1  657.08  1122.8  651.15    1172  637.11  1184.8  634.95
  1201.6   634.5  1334.8   634.8  1349.2  637.03  1408.2  656.66  1427.9  659.19
  1595.2  665.54  1664.1  671.19  1742.8  680.36  1782.2  683.03  1969.2  679.97
#Mann= 3 , 0 , 0
       0      .1       0  1184.8    .045       0  1334.8      .1       0
Bank Sta=1184.8,1334.8
XS Rating Curve= 0 ,0
Exp/Cntr=0.3,0.1

Type RM Length L Ch R = 1 ,29125.8 ,577.5,569.1,561.1
XS GIS Cut Line= 3
     1539838.115      354067.407      1539736.44      354715.641
     1538480.711      355565.323
#Sta/Elev= 30
       0   754.5    29.4   755.4    88.1  753.44   215.5  741.81   254.6  734.12
   323.2  725.66   421.1  702.71   460.3  696.37   607.2  680.63   656.2  678.21
   675.7  676.02   685.5  672.85   695.3  666.99   734.4  640.58   744.2  636.18
     754  634.57   890.9  633.41   909.2  634.37     979  651.94    1067  660.43
  1106.1  660.62  1252.8   652.6  1301.8  659.25  1331.1  661.86  1663.7  667.66
  1771.3  672.91  1908.2  676.98  2015.8  690.57  2113.6  701.36  2172.3  716.71
#Mann= 3 , 0 , 0
       0      .1       0     754    .045       0   909.2      .1       0
#XS Ineff= 2 , 0
                         1089.74          670.28
Permanent Ineff=
       F       F
Bank Sta=754,909.2
XS Rating Curve= 0 ,0
Exp/Cntr=0.3,0.1

Type RM Length L Ch R = 1 ,28556.6 ,979.5,973.5,966.6
XS GIS Cut Line= 3
     1539271.162      354212.169     1539246.857      354330.224
     1538334.877      355633.031
#Sta/Elev= 30
       0  754.82     9.3  753.67    18.5  750.68    27.8  745.77    46.4  731.69
    83.4  696.18     102  680.64     150  648.47   172.1  636.88   179.4  635.14
   189.2  634.75     307  633.49   322.1  634.59   385.6  644.82   405.2  645.75
   444.5  643.04   464.1  643.73   542.6  658.45   640.8   665.3   719.3  666.34
   827.3  661.54   886.2  661.36  1082.6  666.41  1308.3  679.82  1406.5  690.52
  1465.4  700.71  1494.8  703.85  1573.4  728.04  1671.6  752.04  1710.8  760.24
#Mann= 3 , 0 , 0
       0      .1       0   172.1    .045       0   322.1      .1       0
Bank Sta=172.1,322.1
XS Rating Curve= 0 ,0
Exp/Cntr=0.3,0.1

Type RM Length L Ch R = 1 ,27583.1 ,464.5,484.6,505.3
XS GIS Cut Line= 5
     1538288.523      353969.113     1538285.051       354042.03
     1537660.722      355910.478     1537066.487      356830.783
     1536240.892      357324.352
#Sta/Elev= 30
       0  681.19    45.6  683.11   107.5  634.89   239.6  630.55   257.5  632.05
   337.6  643.34   915.9  642.77   994.3  667.27  1072.7  674.81  1347.1  734.22
  1405.9  760.13  1494.1  783.17  1856.8   808.4  2033.2  811.78  2140.8  802.71
  2287.5  762.65  2336.4  755.41  2492.9  800.62    2532  800.12  2903.7  700.78
  3177.7  791.21  3246.4  780.76  3334.8  805.68  3413.3  811.98  3491.8  805.32
  3668.5  768.75  3766.6  799.03  3815.7  806.61  3972.8   793.2  4100.4  766.28
#Mann= 3 , 0 , 0
       0      .1       0   107.5    .045       0   257.5     .07       0
#XS Ineff= 2 , 0
                          625.16          666.45
Permanent Ineff=
       F       F
Bank Sta=107.5,257.5
XS Rating Curve= 0 ,0
Exp/Cntr=0.3,0.1