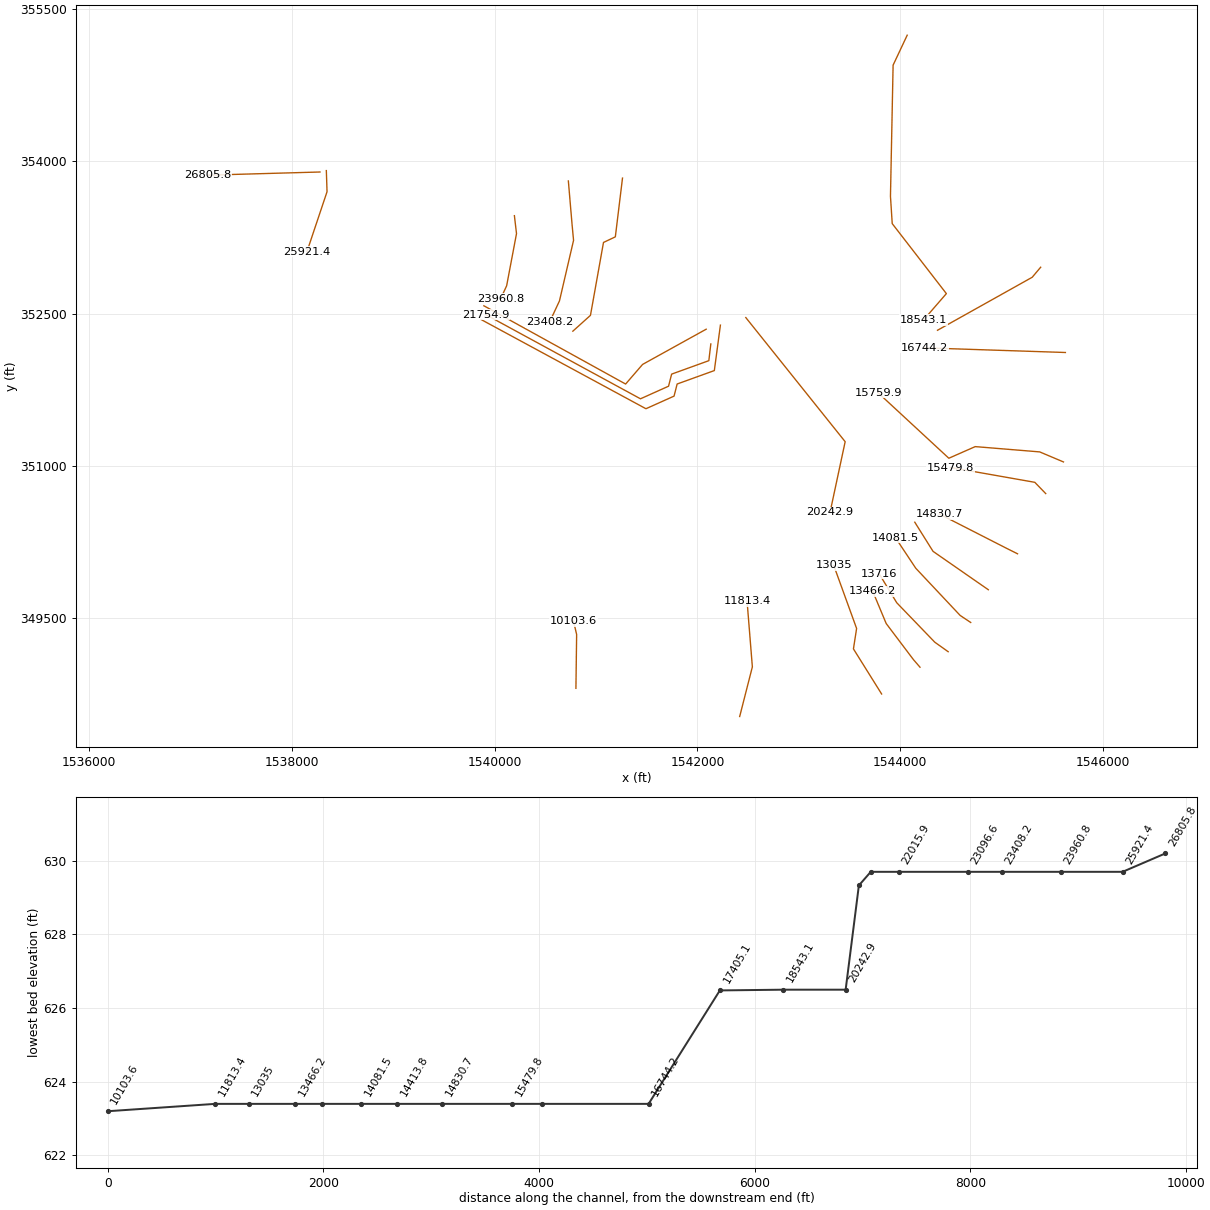
HEC-RAS study MDISLCRK1.prj: MDISLCRK1

--- MDISLCRK1.g02 (geometry) --- (continued)

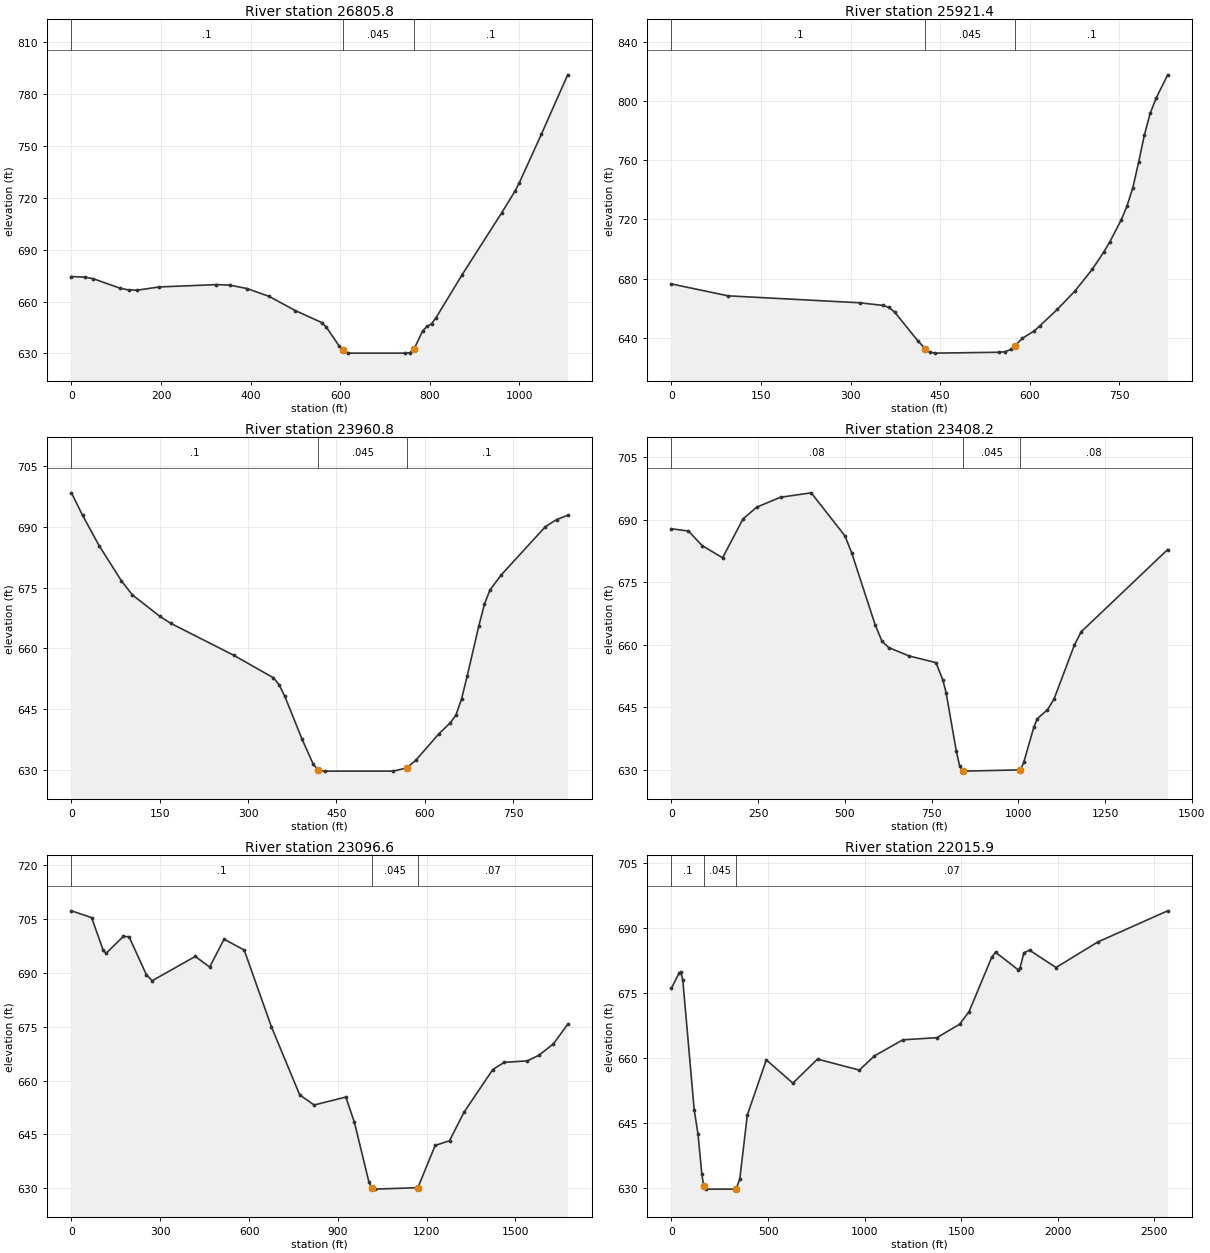
Type RM Length L Ch R = 1 ,26805.8 ,373,397,420.6
XS GIS Cut Line= 2
     1538278.107      353896.197     1537170.468      353864.947
#Sta/Elev= 30
       0  674.41    29.4  674.07      49  673.13   107.9  667.74   127.5  666.66
   147.1  666.56   196.1  668.41   323.6  669.75     353  669.48   392.2  667.47
   441.3  662.96   500.1  654.73   558.9  647.85   568.8  645.33   598.2   634.2
   605.8  631.89   617.8   630.2   745.3   630.2   755.1  630.39   764.9  632.46
   784.5  643.21   794.3  645.59   804.1  647.18   813.9  650.55   872.7  675.58
     961  711.28   990.4  723.67  1000.2  728.61  1049.2  756.42  1108.1  790.84
#Mann= 3 , 0 , 0
       0      .1       0   605.8    .045       0   764.9      .1       0
Bank Sta=605.8,764.9
XS Rating Curve= 0 ,0
Exp/Cntr=0.3,0.1

Type RM Length L Ch R = 1 ,25921.4 ,570.9,570.4,570
XS GIS Cut Line= 3
     1538340.607      353910.085     1538347.551      353701.752
     1538149.634      353111.474
#Sta/Elev= 30
       0   676.4    94.8  668.39   315.4   663.7   354.4   661.9   364.1  660.58
   373.8  657.47   412.7  637.98   425.3  632.57   432.2  630.46   441.9   629.7
   548.9  630.29   558.6  630.66   568.4  632.22   575.3  634.78   587.8  639.75
   607.3  644.62     617  648.12   646.2  659.23   675.4  671.48   704.6  686.19
     724  697.96   733.8  704.55   753.2  719.62   762.9  728.91   772.7  741.39
   782.4  758.51   792.1  777.08   801.8  791.64   811.6  801.72     831   817.6
#Mann= 3 , 0 , 0
       0      .1       0   425.3    .045       0   575.3      .1       0
Bank Sta=425.3,575.3
XS Rating Curve= 0 ,0
Exp/Cntr=0.3,0.1

Type RM Length L Ch R = 1 ,23960.8 ,553.4,552.6,551.6
XS GIS Cut Line= 4
     1540194.773      353465.641     1540215.607      353288.558
     1540118.384      352774.669     1540059.357      352646.197
#Sta/Elev= 30
       0  698.45    18.8   692.9    46.9  685.42    84.5  676.77   103.2  673.27
   150.2  667.93   168.9  666.19   275.2  658.35     343  652.76   352.6  651.07
   362.3  648.18   391.4  637.68   410.8  631.34   419.2  629.98   430.1   629.7
   546.3  629.71   569.2  630.47   585.1  632.44   623.8  638.89   643.2  641.61
   652.9  643.51   662.6  647.58   672.2  653.26   691.6  665.45   701.3  670.92
   710.7  674.44   729.6  678.13     805   690.1   823.8  691.83   842.7   692.9
#Mann= 3 , 0 , 0
       0      .1       0   419.2    .045       0   569.2      .1       0
Bank Sta=419.2,569.2
XS Rating Curve= 0 ,0
Exp/Cntr=0.3,0.1

Type RM Length L Ch R = 1 ,23408.2 ,310.5,311.6,312.9
XS GIS Cut Line= 5
     1540726.805      353807.944     1540762.611      353386.835
     1540778.107      353222.585     1540639.218      352625.363
     1540541.996       352417.03
#Sta/Elev= 30
       0   687.8    49.1  687.26    88.5  683.76   147.4  680.85   206.4  690.17
   245.7  692.98   314.5  695.36     403  696.42   500.3   686.1   519.7  682.03
   587.6  664.73   607.1  660.83   626.5  659.32   684.9  657.32   762.8  655.71
   782.3   651.6     792  648.48   821.2  634.58   830.9  630.95   839.9   629.8
   840.7   629.7  1006.1     630  1015.8   631.8    1045  640.27  1054.8  642.26
    1084  644.39  1103.4  647.03  1161.8  659.91  1181.3  663.09  1430.7  682.82
#Mann= 3 , 0 , 0
       0     .08       0   839.9    .045       0  1006.1     .08       0
Bank Sta=839.9,1006.1
XS Rating Curve= 0 ,0
Exp/Cntr=0.3,0.1

Type RM Length L Ch R = 1 ,23096.6 ,651.4,639.9,628.5
XS GIS Cut Line= 5
     1541260.659      353836.156     1541190.018      353256.834
     1541073.246      353201.752     1540944.773      352483.002
     1540771.162      352326.752
#Sta/Elev= 30
       0  707.33    68.1  705.43     107  696.37   116.7  695.47   175.1  700.17
   194.5  700.11   252.9  689.54   272.4  687.82   418.3  694.61   466.9  691.65
   515.5  699.42   583.6   696.4   675.8  674.92   771.1  655.99   819.8  653.17
   926.9  655.38   956.1  648.29  1004.8  631.74  1014.5  629.99  1024.2   629.7
  1170.3   630.1  1228.7  641.88  1277.4  643.21    1326  651.12  1423.4  663.06
  1462.3  665.07  1540.2  665.48  1579.1  667.04  1627.8  670.18  1676.4  675.64
#Mann= 3 , 0 , 0
       0      .1       0  1014.5    .045       0  1170.3     .07       0
Bank Sta=1014.5,1170.3
XS Rating Curve= 0 ,0
Exp/Cntr=0.3,0.1

Type RM Length L Ch R = 1 ,22015.9 ,264.6,261,257.4
XS GIS Cut Line= 4
     1542085.832      352346.283     1541458.662      351999.061
     1541291.363      351805.559     1539894.133       352577.13
#Sta/Elev= 30
       0  676.12    39.3   679.6    49.1  679.83    58.9   677.9   117.8  648.02
   137.5   642.4   157.1  633.25   166.9  630.42   176.8   629.7   333.9   629.7
   353.5  631.96   392.8  646.82     491  659.55   628.5  654.18   756.2  659.73
   972.7  657.19    1051  660.47  1197.9  664.18  1374.2  664.68  1491.6  667.78
  1540.6  670.67  1658.1  683.25  1677.7  684.42  1795.2  680.34    1805  680.84
  1824.6  684.28    1854  684.88    1991  680.88  2206.5  686.76  2568.8  693.97
#Mann= 3 , 0 , 0
       0      .1       0   166.9    .045       0   333.9     .07       0
Bank Sta=166.9,333.9
XS Rating Curve= 0 ,0
Exp/Cntr=0.3,0.1

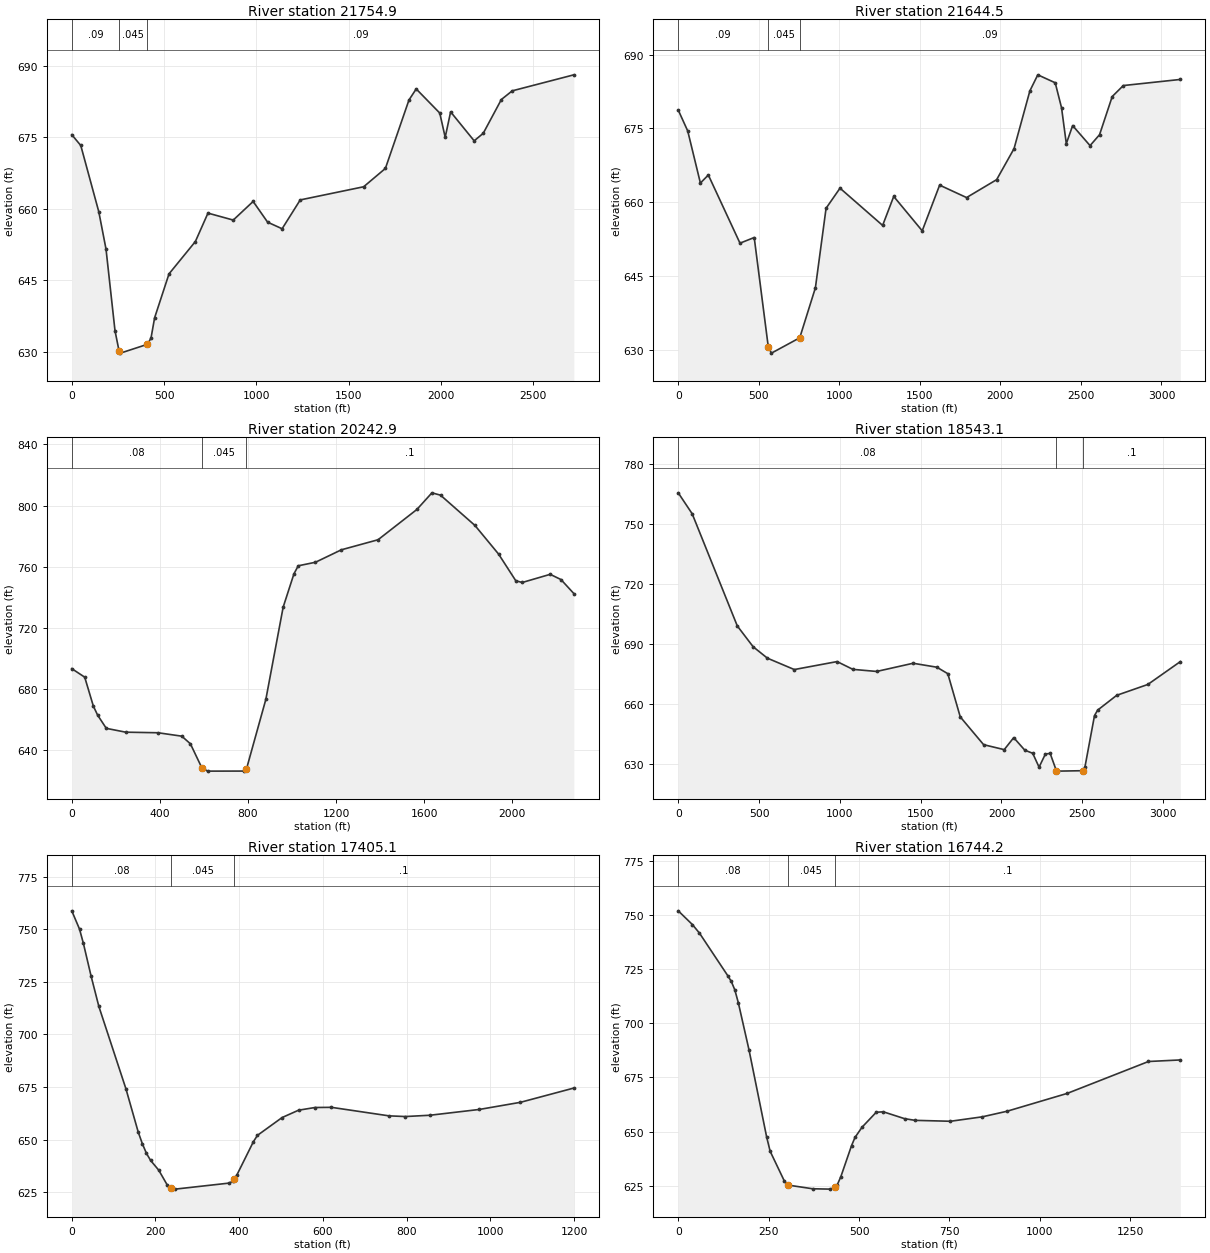
Type RM Length L Ch R = 1 ,21754.9 ,110.4,110.4,110.4
XS GIS Cut Line= 6
     1542131.405      352200.884     1542111.874      352035.953
     1541745.121      351903.575     1541714.739      351784.217
     1541437.901      351660.048     1539911.494      352490.324
#Sta/Elev= 30
       0  675.54    48.8  673.27   146.5  659.35   185.6  651.52   234.3  634.38
   256.5   630.1   263.6   629.7   409.8  631.55   429.3  632.85   448.8  637.11
   526.8  646.33   669.7  653.12   737.9  659.08   874.9  657.62   982.6  661.53
  1061.1  657.18  1139.6   655.8  1237.8  661.85  1581.4  664.61  1699.2  668.46
  1826.8  682.81  1866.1  685.14  1993.7  680.08  2023.2  674.99  2052.6  680.33
  2180.2  674.25  2229.3  675.83  2327.5  682.92  2386.4  684.74  2720.2   688.1
#Mann= 3 , 0 , 0
       0     .09       0   256.5    .045       0   409.8     .09       0
Bank Sta=256.5,409.8
XS Rating Curve= 0 ,0
Exp/Cntr=0.3,0.1

Type RM Length L Ch R = 1 ,21644.5 ,119.6,122.6,125.6
XS GIS Cut Line= 6
     1542225.937      352386.503     1542166.127      351938.297
     1541799.374      351805.919     1541768.992      351686.561
     1541491.806      351562.235     1539866.355      352441.713
#Sta/Elev= 30
       0  678.74      59  674.48   137.6   663.9   186.8  665.54   383.4  651.68
   471.7  652.83   559.4  630.51   578.9  629.33   754.4  632.45   851.6  642.61
   917.9  658.78  1004.4  662.86    1269  655.29  1337.9  661.18  1514.8  654.19
  1622.9  663.48  1790.1  660.95  1976.8  664.59    2085   670.9  2183.3  682.65
  2232.4   685.9  2340.6  684.28  2379.9  679.19  2409.4  671.91  2448.7  675.58
  2556.8  671.51  2615.8  673.73  2694.5  681.49  2763.3  683.72  3117.2  684.96
#Mann= 3 , 0 , 0
       0     .09       0   559.4    .045       0   754.4     .09       0
Bank Sta=559.4,754.4
XS Rating Curve= 0 ,0
Exp/Cntr=0.3,0.1

Type RM Length L Ch R = 1 ,20242.9 ,581,580.4,579.8
XS GIS Cut Line= 3
     1542476.457      352460.867     1543456.011      351237.171
      1543306.81      350540.031
#Sta/Elev= 30
       0  693.46    58.8  687.89      98  668.99   117.6  663.04   156.8  654.45
   244.9  651.95   391.9  651.57   499.6  649.34   538.8  644.36   590.5  628.74
   617.2   626.5   783.7  626.54   793.5   627.9   881.7   673.5   960.1  733.62
  1009.1   755.4  1028.6  760.65    1107  762.98  1224.6  771.11  1391.1  777.67
  1567.5  797.46  1635.8  808.33  1674.9   806.8  1831.2  787.02  1938.6  768.31
  2016.7  750.89    2046  749.75    2173  755.08  2221.8  751.68  2280.4  742.52
#Mann= 3 , 0 , 0
       0     .08       0   590.5    .045       0   793.5      .1       0
Bank Sta=590.5,793.5
XS Rating Curve= 0 ,0
Exp/Cntr=0.3,0.1

Type RM Length L Ch R = 1 ,18543.1 ,603.4,586.3,569.2
XS GIS Cut Line= 6
     1544067.571      355244.954     1543928.682      354949.815
      1543902.64      353656.412     1543920.001      353387.315
     1544453.855      352697.211     1544228.161      352436.794
#Sta/Elev= 30
       0  765.46    86.3     755   365.4     699   463.4  688.61   551.6  682.91
   718.2  677.22   982.8   681.2  1080.8  677.31  1227.8  676.27  1453.2  680.36
  1600.2  678.39    1668  675.15    1745  653.59  1889.5  639.71    2017  637.23
  2075.8  643.22  2144.4  636.96  2193.4  635.41  2232.6  628.48  2271.8  635.03
  2301.2  635.36  2340.5  626.52  2349.2   626.5  2507.1  626.72  2516.9  628.72
  2575.7  654.25  2595.3  656.97    2713  664.35  2905.6  669.77  3106.6  681.18
#Mann= 3 , 0 , 0
       0     .08       0  2340.5    .045       0  2507.1      .1       0
Bank Sta=2340.5,2507.1
XS Rating Curve= 0 ,0
Exp/Cntr=0.3,0.1

Type RM Length L Ch R = 1 ,17405.1 ,673.1,660.9,648.6
XS GIS Cut Line= 3
     1545383.575      352957.394     1545300.242      352858.436
     1544366.301       352335.78
#Sta/Elev= 30
       0  758.72    18.5  750.04    27.7  743.31    46.2  727.67    64.7  713.29
   129.4  674.15   158.8  653.58   168.6  648.07   178.5  643.45   188.3  640.14
   207.9  635.46   227.6  628.62   237.6  626.83   247.2  626.48   374.8  629.32
   384.7  630.18   387.6  631.08   394.5  633.21   433.8  648.95   443.6  652.03
   502.5  660.49   541.8  663.98     581  665.26   620.3  665.35   757.8   661.3
     797  660.97     856  661.59   973.8  664.34    1072  667.73  1199.6  674.51
#Mann= 3 , 0 , 0
       0     .08       0   237.6    .045       0   387.6      .1       0
Bank Sta=237.6,387.6
XS Rating Curve= 0 ,0
Exp/Cntr=0.3,0.1

Type RM Length L Ch R = 1 ,16744.2 ,985.3,984.3,983.1
XS GIS Cut Line= 2
     1545627.362      352116.596     1544239.536      352162.398
#Sta/Elev= 30
       0  751.92    39.1  745.59    58.7  741.63   136.9  721.99   146.7  719.33
   156.5  715.41   166.2  709.47   195.6  687.81   244.5   647.5   254.2  640.88
   293.4  627.16   303.1  625.28   371.6  623.57   420.5   623.4   433.3  624.24
     440  625.46   449.8  629.18   479.2  643.43   488.9  647.28   508.5  652.02
   547.6   658.9   567.2  659.11   625.8  655.95   655.2  655.16     753  654.74
     841  656.79   909.4  659.37  1075.7   667.6  1300.6  682.34  1388.6  683.06
#Mann= 3 , 0 , 0
       0     .08       0   303.1    .045       0   433.3      .1       0
Bank Sta=303.1,433.3
XS Rating Curve= 0 ,0
Exp/Cntr=0.3,0.1

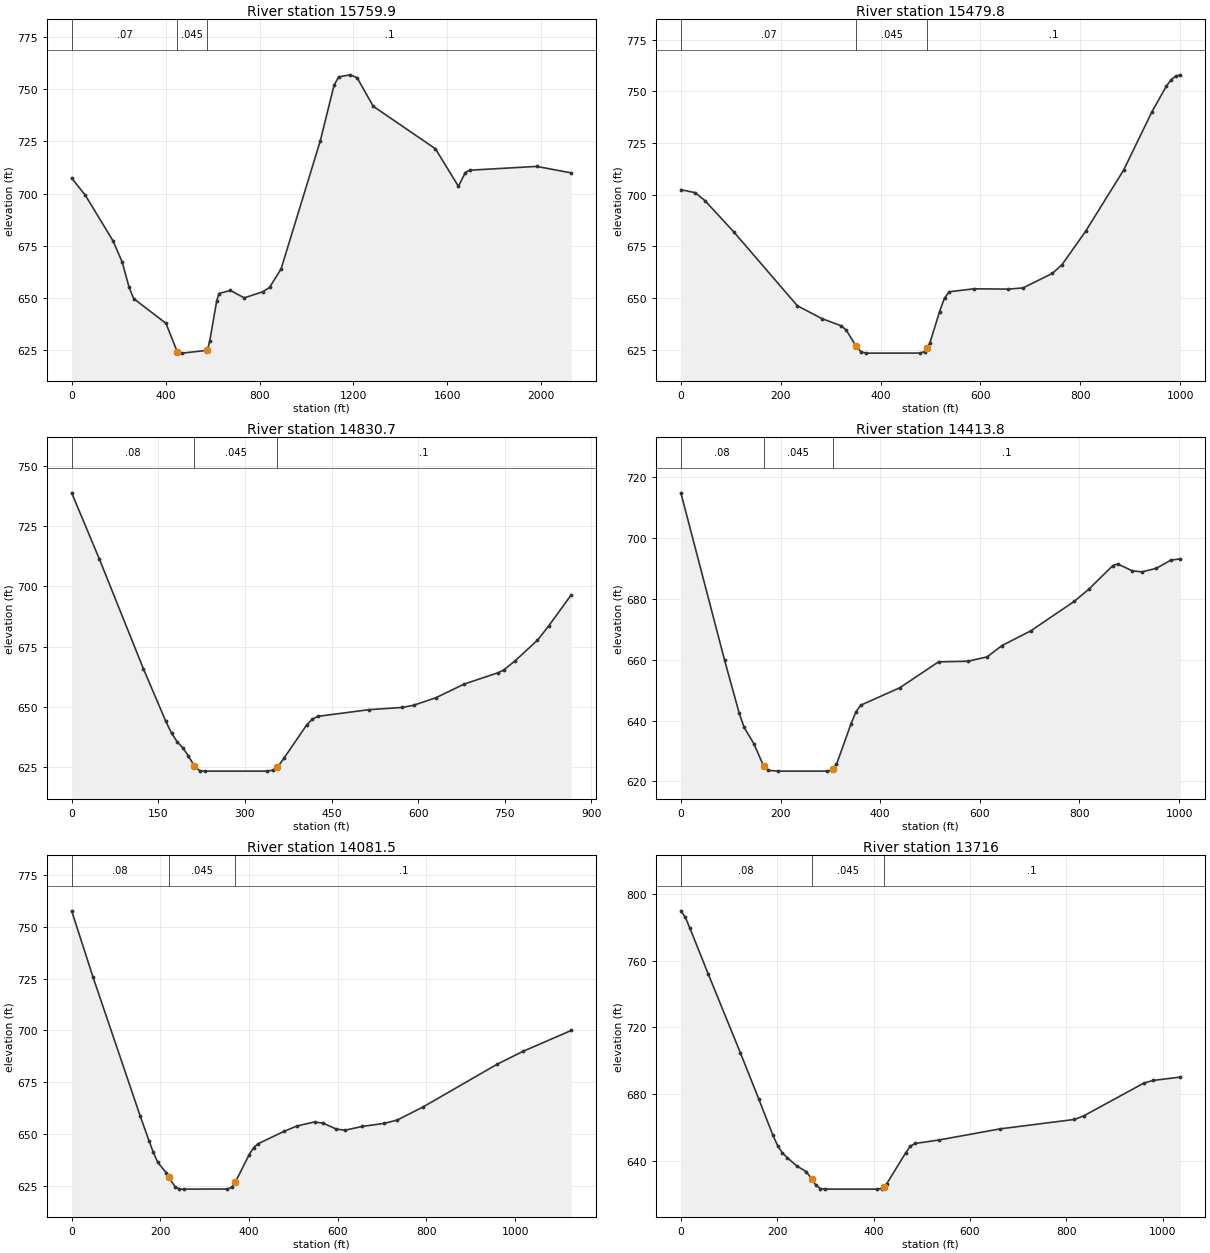
Type RM Length L Ch R = 1 ,15759.9 ,282.3,280.1,278.1
XS GIS Cut Line= 5
     1545608.264      351037.603     1545373.889      351136.561
     1544738.473      351188.644     1544478.056      351074.061
     1543780.139      351719.894
#Sta/Elev= 30
       0  707.44    58.7  699.12   176.1  677.31   215.3  667.12   244.6  655.01
   264.2  649.56   401.5  637.72   450.6  623.78   470.2   623.4   578.1  624.75
   587.9  629.17   617.3  648.22   627.1  652.02   676.2  653.49     735  649.93
   813.5  652.84   842.9  654.96     892  663.88  1058.7  725.27  1117.6  752.07
  1137.2  755.99  1186.3  756.99  1215.7  755.58  1284.3   741.9    1549  721.51
    1647  703.47  1676.4   710.1    1696  711.21  1980.3  713.03  2127.4  709.92
#Mann= 3 , 0 , 0
       0     .07       0   450.6    .045       0   578.1      .1       0
Bank Sta=450.6,578.1
XS Rating Curve= 0 ,0
Exp/Cntr=0.3,0.1

Type RM Length L Ch R = 1 ,15479.8 ,655.8,649,642.3
XS GIS Cut Line= 4
     1545433.402      350725.537     1545325.763      350836.648
     1544735.485      350940.815      1544492.43      350982.481
#Sta/Elev= 30
       0  702.43      29  700.96    48.3  697.13   106.4  681.92   233.3  646.31
   282.4   640.1   321.7  636.58   331.6  634.42   351.2  626.66     361  624.04
   370.9   623.4     479  623.43   488.8  624.15   493.3  625.99   498.6  628.15
   518.3  643.52   528.1  650.08   537.9  653.07     587  654.51   655.8  654.35
   685.3  654.92   744.3  661.97   763.6  666.21     811  682.41   886.9   711.9
   943.8  740.18   972.2  752.37   981.7  755.52   991.2  757.33  1000.7  757.96
#Mann= 3 , 0 , 0
       0     .07       0   351.2    .045       0   493.3      .1       0
Bank Sta=351.2,493.3
XS Rating Curve= 0 ,0
Exp/Cntr=0.3,0.1

Type RM Length L Ch R = 1 ,14830.7 ,420,417,413.9
XS GIS Cut Line= 3
     1545155.624      350131.787     1545044.513      350187.342
     1544384.791      350524.148
#Sta/Elev= 30
       0   738.8    47.8  711.46   124.2  665.88   163.2  643.98     173  639.11
   182.7  635.58   192.4  633.07   202.2  629.73   211.9  625.71   221.7  623.54
   231.4   623.4   338.6   623.4   348.4  623.82   355.9  625.18   358.1  625.58
   367.9  628.86   406.9  642.53   416.6   644.9   426.4  646.12   514.1  648.86
   572.6  649.82     592  650.71     631  653.86   679.8  659.52   738.2  664.18
     748  665.34   767.5  669.05   806.5  677.68     826   683.6     865   696.5
#Mann= 3 , 0 , 0
       0     .08       0   211.9    .045       0   355.9      .1       0
Bank Sta=211.9,355.9
XS Rating Curve= 0 ,0
Exp/Cntr=0.3,0.1

Type RM Length L Ch R = 1 ,14413.8 ,337,332.3,327.6
XS GIS Cut Line= 3
      1544867.43       349777.62     1544322.291      350156.092
     1544142.343      350443.419
#Sta/Elev= 30
       0  714.72    87.8   659.8   117.1  642.42   126.9  637.78   146.4  632.45
   165.9  625.15   175.7  623.66   195.2   623.4   292.8   623.4   302.5  623.63
   305.5  624.23   312.3  625.58   341.6  638.94   351.3  642.81   361.1  645.05
   439.2  650.73   517.2  659.26   575.8  659.45   614.8  660.89   644.1  664.57
   702.4  669.44   789.6   679.1   818.6  683.08     867  690.84   876.7  691.37
   905.8  689.15   925.2  688.78   954.2  689.93   983.3  692.63  1002.7  693.07
#Mann= 3 , 0 , 0
       0     .08       0   165.9    .045       0   305.5      .1       0
Bank Sta=165.9,305.5
XS Rating Curve= 0 ,0
Exp/Cntr=0.3,0.1

Type RM Length L Ch R = 1 ,14081.5 ,365.2,365.5,365.8
XS GIS Cut Line= 4
     1544693.818      349454.703     1544589.652      349524.148
     1544152.152      349989.426     1543951.371      350291.509
#Sta/Elev= 30
       0   757.7    48.2  725.72   154.7  658.64   174.3  646.85   184.2  641.13
     194   636.4   213.6  631.21     219  629.25   233.3  624.51   243.1  623.51
   252.9   623.4   351.2  623.47     361  624.28     369  626.71   400.3  640.05
   410.1  643.31     420  645.26   478.9  651.27   508.4  653.89   547.7  655.83
   567.3  655.19   596.8   652.4   616.5  651.82   655.8  653.68   704.9  655.12
   734.4  656.74   793.3  663.16   959.9  683.72  1018.7  689.97  1126.6  699.97
#Mann= 3 , 0 , 0
       0     .08       0     219    .045       0     369      .1       0
Bank Sta=219,369
XS Rating Curve= 0 ,0
Exp/Cntr=0.3,0.1

Type RM Length L Ch R = 1 ,13716   ,252.5,249.7,247
XS GIS Cut Line= 4
     1544471.596      349166.509     1544339.652      349260.259
     1543964.652      349649.148      1543790.78      349935.606
#Sta/Elev= 30
       0  789.69     9.5  785.72      19  779.17    57.1  751.78   123.8  704.69
   161.9  677.14   191.3  655.46   201.2  649.23     211  645.01   220.8  642.21
   240.4  637.32   260.1  633.87   271.5  629.68   279.7     626   289.6  623.71
   299.4   623.4   407.4   623.4   417.2  623.74   421.5  624.92   427.1  626.45
   466.4  644.93   476.2  648.98     486  650.67   535.1  652.72   662.8  659.41
     817  665.03   836.1  667.13   960.6  686.66   979.8  688.32  1037.2  690.36
#Mann= 3 , 0 , 0
       0     .08       0   271.5    .045       0   421.5      .1       0
Bank Sta=271.5,421.5
XS Rating Curve= 0 ,0
Exp/Cntr=0.3,0.1

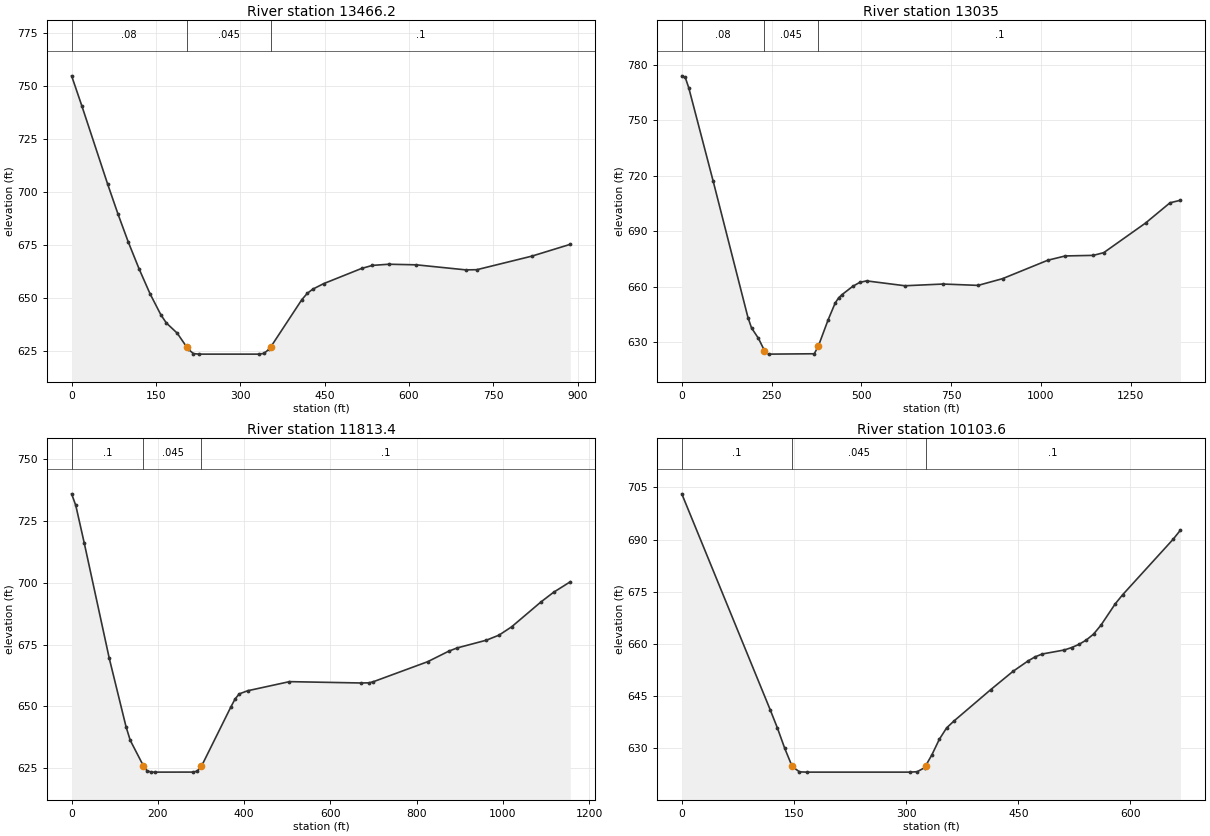
Type RM Length L Ch R = 1 ,13466.2 ,433.1,431.2,429.3
XS GIS Cut Line= 4
     1544193.818      349013.731     1544127.846       349090.12
     1543860.485      349444.287     1543728.541      349760.259
#Sta/Elev= 30
       0  754.63    18.4  740.32    64.2  703.51    82.6   689.4   100.9  676.21
   120.2  663.51   139.5  651.88   158.8  641.94   168.5   638.1   187.8  633.31
   204.4   626.9     207  625.82   216.7  623.66   226.3   623.4   332.5   623.4
   342.1  623.73   351.8  625.83   354.4  626.84   409.6  649.11   419.3  652.08
   428.9  654.02   448.2  656.62   515.8   663.8     535  665.24   564.2  665.79
   613.2  665.51   701.2  663.13   720.8  663.21   818.6   669.6   887.1  675.18
#Mann= 3 , 0 , 0
       0     .08       0   204.4    .045       0   354.4      .1       0
Bank Sta=204.4,354.4
XS Rating Curve= 0 ,0
Exp/Cntr=0.3,0.1

Type RM Length L Ch R = 1 ,13035   ,317.7,310.4,303.1
XS GIS Cut Line= 4
     1543815.346      348749.842     1543537.568      349194.287
     1543568.818      349395.676     1543343.703      350016.565
#Sta/Elev= 30
       0  774.08     9.7  773.18    19.4  767.61    87.4  717.04   184.4  643.12
   194.1  637.62   213.5  631.92   230.1  625.33   232.9  624.29   242.6   623.4
   368.8   623.6   380.1  627.68   407.6  642.05     427  651.05   436.8  653.91
   446.5  655.67   475.6  660.06     495   662.2   514.4  663.06   621.2  660.42
   727.9  661.35     825  660.62     893  664.26  1019.3  674.26  1067.8  676.56
  1145.5  676.87  1174.7  678.33  1291.2  694.38  1359.2  705.33  1388.4  706.72
#Mann= 3 , 0 , 0
       0     .08       0   230.1    .045       0   380.1      .1       0
Bank Sta=230.1,380.1
XS Rating Curve= 0 ,0
Exp/Cntr=0.3,0.1

Type RM Length L Ch R = 1 ,11813.4 ,995.3,997.5,999.5
XS GIS Cut Line= 3
     1542416.041       348527.62     1542541.041      349017.203
     1542488.697      349666.509
#Sta/Elev= 30
       0  736.06     9.7  731.36    29.2  716.25    87.4  669.45   126.3  641.75
     136  636.28   166.6  625.93   174.9  623.98   184.6  623.41   194.3   623.4
   281.8  623.42   291.5  623.82   301.2  625.78   369.2  649.71     379  652.96
   388.7  655.06   408.1  656.33   505.3  660.03   670.6  659.49     690  659.55
   699.7  659.99   826.1  668.12   874.8  672.37   894.2  673.67   962.2  676.82
   991.4  678.86  1020.6  682.22  1088.6  692.29  1117.8  696.19  1156.7  700.46
#Mann= 3 , 0 , 0
       0      .1       0   166.6    .045       0   301.2      .1       0
Bank Sta=166.6,301.2
XS Rating Curve= 0 ,0
Exp/Cntr=0.3,0.1

Type RM Length L Ch R = 1 ,10103.6 ,320.4,319.2,318.1
XS GIS Cut Line= 3
     1540801.457      348805.398     1540808.402      349336.648
     1540777.152      349468.592
#Sta/Elev= 30
       0  703.15   118.1  641.19   127.9  635.87   137.7  630.02   147.6  624.83
   157.4  623.28   167.3   623.2     305   623.2   314.8  623.32   324.7  624.48
   326.2  625.05   334.5  628.19   344.4  632.63   354.2  635.92     364  637.89
   413.2  646.91   442.8  652.13   462.4  655.05   472.3   656.3   482.1  657.14
   511.6  658.29   521.5     659   531.3  659.91     541  661.16   550.7  662.86
   560.4  665.37   579.7  671.56   589.4  674.12   657.2  690.13   666.9  692.74
#Mann= 3 , 0 , 0
       0      .1       0   147.6    .045       0   326.2      .1       0
Bank Sta=147.6,326.2
XS Rating Curve= 0 ,0
Exp/Cntr=0.3,0.1