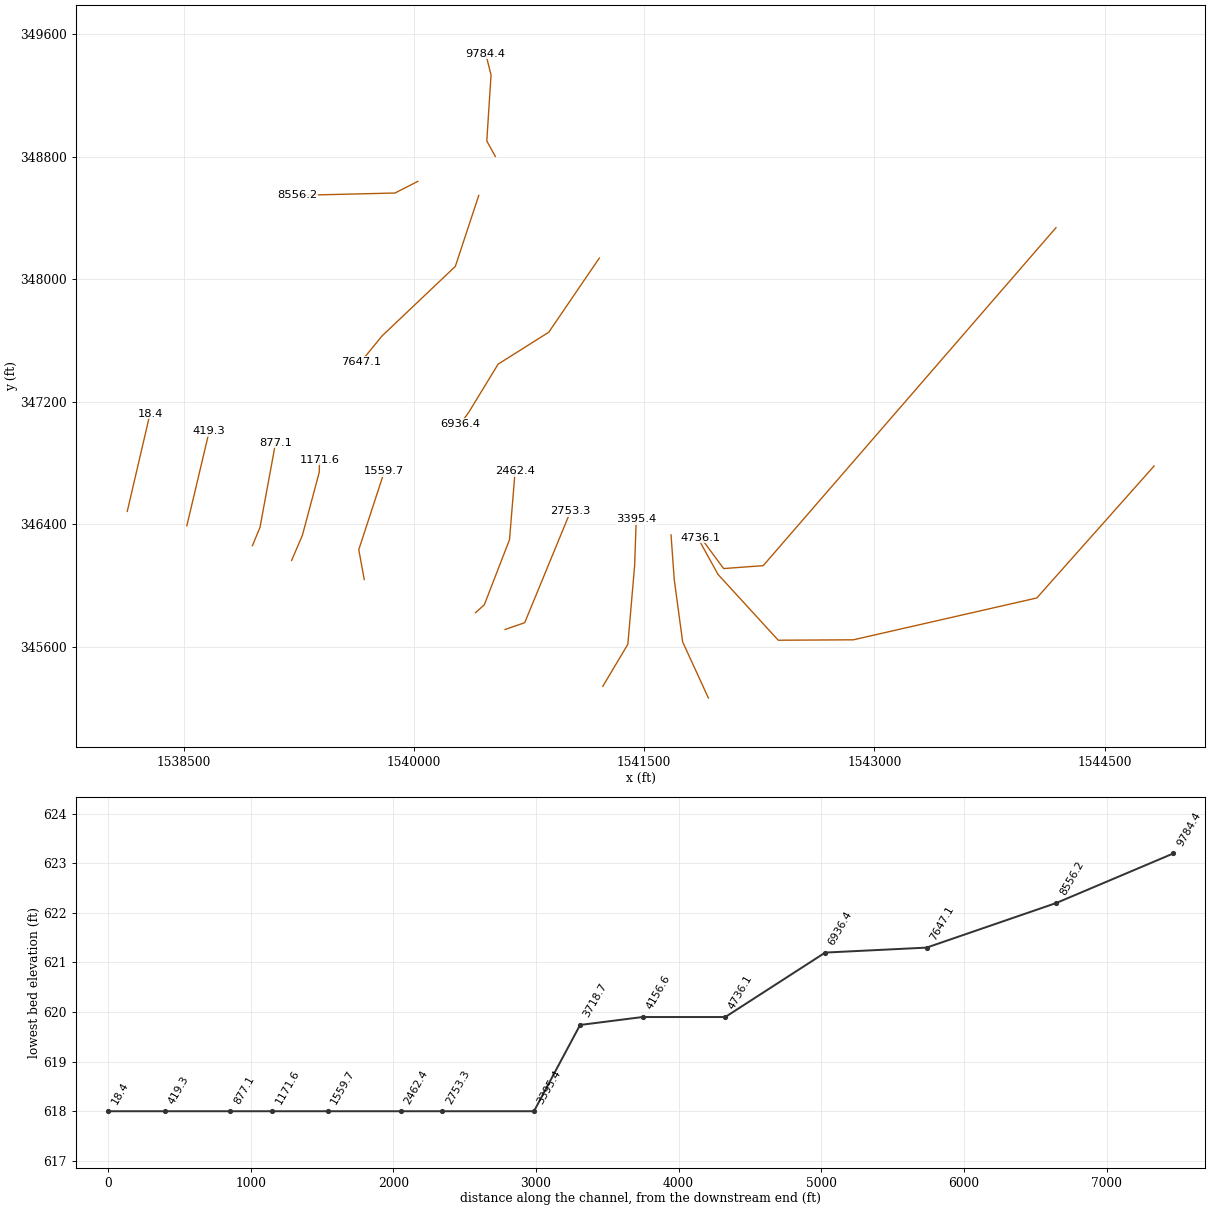
HEC-RAS study MDISLCRK1.prj: MDISLCRK1

--- MDISLCRK1.g02 (geometry) --- (continued)

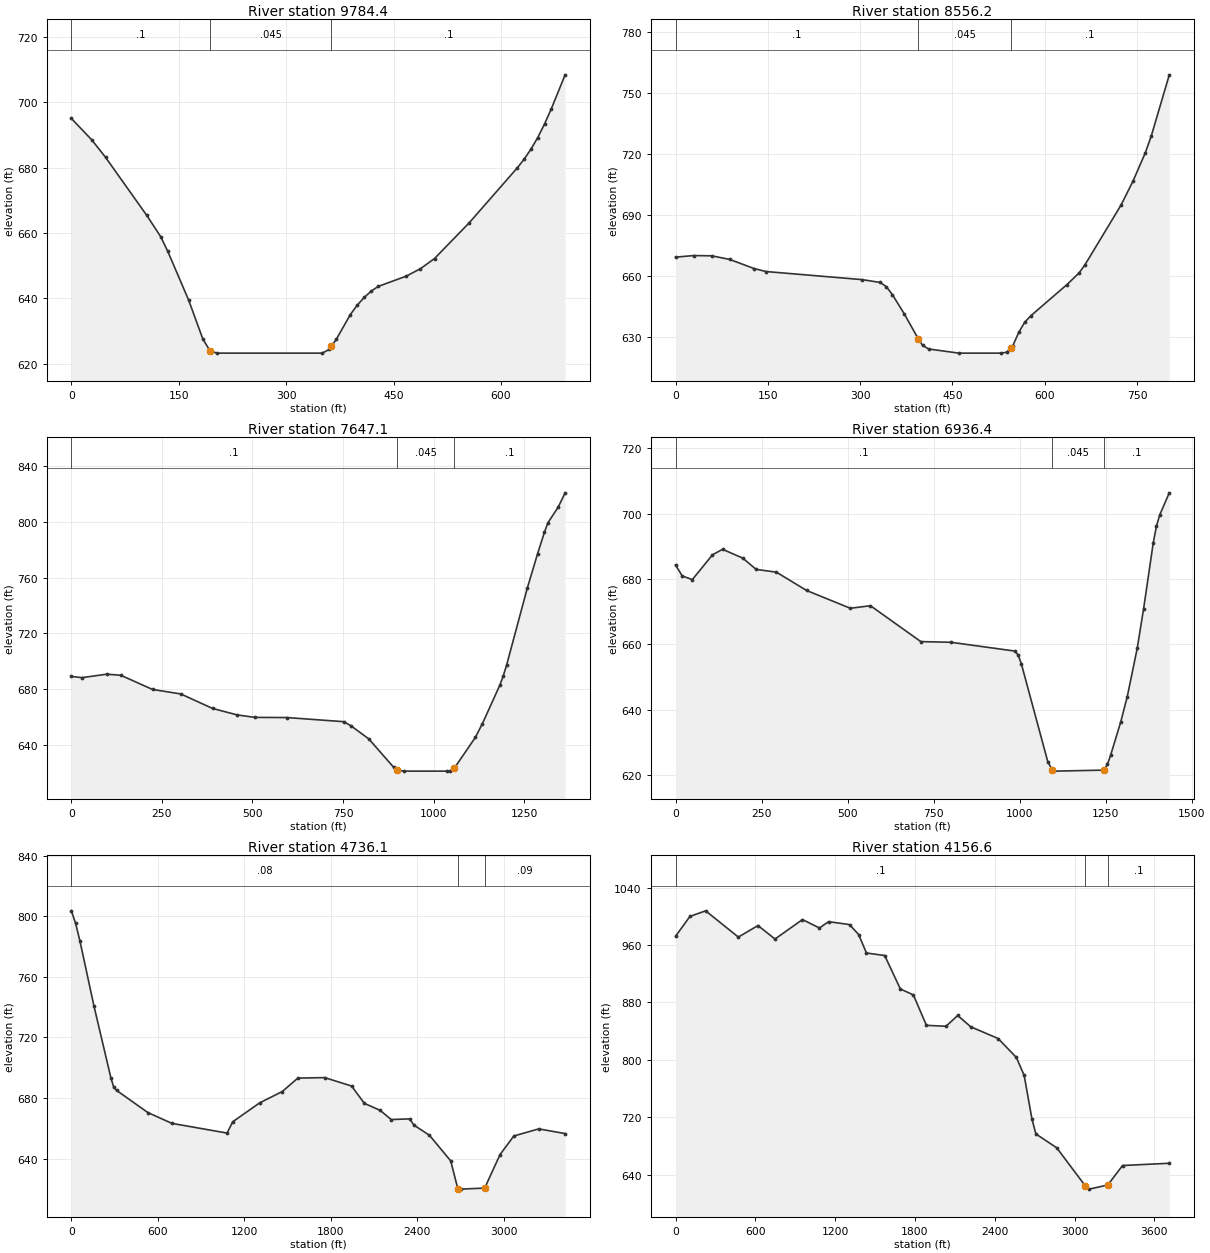
Type RM Length L Ch R = 1 ,9784.4  ,803.9,820.8,837.4
XS GIS Cut Line= 4
     1540530.624      348801.926     1540475.068       348902.62
     1540502.846      349333.176     1540468.124      349472.065
#Sta/Elev= 30
       0  695.03    28.8   688.4    47.9  683.09   105.4  665.33   124.8  658.84
   134.6  654.38     164  639.33   183.6  627.54   193.4  623.98   203.2   623.2
   350.3   623.2   360.2  624.32   363.3   625.3     370  627.41   389.6  634.99
   399.4  637.92   409.2  640.27     419  642.22   428.8  643.63     468  646.79
   487.6  649.05   507.2  652.15     556  663.17   622.8   679.9   632.4  682.57
   641.9  685.62   651.4  689.19     661  693.39   670.5  698.07   689.6  708.38
#Mann= 3 , 0 , 0
       0      .1       0   193.4    .045       0   363.3      .1       0
Bank Sta=193.4,363.3
XS Rating Curve= 0 ,0
Exp/Cntr=0.3,0.1

Type RM Length L Ch R = 1 ,8556.2  ,892.4,909.1,925.8
XS GIS Cut Line= 3
     1540025.416      348638.731     1539877.111        348562.9
     1539241.562      348547.585
#Sta/Elev= 30
       0  669.41    29.4   670.2    58.8  670.07    88.2  668.28   127.4  663.83
     147  662.34   303.5  658.35   332.8  656.95   342.6  654.86   352.4  650.96
     372  641.33   394.5  629.18   401.3  626.06   411.1  624.25     460   622.2
   528.4   622.2   538.2  622.64   544.5   624.7     548  625.84   557.8  632.49
   567.6   637.5   577.4  640.61     636  655.92   655.6  661.61   665.4  665.72
   724.1  695.15   743.6  707.02   763.2  720.66     773     729   802.3  759.11
#Mann= 3 , 0 , 0
       0      .1       0   394.5    .045       0   544.5      .1       0
Bank Sta=394.5,544.5
XS Rating Curve= 0 ,0
Exp/Cntr=0.3,0.1

Type RM Length L Ch R = 1 ,7647.1  ,704.8,710.7,716.6
XS GIS Cut Line= 4
     1540422.725      348546.717     1540270.207      348084.044
     1539793.645      347630.919     1539655.624      347461.648
#Sta/Elev= 30
       0  689.15    29.2  688.28    97.4  690.76   136.4  690.02   224.1  679.82
     302  676.62   389.7  666.23   457.9  661.58   506.8   659.8   595.1  659.69
   752.2  656.73   771.8   653.8   820.9  644.46   889.6  624.14   899.4  621.89
     919   621.3  1036.8   621.3  1046.6  621.48  1056.8  623.21  1115.3  645.42
    1135  655.42  1182.7  682.72  1192.2  689.33  1201.7   697.3  1258.7  752.35
  1287.2  777.08  1306.2  792.55  1315.7  799.25  1344.2   810.5  1363.2  820.72
#Mann= 3 , 0 , 0
       0      .1       0   899.4    .045       0  1056.8      .1       0
Bank Sta=899.4,1056.8
XS Rating Curve= 0 ,0
Exp/Cntr=0.3,0.1

Type RM Length L Ch R = 1 ,6936.4  ,696.5,700.3,704
XS GIS Cut Line= 5
     1541208.315      348138.731     1540878.561      347654.259
     1540548.853      347446.023     1540358.749      347133.523
     1540304.062      347058.002
#Sta/Elev= 30
       0  684.28    19.5  680.91    48.8   679.8   107.4  687.39   136.7  689.07
   195.4  686.37   234.4  682.92     293  682.08   380.9  676.47   507.9  671.03
   566.5  671.81   712.8  660.83   800.5  660.62   985.6  657.94   995.3  656.82
  1004.9  654.08  1081.9  624.07  1094.9  621.54  1101.1   621.2  1244.9  621.51
  1255.2  623.26  1264.8  626.18  1293.7   636.2  1312.9  644.03  1341.8  658.79
  1360.4  670.93  1388.4  691.08  1397.7  696.16  1407.1  699.58    1435  706.35
#Mann= 3 , 0 , 0
       0      .1       0  1094.9    .045       0  1244.9      .1       0
Bank Sta=1094.9,1244.9
XS Rating Curve= 0 ,0
Exp/Cntr=0.3,0.1

Type RM Length L Ch R = 1 ,4736.1  ,617,579.6,542
XS GIS Cut Line= 4
     1544182.244      348336.617     1542275.416      346130.919
     1542017.667      346111.826     1541869.166       346313.21
#Sta/Elev= 30
       0  803.59    29.4  795.33    58.9  783.93   157.1  740.63   274.9  693.06
   294.5  687.08   314.2  685.03   530.1  670.47     697  663.31  1079.9   656.9
  1119.1  664.35  1305.7  676.82  1462.7  684.32  1570.7  693.18  1757.2  693.51
  1943.8  687.93  2032.1  676.49  2140.1  671.97  2218.6  665.82  2346.3  666.28
  2375.7  662.18  2483.7  655.42    2631  638.54  2680.1  620.23  2699.1   619.9
  2866.6  620.59  2973.1  642.72  3068.8  654.98  3241.5  659.66  3424.3  656.56
#Mann= 3 , 0 , 0
       0     .08       0  2680.1    .045       0  2866.6     .09       0
Bank Sta=2680.1,2866.6
XS Rating Curve= 0 ,0
Exp/Cntr=0.3,0.1

Type RM Length L Ch R = 1 ,4156.6  ,452.6,437.9,423.1
XS GIS Cut Line= 6
     1544821.133      346781.061     1544057.244       345919.95
     1542862.697      345646.885     1542373.393      345644.167
     1541981.145      346073.627     1541853.541      346305.398
#Sta/Elev= 30
       0  972.28   108.2  999.97   226.3 1007.75   472.2  971.15   619.8  987.24
   747.7  968.45   954.3  995.54  1082.2  983.86  1151.1  992.64    1308  988.59
  1376.6  974.73  1435.4  948.94  1572.6  945.49  1690.3  898.85  1788.3  890.53
  1886.3  848.16  2033.4  846.88  2121.6  861.88  2219.6  846.12  2425.4   829.8
  2562.4  803.44  2621.1  778.47  2679.8  717.51  2709.2  696.84  2865.8  677.54
  3081.2  624.35  3110.2   619.9  3249.7  625.65    3361  652.81  3712.4  655.95
#Mann= 3 , 0 , 0
       0      .1       0  3081.2    .045       0  3249.7      .1       0
Bank Sta=3081.2,3249.7
XS Rating Curve= 0 ,0
Exp/Cntr=0.3,0.1

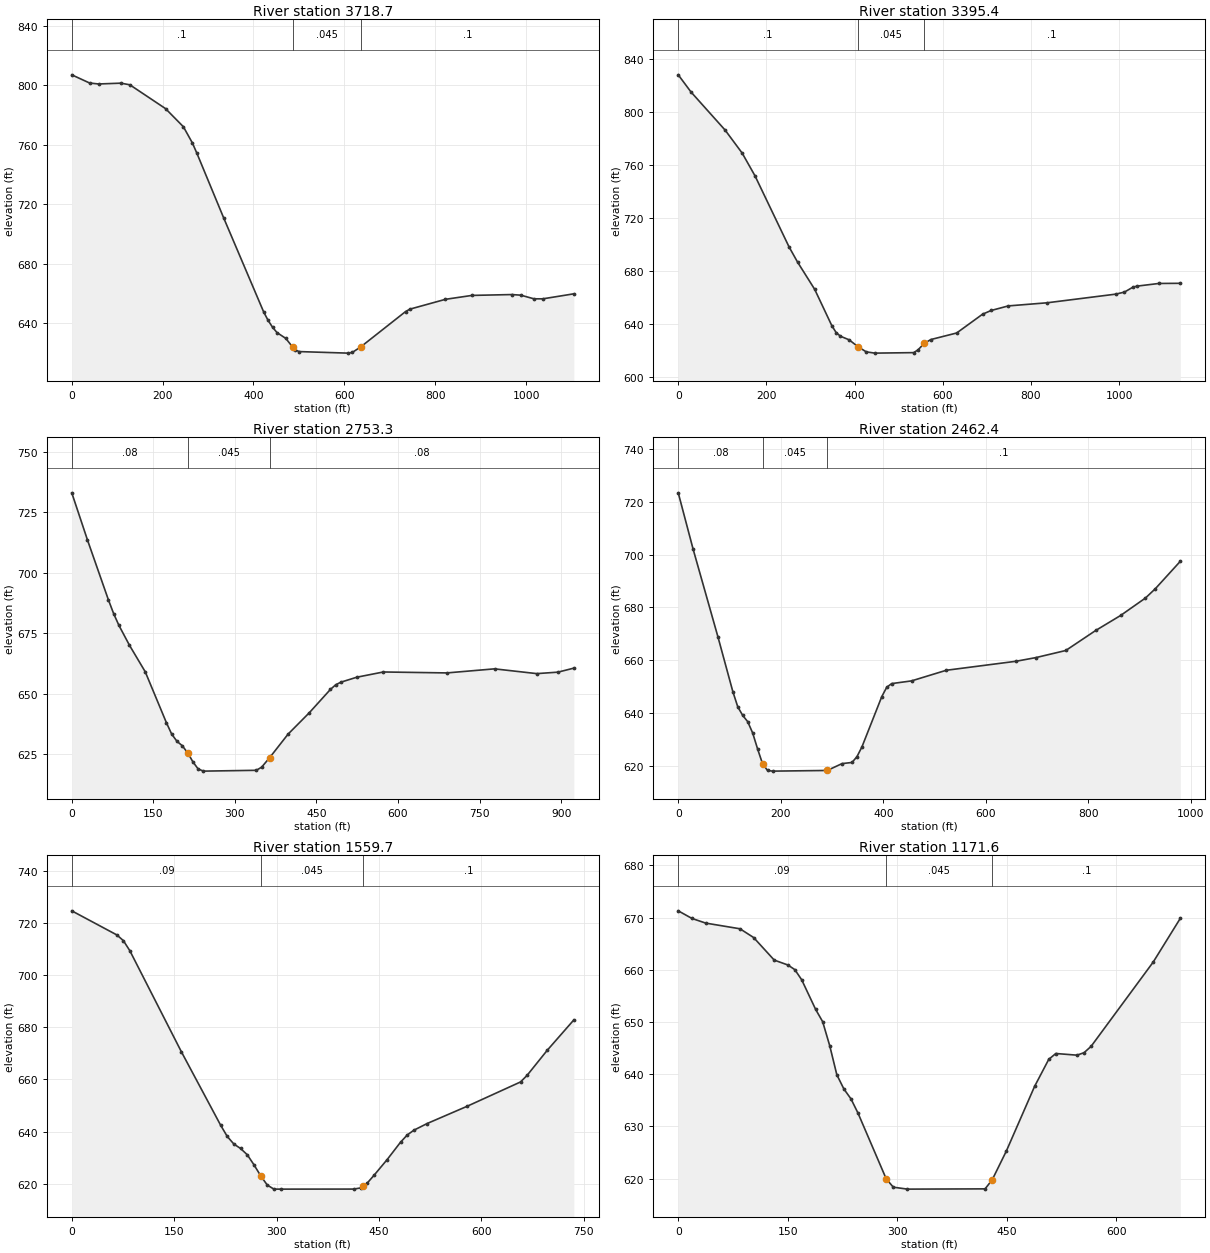
Type RM Length L Ch R = 1 ,3718.7  ,328.2,323.2,318.3
XS GIS Cut Line= 4
     1541918.356      345267.172     1541750.676      345633.523
     1541695.989      346039.773     1541675.155       346331.44
#Sta/Elev= 30
       0  807.11    39.3  801.59      59  800.95   108.1   801.5   127.8   800.4
   206.4  784.36   245.7  772.15   265.3  761.36   275.2  754.48   334.1  710.99
   422.4  647.48   432.2  641.76   441.9  637.21   451.7  633.58   471.2  629.64
     486  623.89   490.7  622.05   500.5  620.78   607.9  619.74   617.6  620.21
     636  623.92   734.7   647.7   744.5  649.37   822.6  655.97     881   658.6
   968.8  659.17   988.3  658.77  1017.5   656.3    1037   656.3  1105.2  659.67
#Mann= 3 , 0 , 0
       0      .1       0     486    .045       0     636      .1       0
Bank Sta=486,636
XS Rating Curve= 0 ,0
Exp/Cntr=0.3,0.1

Type RM Length L Ch R = 1 ,3395.4  ,648.8,642.1,635.1
XS GIS Cut Line= 4
     1541230.856      345343.561     1541393.905      345617.898
     1541438.176      346133.523     1541448.593      346435.606
#Sta/Elev= 30
       0  828.22      29  815.24   106.4  786.45   145.1  769.06   174.1  751.94
   251.4  698.22   270.8  686.69   309.5   666.2   348.4  638.74   358.2  633.52
     368  630.76   387.5  628.07   407.8  622.85   426.5  618.95   446.1     618
     534  618.38   543.7  620.39   557.8   625.3     573  628.26   631.6  633.21
   690.2  647.38   709.7   650.2   748.8  653.67   836.6  656.02   992.7  662.57
  1012.2  664.12  1031.7  667.88  1041.4  668.64  1090.2  670.62  1138.9  670.74
#Mann= 3 , 0 , 0
       0      .1       0   407.8    .045       0   557.8      .1       0
Bank Sta=407.8,557.8
XS Rating Curve= 0 ,0
Exp/Cntr=0.3,0.1

Type RM Length L Ch R = 1 ,2753.3  ,290.4,290.9,291.4
XS GIS Cut Line= 3
     1540594.426      345714.252      1540722.03      345758.523
     1541021.509       346487.69
#Sta/Elev= 30
       0  733.05    28.9  713.54    67.5  688.73    77.2  683.01    86.8  678.21
   106.1  670.03   135.1  659.07     174  638.04   183.7  633.32   193.5  630.31
   203.2  628.51     214  625.29   222.6  621.88   232.4   618.9   242.1     618
   339.4  618.34   349.2  619.65     364   623.6   397.8   633.3   436.8  642.13
   475.7  651.79   485.4   653.7   495.1  654.79   524.3  656.83     573  658.99
   689.8   658.6   777.4  660.28   855.2  658.31   894.1  658.92   923.3  660.58
#Mann= 3 , 0 , 0
       0     .08       0     214    .045       0     364     .08       0
Bank Sta=214,364
XS Rating Curve= 0 ,0
Exp/Cntr=0.3,0.1

Type RM Length L Ch R = 1 ,2462.4  ,512.5,511.9,511.3
XS GIS Cut Line= 4
     1540401.718      345823.627     1540459.009       345875.71
     1540623.072       346300.19      1540659.53      346745.502
#Sta/Elev= 30
       0  723.36      29  702.05    77.4  668.86   106.5  648.11   116.2   642.3
   125.8  639.08   135.5  636.73   145.2  632.43   154.9  626.33   164.6   620.7
   174.2  618.26   183.9     618   290.7  618.25   319.5  620.85   338.9  621.28
   348.5  623.44   358.2  627.12     397   646.2   406.6  649.73   416.3  651.14
     455  652.16   522.8  656.18   658.8  659.59   697.6  660.98   755.9  663.67
   814.2  671.24   862.8  676.92   911.3  683.53   930.8   687.1   979.3  697.44
#Mann= 3 , 0 , 0
       0     .08       0   164.6    .045       0   290.7      .1       0
Bank Sta=164.6,290.7
XS Rating Curve= 0 ,0
Exp/Cntr=0.3,0.1

Type RM Length L Ch R = 1 ,1559.7  ,386.8,388.1,389.3
XS GIS Cut Line= 3
      1539677.13      346039.918     1539641.301      346235.085
     1539807.968      346745.502
#Sta/Elev= 30
       0  724.57    66.1  715.33    75.6  713.15      85  709.32   160.6  670.57
     218   642.5   227.7  638.18   237.5  635.25   247.2  633.57     257  631.18
   266.8  627.35     277  622.98   286.3  619.58     296  618.01   305.8     618
   413.2  618.02     423  618.46     427  619.21   432.7  620.29   442.5  623.23
     462  629.33   481.5  635.95   491.3  638.72   501.1  640.57   520.6  643.13
   579.2  649.74   657.3  659.04     667  661.59   696.3  671.13   735.4   682.8
#Mann= 3 , 0 , 0
       0     .09       0     277    .045       0     427      .1       0
Bank Sta=277,427
XS Rating Curve= 0 ,0
Exp/Cntr=0.3,0.1

Type RM Length L Ch R = 1 ,1171.6  ,292.7,294.5,296.2
XS GIS Cut Line= 4
     1539203.801      346164.773     1539274.114      346328.835
     1539383.813      346740.207     1539386.093      346823.627
#Sta/Elev= 30
       0  671.31    18.8  669.85    37.6  668.96    84.6  667.87   103.3  666.19
   131.5  661.87   150.3  660.93   159.7  660.04   169.1   658.1   188.2  652.43
   197.8  650.08   207.5  645.47   217.2  639.92   226.9  637.18   236.6  635.29
   246.2  632.57   284.9  619.96   294.6  618.37     314     618   420.3  618.05
   430.1   619.8   449.4  625.29   488.1  637.68   507.5  642.86   517.2  643.98
   546.2  643.66   555.9  644.14   565.5  645.35   650.6   661.5   687.7  669.87
#Mann= 3 , 0 , 0
       0     .09       0   284.9    .045       0   430.1      .1       0
Bank Sta=284.9,430.1
XS Rating Curve= 0 ,0
Exp/Cntr=0.3,0.1

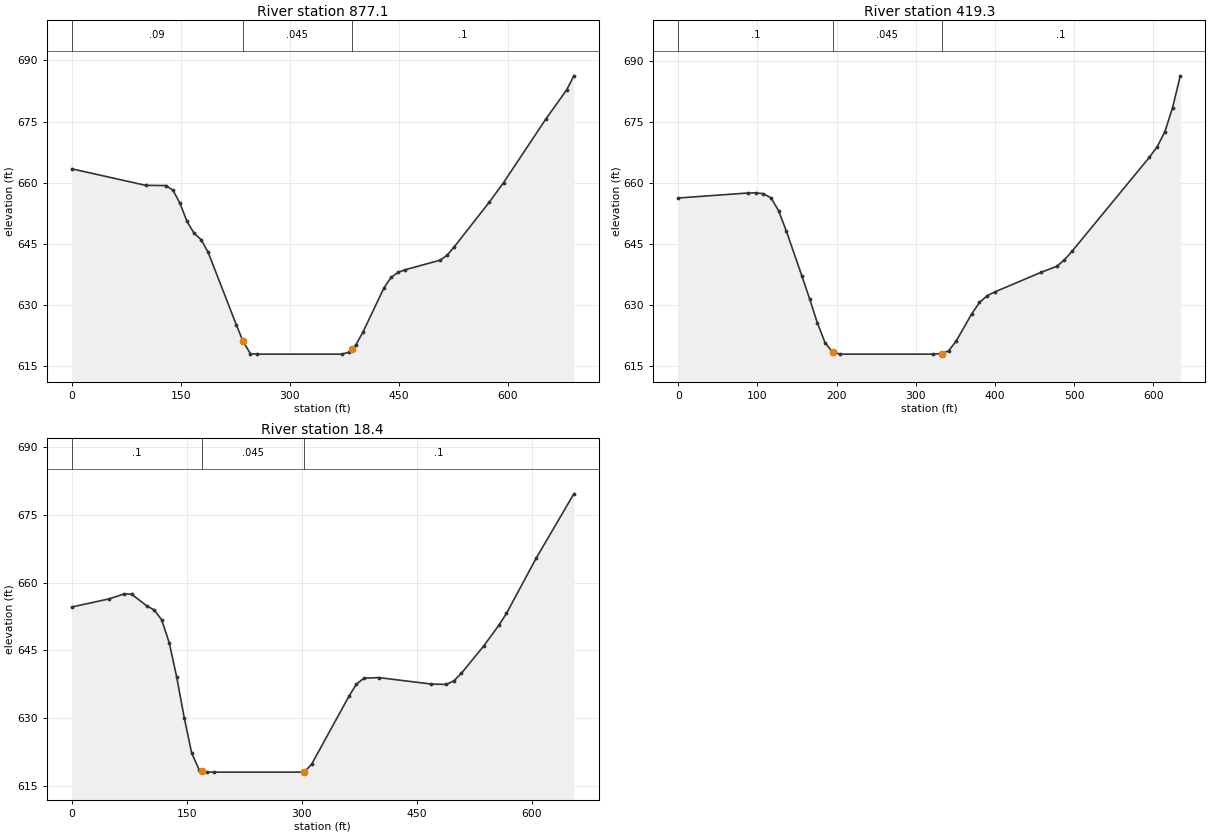
Type RM Length L Ch R = 1 ,877.1   ,459,457.8,456.7
XS GIS Cut Line= 3
     1538948.593      346261.127     1538998.072      346380.919
     1539099.634      346933.002
#Sta/Elev= 30
       0  663.41   101.8  659.36   129.6  659.31   139.3  658.17     149  654.93
   158.6  650.51   168.3  647.66     178  646.06   187.7  642.95   226.4  625.22
   235.3  621.31   245.8   618.1   255.4     618   371.6     618   381.2  618.44
   385.3  619.21   390.9  620.25   400.6  623.34   429.6  634.21   439.3  636.78
     449  638.02   458.7  638.67   507.1  641.03   516.7  642.25   526.4   644.3
   574.8  655.28   594.2  660.02   652.2  675.54   681.3  682.81     691   686.2
#Mann= 3 , 0 , 0
       0     .09       0   235.3    .045       0   385.3      .1       0
Bank Sta=235.3,385.3
XS Rating Curve= 0 ,0
Exp/Cntr=0.3,0.1

Type RM Length L Ch R = 1 ,419.3   ,400.7,400.8,400.9
XS GIS Cut Line= 2
     1538521.509      346391.335     1538667.343      347008.523
#Sta/Elev= 30
       0  656.31    87.8  657.54    97.6  657.57   107.3  657.39   117.1  656.36
   126.8  653.18   136.6  648.18   156.1  637.24   165.9   631.6   175.6  625.75
   185.4  620.81   195.1  618.44   204.9     618     322     618   332.7  618.14
   341.5   618.8   351.2  621.24   370.8  627.92   380.5  630.68   390.3  632.34
     400  633.27   458.6   638.1   478.1  639.54   487.8  641.13   497.6  643.28
   595.2  666.32   604.9  668.86   614.7  672.56   624.4  678.48   634.2  686.29
#Mann= 3 , 0 , 0
       0      .1       0   195.1    .045       0   332.7      .1       0
Bank Sta=195.1,332.7
XS Rating Curve= 0 ,0
Exp/Cntr=0.3,0.1

Type RM Length L Ch R = 1 ,18.4    ,21,18.4,15.9
XS GIS Cut Line= 2
     1538133.489      346485.085     1538281.926      347123.106
#Sta/Elev= 30
       0  654.62    48.9  656.43    68.4  657.53    78.2  657.45    97.8  654.88
   107.6  653.96   117.3  651.78   127.1  646.74   136.9  639.11   146.7  630.11
   156.4  622.25   166.2  618.53   170.4  618.31     176  618.01   185.8     618
   303.1     618   312.9  619.74   361.8  634.87   371.5  637.52   381.3  638.84
   400.9  638.96   469.3  637.53   488.8  637.45   498.6  638.25   508.4  639.93
   537.7  646.02   557.3  650.59   567.1  653.18   606.2  665.52   655.1  679.72
#Mann= 3 , 0 , 0
       0      .1       0   170.4    .045       0   303.1      .1       0
Bank Sta=170.4,303.1
XS Rating Curve= 0 ,0
Exp/Cntr=0.3,0.1